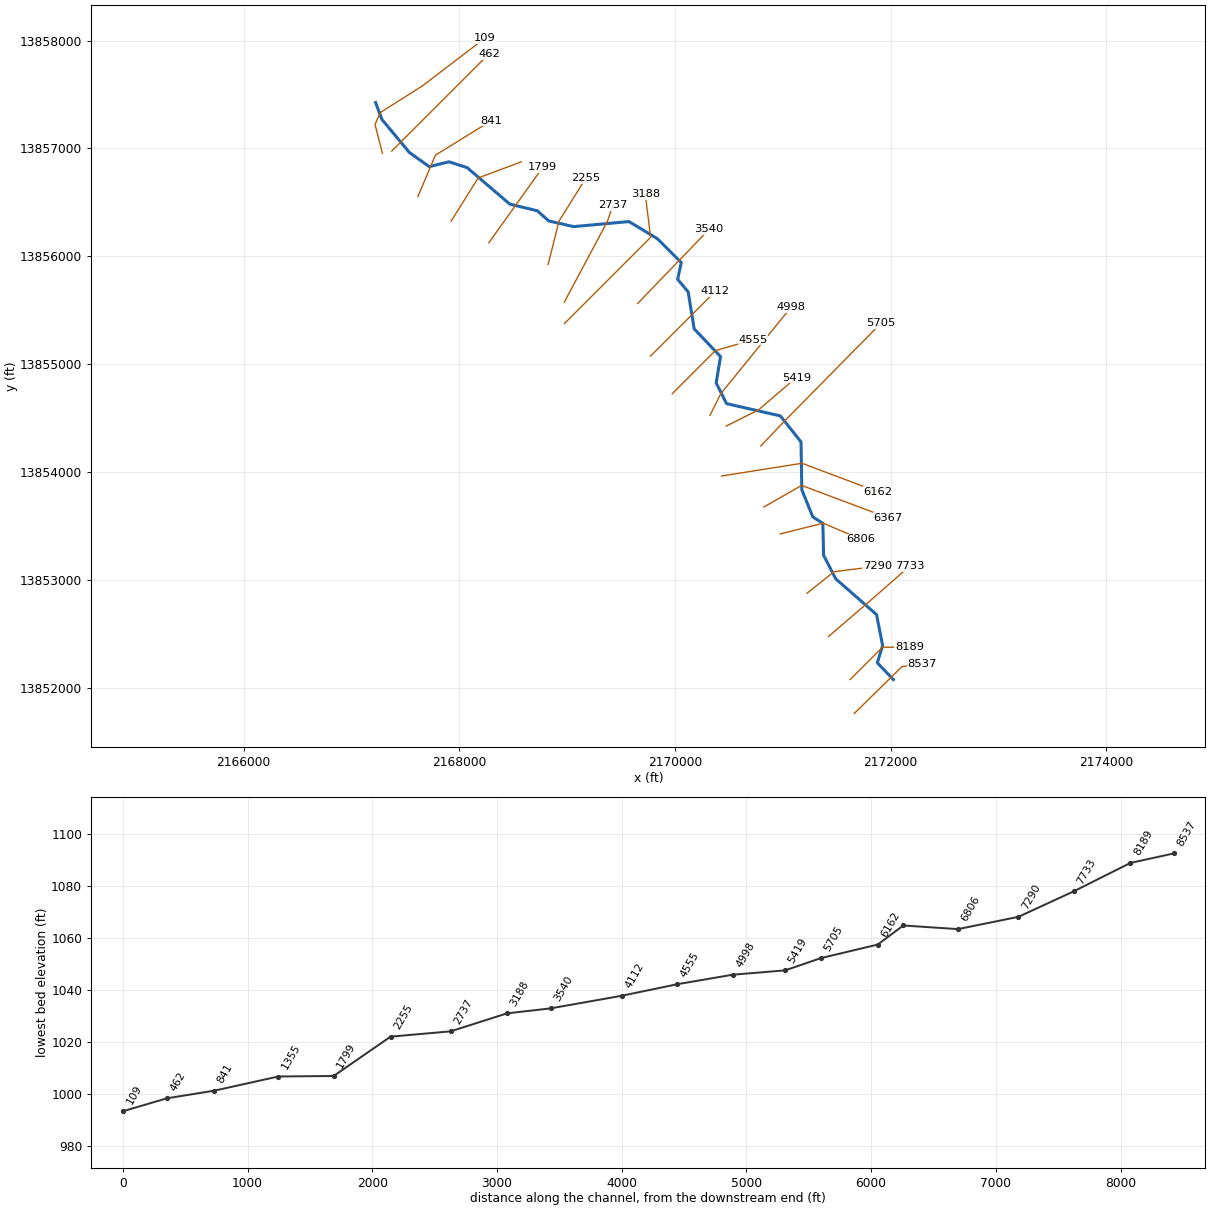
--- Miller Tributary 1.prj (project) ---

Proj Title=Miller Tributary 1 Base Level Engineering
Current Plan=p01
Default Exp/Contr=0.3,0.1
English Units
Geom File=g01
Flow File=f01
Plan File=p01
Y Axis Title=Elevation
X Axis Title(PF)=Main Channel Distance
X Axis Title(XS)=Station
BEGIN DESCRIPTION:
Miller Tributary 1
END DESCRIPTION:
DSS Export Rating Curves= 0
DSS Export Rating Curve Sorted= 0
DSS Export Volume Flow Curves= 0
DXF OffsetX= 0
DXF OffsetY= 0
DXF ScaleX= 1
DXF ScaleY= 10

--- Miller Tributary 1.p01 (plan) ---

Plan Title=Multiple Run
Short Identifier=Multiple
Geom File=g01
Flow File=f01
Subcritical Flow
K Sum by GR= 0
Std Step Tol= 0.01
Critical Tol= 0.01
Num of Std Step Trials= 20
Max Error Tol= 0.3
Flow Tol Ratio= 0.001
Split Flow NTrial= 30
Split Flow Tol= 0.02
Split Flow Ratio= 0.02
Log Output Level= 0
Friction Slope Method= 1
Unsteady Friction Slope Method= 2
Unsteady Bridges Friction Slope Method= 1
Parabolic Critical Depth
Global Vel Dist=  1 , 1 , 1
Global Log Level= 0
CheckData=True
Encroach Param= -1, 0, 0, 0
BEGIN DESCRIPTION:
Multiple Run
END DESCRIPTION:

--- Miller Tributary 1.f01 (steady flow) ---

Flow Title=Multiple
Number of Profiles=7
Profile Names=10-year,25-year,50-year,1pct_min,100-year,1pct_plu,500-year
River Rch & RM= Miller Tributary,Reach-1,8537
    1125    1918    2676    1809    3610    7204    6503
River Rch & RM= Miller Tributary,Reach-1,7733
    1332    2292    3218    2187    4364    8707    7947
River Rch & RM= Miller Tributary,Reach-1,5705
    2368    4193    5998    4145    8270   16501   15584
Boundary for River Rch & Prof#=Miller Tributary,Reach-1,1
Up Type=0
Dn Type=3
Dn Slope=0.005
Boundary for River Rch & Prof#=Miller Tributary,Reach-1,2
Up Type=0
Dn Type=3
Dn Slope=0.005
Boundary for River Rch & Prof#=Miller Tributary,Reach-1,3
Up Type=0
Dn Type=3
Dn Slope=0.005
Boundary for River Rch & Prof#=Miller Tributary,Reach-1,4
Up Type=0
Dn Type=3
Dn Slope=0.005
Boundary for River Rch & Prof#=Miller Tributary,Reach-1,5
Up Type=0
Dn Type=3
Dn Slope=0.005
Boundary for River Rch & Prof#=Miller Tributary,Reach-1,6
Up Type=0
Dn Type=3
Dn Slope=0.005
Boundary for River Rch & Prof#=Miller Tributary,Reach-1,7
Up Type=0
Dn Type=3
Dn Slope=0.005

--- Miller Tributary 1.g01 (geometry) ---

Geom Title=Existing Conditions
Program Version=4.10

River Reach=Miller Tributary,Reach-1
Reach XY= 30
        2172025.       13852075.      2171876.73     13852230.62
      2171925.71     13852390.06      2171869.55     13852677.47
      2171491.64     13853008.32      2171378.75     13853226.55
      2171371.52     13853523.74      2171278.19     13853583.35
      2171176.36     13853834.65      2171169.54     13854277.45
      2170977.48      13854519.6      2170478.66     13854633.17
      2170382.53     13854824.99      2170422.83     13855069.56
      2170178.55     13855326.47      2170122.81     13855669.55
      2170025.61     13855785.63      2170058.78     13855941.68
      2169834.68     13856164.24      2169573.53     13856321.45
      2169061.18     13856274.56      2168830.45     13856327.19
      2168723.53     13856421.44      2168468.94     13856483.14
       2168073.5     13856821.39      2167904.82     13856875.28
      2167722.58     13856830.41      2167538.49     13856961.44
      2167283.05     13857268.67        2167225.       13857425.

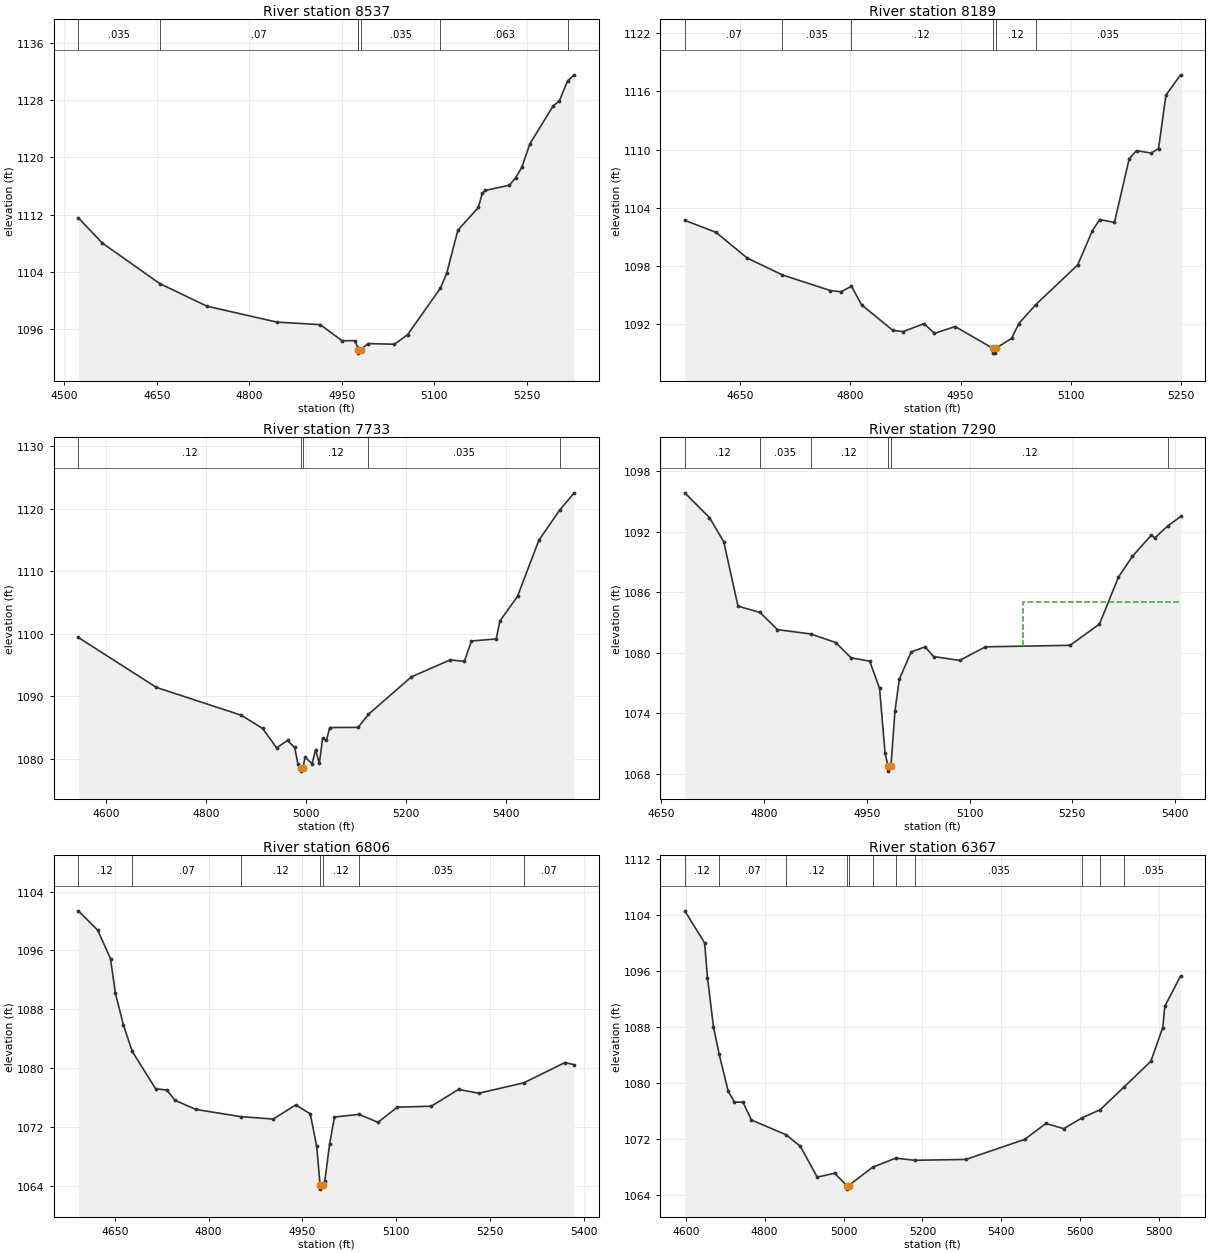
Type RM Length L Ch R = 1 ,8537    ,348,348,348
BEGIN DESCRIPTION:
Miller Tributary 1 19.0
END DESCRIPTION:
XS GIS Cut Line= 3
      2171663.74      13851761.4      2172105.59     13852195.01
      2172288.92     13852220.01
#Sta/Elev= 30
  4522.8 1111.56  4561.6 1108.05    4655 1102.38  4731.3 1099.24  4844.5 1097.02
  4915.2 1096.66  4950.5 1094.42  4971.8 1094.43  4975.7 1093.46  4975.8 1093.44
  4976.8 1093.19    4977 1092.69  4980.8 1093.19  4992.9 1094.02  5035.4 1093.93
  5056.7 1095.26  5109.9 1101.74  5120.2 1103.81  5138.3 1109.83  5171.6 1113.01
  5177.7 1114.97  5182.7 1115.38    5222 1116.11  5232.1 1117.16  5242.2 1118.65
  5255.1 1121.88  5292.7 1127.15  5302.8 1127.85  5316.3 1130.67  5326.9  1131.5
#Mann= 8 ,-1 , 0
  4522.8    .035       0    4655     .07       0  4975.7     .12       0
  4975.8    .035       0  4976.8    .035       0  4980.8    .035       0
  5109.9    .063       0  5316.3     .12       0
Bank Sta=4976.8,4980.8
XS Rating Curve= 0 ,0
Exp/Cntr=0.3,0.1

Type RM Length L Ch R = 1 ,8189    ,456,456,456
BEGIN DESCRIPTION:
Miller Tributary 1 18.0
END DESCRIPTION:
XS GIS Cut Line= 3
      2171624.97     13852074.97        2171925.       13852375.
        2172175.       13852375.
#Sta/Elev= 30
  4574.9 1102.71  4617.4 1101.47  4659.8 1098.82  4707.7 1097.08  4772.9 1095.47
  4787.1 1095.35  4801.6 1095.91  4815.4 1093.99  4857.8 1091.37  4871.9 1091.24
  4900.2 1092.06  4914.4 1091.06  4942.6 1091.76  4993.7 1089.52  4993.9 1089.02
  4997.4 1089.02  4997.7 1089.52  5019.2 1090.53  5029.2 1092.07  5052.3 1094.03
  5109.2 1098.11  5129.2 1101.64  5139.2 1102.79  5159.2 1102.49  5179.2 1109.04
  5189.2  1109.9  5209.2 1109.64  5219.2 1110.11  5229.2 1115.62  5249.2 1117.71
#Mann= 6 ,-1 , 0
  4574.9     .07       0  4707.7    .035       0  4801.6     .12       0
  4993.7     .05       0  4997.7     .12       0  5052.3    .035       0
Bank Sta=4993.7,4997.7
XS Rating Curve= 0 ,0
Exp/Cntr=0.3,0.1

Type RM Length L Ch R = 1 ,7733    ,443,443,443
BEGIN DESCRIPTION:
Miller Tributary 1 17.0
END DESCRIPTION:
XS GIS Cut Line= 3
      2171424.99     13852474.99        2171775.       13852775.
        2172175.       13853125.
#Sta/Elev= 30
    4544 1099.43  4700.4 1091.44  4870.5 1086.98  4912.8 1084.88  4940.8 1081.79
  4962.7 1082.95    4977 1081.83  4983.6 1079.22  4989.1 1078.55  4989.4 1078.05
  4993.4 1078.55  4997.9 1080.28  5012.1 1079.22  5018.8  1081.5  5026.4 1079.28
    5033 1083.31  5040.6 1082.98  5047.2 1085.02  5104.2 1085.05  5124.6 1087.13
  5210.5 1093.12  5288.3 1095.84  5316.8 1095.62    5331 1098.87  5380.4  1099.2
    5388 1102.09  5423.1 1106.01  5465.8 1114.98  5507.3 1119.78  5536.5 1122.57
#Mann= 5 ,-1 , 0
    4544     .12       0  4989.1     .05       0  4993.4     .12       0
  5124.6    .035       0  5507.3     .07       0
Bank Sta=4989.1,4993.4
XS Rating Curve= 0 ,0
Exp/Cntr=0.3,0.1

Type RM Length L Ch R = 1 ,7290    ,484,484,484
BEGIN DESCRIPTION:
Miller Tributary 1 16.0
END DESCRIPTION:
XS GIS Cut Line= 3
      2171225.03     13852875.02        2171475.       13853075.
      2171874.97       13853125.
#Sta/Elev= 30
  4684.7 1095.87  4720.7 1093.41  4741.5 1091.01  4762.3 1084.62  4794.5 1083.99
  4819.9 1082.29  4868.1 1081.86  4904.8 1081.01  4927.2 1079.49  4954.4 1079.16
  4968.8 1076.45  4976.8 1070.05  4981.1 1068.74  4981.3 1068.24  4985.4 1068.74
  4991.2 1074.19  4997.6 1077.37  5014.9 1080.07  5035.1 1080.58  5047.6 1079.62
  5085.4 1079.23  5123.2 1080.58  5246.7 1080.73  5289.5 1082.84  5317.2  1087.5
  5337.4 1089.55  5365.1 1091.67  5370.1 1091.39  5389.7 1092.61  5407.9 1093.52
#Mann= 6 ,-1 , 0
  4684.7     .12       0  4794.5    .035       0  4868.1     .12       0
  4981.1     .05       0  4985.4     .12       0  5389.7    .035       0
#XS Ineff= 2 , 0
       0                 5177.34       0 1085.08
Permanent Ineff=
       F       F
Bank Sta=4981.1,4985.4
XS Rating Curve= 0 ,0
Exp/Cntr=0.3,0.1

Type RM Length L Ch R = 1 ,6806    ,439,439,439
BEGIN DESCRIPTION:
Miller Tributary 1 15.0
END DESCRIPTION:
XS GIS Cut Line= 3
      2170975.05     13853425.01        2171375.       13853525.
      2171725.05     13853374.98
#Sta/Elev= 30
  4591.5  1101.4  4622.4 1098.77    4643 1094.88  4650.7 1090.21  4663.6 1085.86
  4677.8 1082.25  4715.1 1077.18  4733.2 1076.99  4746.1  1075.6  4779.6 1074.36
  4851.3 1073.38  4903.3 1073.05  4939.3 1074.98  4962.5 1073.76  4972.8 1069.32
  4978.3 1064.01  4978.6 1063.51  4982.8 1064.01  4985.7 1064.59  4993.5 1069.68
  5001.2 1073.33  5040.5 1073.69  5070.9 1072.61  5101.7 1074.67  5156.1  1074.8
  5199.6 1077.08  5232.2 1076.57  5304.3 1077.99    5370 1080.75  5384.6 1080.44
#Mann= 7 ,-1 , 0
  4591.5     .12       0  4677.8     .07       0  4851.3     .12       0
  4978.3     .05       0  4982.8     .12       0  5040.5    .035       0
  5304.3     .07       0
Bank Sta=4978.3,4982.8
XS Rating Curve= 0 ,0
Exp/Cntr=0.3,0.1

Type RM Length L Ch R = 1 ,6367    ,205,205,205
BEGIN DESCRIPTION:
Miller Tributary 1 14.0
END DESCRIPTION:
XS GIS Cut Line= 3
      2170825.04     13853675.02        2171175.       13853875.
      2171975.03     13853574.99
#Sta/Elev= 30
  4597.4 1104.64  4647.7 1100.05  4654.9 1095.09  4670.1 1088.09  4684.6 1084.15
  4707.5 1078.88  4723.3 1077.32  4744.9 1077.32  4766.5 1074.77  4854.2 1072.67
  4890.3 1071.02  4933.5 1066.61  4977.4 1067.18    5008  1065.4  5008.3  1064.9
  5012.6  1065.4  5073.8 1068.03  5132.3 1069.33  5180.2 1069.02  5310.2 1069.14
  5459.7 1072.01  5513.1 1074.28  5558.5 1073.54    5606 1075.11  5650.8 1076.24
  5712.4 1079.54  5779.2 1083.14  5809.5 1087.95  5814.8 1091.02  5854.9 1095.34
#Mann= 11 ,-1 , 0
  4597.4     .12       0  4684.6     .07       0  4854.2     .12       0
    5008     .05       0  5012.6     .12       0  5073.8    .035       0
  5132.3     .07       0  5180.2    .035       0    5606     .07       0
  5650.8     .12       0  5712.4    .035       0
Bank Sta=5008,5012.6
XS Rating Curve= 0 ,0
Exp/Cntr=0.3,0.1

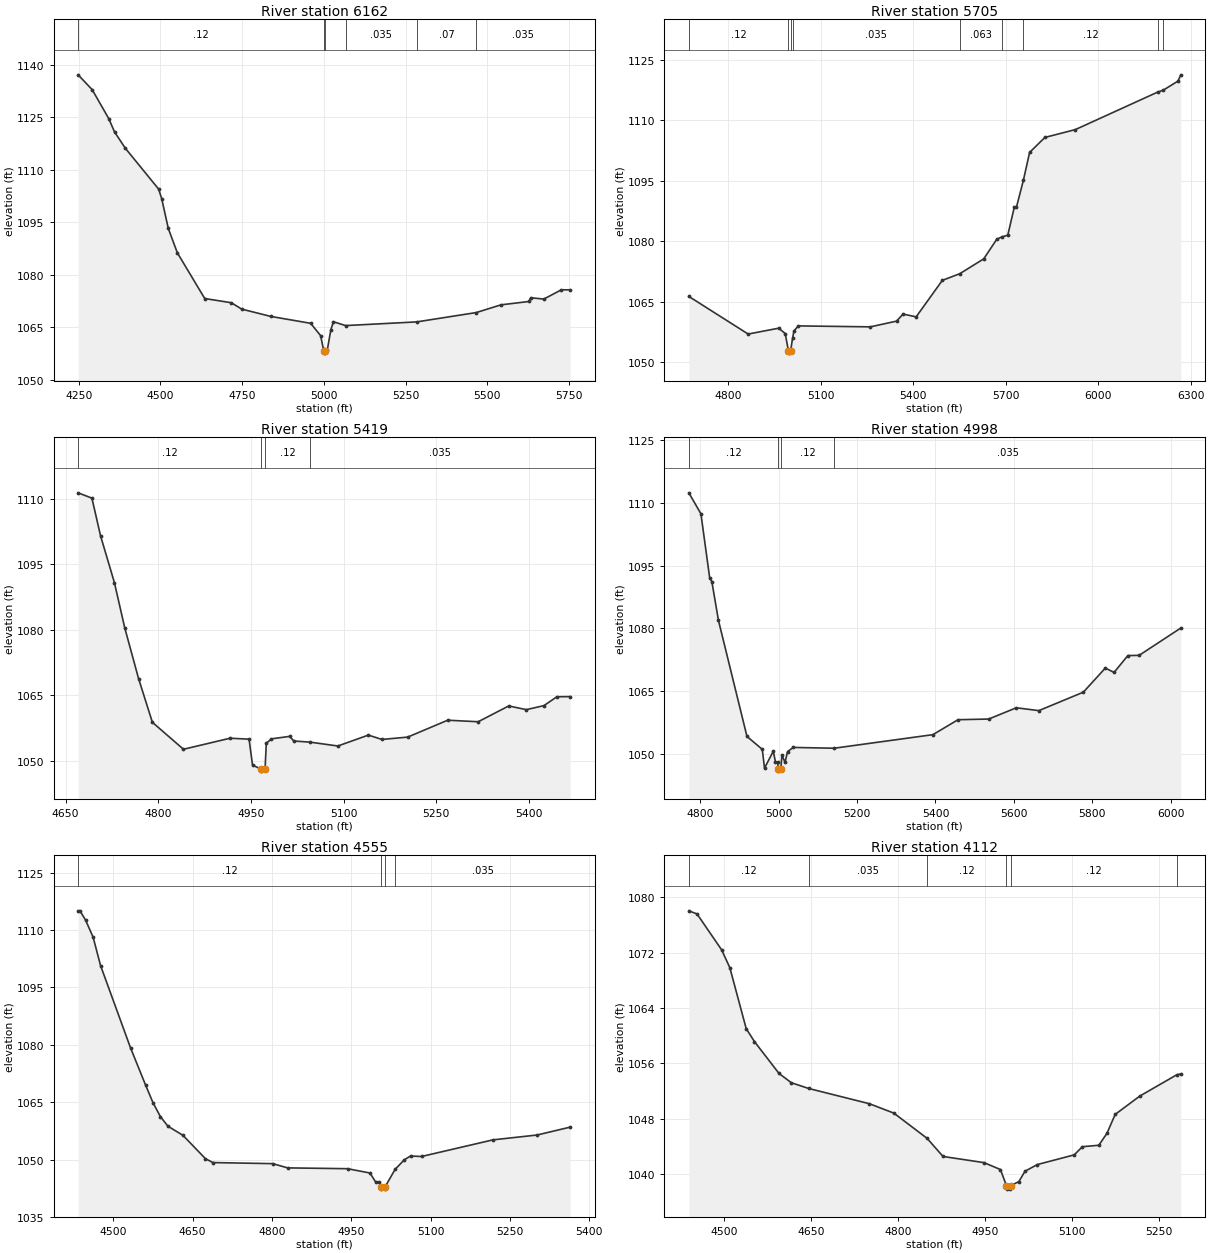
Type RM Length L Ch R = 1 ,6162    ,457,457,457
BEGIN DESCRIPTION:
Miller Tributary 1 13.0
END DESCRIPTION:
XS GIS Cut Line= 3
      2170432.56      13853962.2      2171177.78     13854080.16
      2171880.28     13853816.64
#Sta/Elev= 30
  4248.3 1137.15  4291.3  1132.9  4341.9 1124.64  4359.6 1120.82  4392.5 1116.17
  4494.4 1104.48  4503.9 1101.73  4524.1  1093.2  4551.7 1086.25  4635.5 1073.17
  4716.5 1071.97  4748.9 1070.13    4838 1068.04  4959.5 1066.08  4989.9 1062.56
    5000 1058.05  5000.3 1057.55  5004.6 1058.05  5010.5  1058.5  5021.2  1064.2
  5029.1 1066.53  5066.4 1065.43  5283.7 1066.48  5465.9 1069.15  5541.7 1071.36
  5627.1 1072.32  5632.5 1073.39  5672.7 1073.01  5726.1 1075.65  5753.1 1075.66
#Mann= 6 ,-1 , 0
  4248.3     .12       0    5000     .05       0  5004.6     .12       0
  5066.4    .035       0  5283.7     .07       0  5465.9    .035       0
Bank Sta=5000,5004.6
XS Rating Curve= 0 ,0
Exp/Cntr=0.3,0.1

Type RM Length L Ch R = 1 ,5705    ,286,286,286
BEGIN DESCRIPTION:
Miller Tributary 1 12.1
END DESCRIPTION:
XS GIS Cut Line= 3
      2170797.01     13854241.21       2171024.6     13854479.75
      2171912.58     13855380.57
#Sta/Elev= 30
    4673 1066.36  4865.2 1057.04  4964.3 1058.49  4985.4 1057.16  4995.9 1052.81
  4996.4 1052.31  5002.9 1052.81    5009 1055.94  5013.7 1057.81  5027.9 1059.06
  5261.3 1058.82  5346.2 1060.24  5367.3 1061.99  5409.7  1061.3  5494.6 1070.34
  5551.3    1072  5628.9 1075.68  5671.3 1080.56  5687.4  1081.1  5706.8 1081.55
  5727.9 1088.49    5735 1088.52  5757.3 1095.14  5777.5 1102.05  5826.9 1105.76
  5925.9 1107.71  6193.2 1117.02  6210.3 1117.46  6258.3 1119.72  6267.6 1121.28
#Mann= 9 ,-1 , 0
    4673     .12       0  4995.9     .05       0  5002.9     .12       0
    5009    .035       0  5551.3    .063       0  5687.4    .035       0
  5757.3     .12       0  6193.2     .07       0  6210.3     .12       0
Bank Sta=4995.9,5002.9
XS Rating Curve= 0 ,0
Exp/Cntr=0.3,0.1

Type RM Length L Ch R = 1 ,5419    ,421,421,421
BEGIN DESCRIPTION:
Miller Tributary 1 12.0
END DESCRIPTION:
XS GIS Cut Line= 3
      2170475.03     13854425.01        2170775.       13854575.
      2171125.03     13854875.03
#Sta/Elev= 30
  4670.3 1111.39  4692.6 1110.17  4706.6 1101.53    4729 1090.81  4745.7 1080.47
  4768.1 1068.82  4790.5 1058.79  4840.8 1052.61  4916.2 1055.14    4947 1054.93
  4952.6 1048.99  4965.8  1048.1  4966.3  1047.6  4972.9  1048.1  4974.9 1053.98
  4983.3    1055  5012.8 1055.57  5019.4  1054.5  5045.5 1054.25  5090.7 1053.36
  5140.1 1055.86  5162.1 1054.86  5203.8  1055.4  5268.5 1059.27  5317.9 1058.92
  5367.3 1062.54  5395.9 1061.69  5424.4 1062.62  5445.3 1064.65  5466.7 1064.68
#Mann= 4 ,-1 , 0
  4670.3     .12       0  4965.8     .05       0  4972.9     .12       0
  5045.5    .035       0
Bank Sta=4965.8,4972.9
XS Rating Curve= 0 ,0
Exp/Cntr=0.3,0.1

Type RM Length L Ch R = 1 ,4998    ,443,443,443
BEGIN DESCRIPTION:
Miller Tributary 1 11.0
END DESCRIPTION:
XS GIS Cut Line= 3
      2170324.98     13854524.96        2170425.       13854725.
      2171074.99     13855524.98
#Sta/Elev= 30
  4771.1 1112.39  4801.9 1107.38  4824.2  1092.1  4829.8 1091.17  4846.6 1081.92
  4919.3  1054.2  4958.4 1051.12    4964 1046.63  4986.4 1050.67    4992 1048.11
    4998 1048.11  4998.4 1046.42  4998.9 1045.92  5005.5 1046.42  5008.4 1049.73
  5016.3 1048.03  5022.7 1050.56  5037.1 1051.58  5141.5 1051.39  5393.4 1054.63
  5457.4  1058.2  5535.7 1058.36    5606 1061.05  5663.5 1060.37    5777 1064.78
    5833 1070.53  5855.3  1069.5  5890.5 1073.52  5919.2 1073.57  6025.5  1080.1
#Mann= 4 ,-1 , 0
  4771.1     .12       0  4998.4     .05       0  5005.5     .12       0
  5141.5    .035       0
Bank Sta=4998.4,5005.5
XS Rating Curve= 0 ,0
Exp/Cntr=0.3,0.1

Type RM Length L Ch R = 1 ,4555    ,443,443,443
BEGIN DESCRIPTION:
Miller Tributary 1 10.0
END DESCRIPTION:
XS GIS Cut Line= 3
        2169975.       13854725.        2170375.       13855125.
      2170725.01       13855225.
#Sta/Elev= 30
  4433.8    1115  4437.3    1115  4447.9 1112.56  4462.1 1108.11  4476.2 1100.68
  4532.8 1079.19  4561.1 1069.52  4575.2 1064.87  4589.4 1061.19  4603.5 1058.71
  4631.8 1056.34  4674.2 1050.25  4688.4 1049.21  4801.5 1048.93  4829.8 1047.82
  4942.9 1047.61  4985.3 1046.48  4995.9 1044.16  5002.1 1044.16  5006.3 1042.77
  5006.8 1042.27    5013 1042.27  5013.5 1042.77  5032.7 1047.42  5050.2 1049.94
  5061.9 1050.92  5082.7  1050.8  5217.9 1055.15  5301.1 1056.41  5363.5 1058.47
#Mann= 4 ,-1 , 0
  4433.8     .12       0  5006.3     .05       0  5013.5     .12       0
  5032.7    .035       0
Bank Sta=5006.3,5013.5
XS Rating Curve= 0 ,0
Exp/Cntr=0.3,0.1

Type RM Length L Ch R = 1 ,4112    ,572,572,572
BEGIN DESCRIPTION:
Miller Tributary 1 9.0
END DESCRIPTION:
XS GIS Cut Line= 3
      2169775.03     13855075.03        2170175.       13855475.
      2170375.01     13855675.01
#Sta/Elev= 30
  4438.9 1078.06    4453 1077.61  4495.4 1072.43  4509.6 1069.84  4537.8 1061.04
    4552 1059.17  4594.4 1054.56  4615.6 1053.22  4645.4 1052.39    4750 1050.19
  4792.4 1048.83  4849.8 1045.18  4877.3 1042.56    4948 1041.67  4976.3 1040.67
  4986.7 1038.34  4987.2 1037.84  4993.6 1037.84  4994.1 1038.34  5008.1 1038.93
  5018.7 1040.43  5039.9 1041.39  5103.5 1042.79  5117.7 1043.97    5146 1044.18
  5160.1 1045.92  5174.2 1048.64  5216.7 1051.29  5280.3 1054.36  5287.4 1054.49
#Mann= 6 ,-1 , 0
  4438.9     .12       0  4645.4    .035       0  4849.8     .12       0
  4986.7     .05       0  4994.1     .12       0  5280.3    .035       0
Bank Sta=4986.7,4994.1
XS Rating Curve= 0 ,0
Exp/Cntr=0.3,0.1

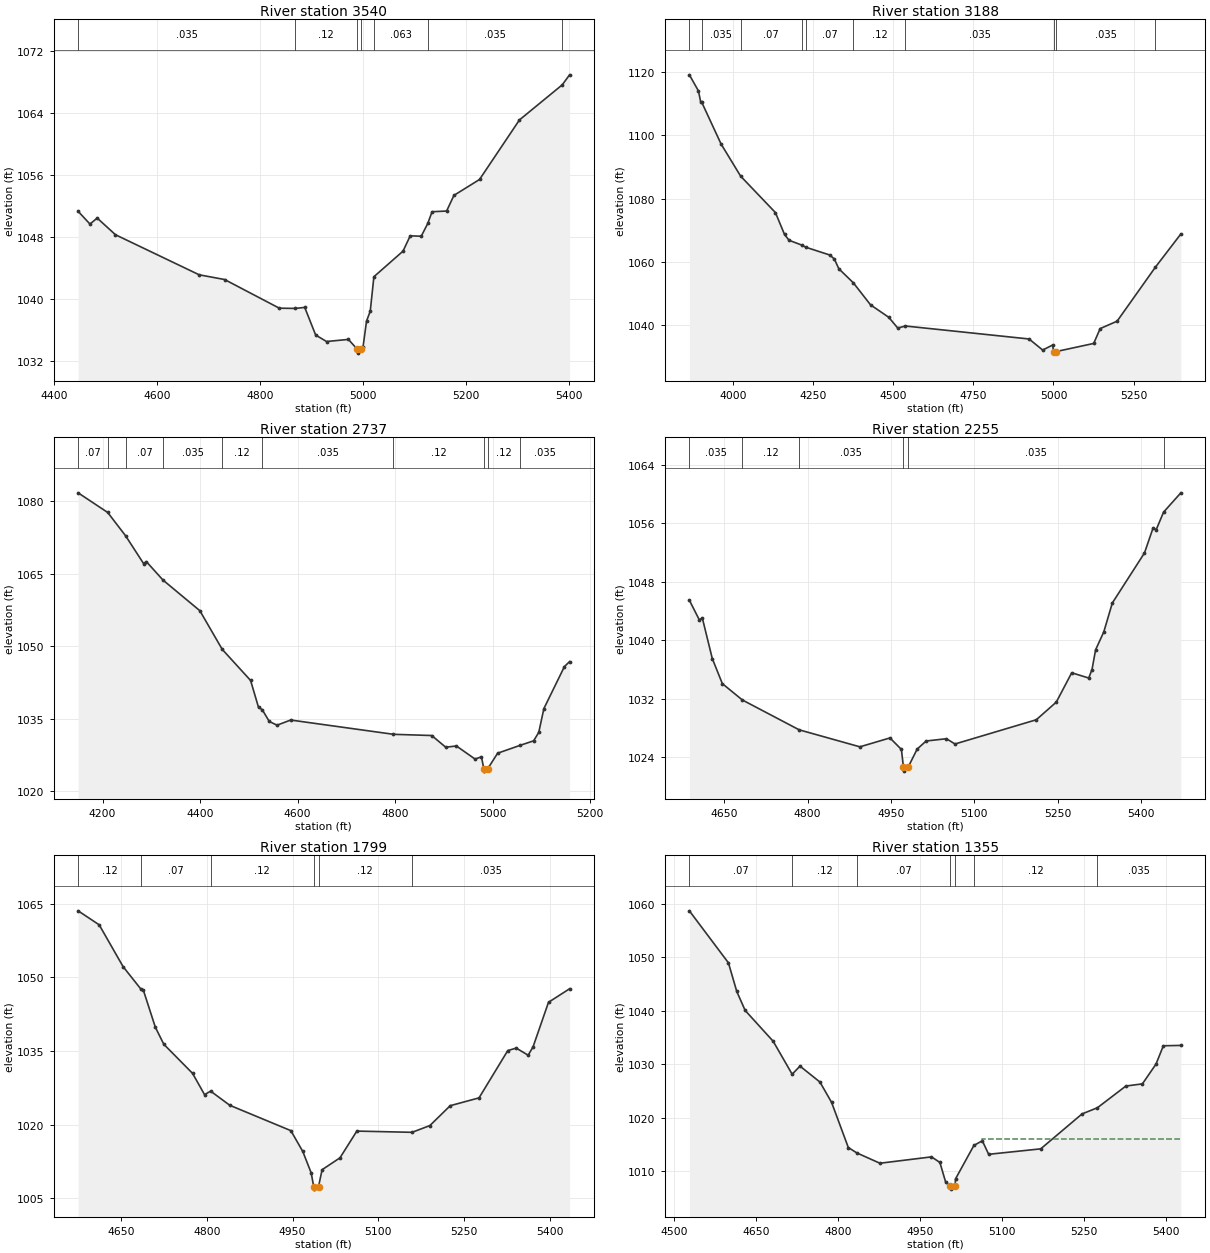
Type RM Length L Ch R = 1 ,3540    ,352,352,352
BEGIN DESCRIPTION:
Miller Tributary 1 8.0
END DESCRIPTION:
XS GIS Cut Line= 2
      2169655.15     13855562.31      2170317.75     13856249.91
#Sta/Elev= 30
  4446.1 1051.27  4469.1 1049.62  4483.2 1050.39  4518.7 1048.24  4681.3 1043.07
  4730.7 1042.46    4837 1038.76  4867.8 1038.73  4886.4 1038.86  4907.7 1035.29
  4928.8 1034.46  4971.3 1034.73  4988.5 1033.46    4989 1032.96  4996.3 1033.46
  4999.6 1033.71  5006.5  1037.1  5013.7 1038.37  5020.8 1042.82  5077.3 1046.12
  5091.4  1048.1  5112.8 1048.05  5125.5  1049.7  5133.8 1051.21  5162.1  1051.3
  5176.3 1053.32    5226 1055.37  5303.6 1063.06  5386.8 1067.59    5401 1068.88
#Mann= 7 ,-1 , 0
  4446.1    .035       0  4867.8     .12       0  4988.5     .05       0
  4996.3     .12       0  5020.8    .063       0  5125.5    .035       0
  5386.8    .063       0
Bank Sta=4988.5,4996.3
XS Rating Curve= 0 ,0
Exp/Cntr=0.3,0.1

Type RM Length L Ch R = 1 ,3188    ,451,451,451
BEGIN DESCRIPTION:
Miller Tributary 1 7.0
END DESCRIPTION:
XS GIS Cut Line= 3
      2168974.98     13855374.98        2169775.       13856175.
        2169725.     13856574.99
#Sta/Elev= 30
  3863.2 1119.18  3891.5 1114.08  3898.6 1110.54  3901.7 1110.51  3962.2 1097.26
  4023.2 1087.09  4131.9 1075.54  4160.2 1068.63  4174.4 1066.77  4213.4 1065.27
  4226.5 1064.57  4301.6  1062.1  4315.8 1060.84  4329.9 1057.74  4375.3 1053.28
  4428.9 1046.31  4485.5 1042.39  4513.8 1038.97  4537.9 1039.61  4923.9  1035.5
  4966.3    1032  4997.1 1033.57  5000.7 1031.52  5001.2 1031.02  5008.6 1031.52
  5125.6 1034.09  5145.8 1038.79  5198.7 1041.14  5317.9  1058.2  5397.7 1068.76
#Mann= 10 ,-1 , 0
  3863.2     .07       0  3901.7    .035       0  4023.2     .07       0
  4213.4    .035       0  4226.5     .07       0  4375.3     .12       0
  4537.9    .035       0  5000.7    .035       0  5008.6    .035       0
  5317.9     .12       0
Bank Sta=5000.7,5008.6
XS Rating Curve= 0 ,0
Exp/Cntr=0.3,0.1

Type RM Length L Ch R = 1 ,2737    ,482,482,482
BEGIN DESCRIPTION:
Miller Tributary 1 6.0
END DESCRIPTION:
XS GIS Cut Line= 3
        2168975.     13855574.99        2169375.       13856325.
      2169424.99     13856474.98
#Sta/Elev= 30
  4149.9 1081.78  4210.6 1077.71  4247.4 1072.86  4284.1 1067.13  4289.8 1067.53
    4324  1063.7  4399.6 1057.35  4445.5 1049.34  4503.7 1042.89    4520  1037.3
  4527.4 1036.86    4542  1034.4  4557.9 1033.62  4585.9 1034.69  4796.8 1031.73
  4875.2 1031.48  4903.9 1029.06  4925.9 1029.31  4964.1  1026.6  4977.2 1027.07
  4982.1  1024.6  4982.6  1024.1  4990.1  1024.6  5010.4 1027.81  5056.1 1029.43
  5084.2 1030.38  5094.8 1032.13  5105.3 1037.07  5147.5 1045.78    5158  1046.8
#Mann= 10 ,-1 , 0
  4149.9     .07       0  4210.6    .035       0  4247.4     .07       0
    4324    .035       0  4445.5     .12       0  4527.4    .035       0
  4796.8     .12       0  4982.1     .05       0  4990.1     .12       0
  5056.1    .035       0
Bank Sta=4982.1,4990.1
XS Rating Curve= 0 ,0
Exp/Cntr=0.3,0.1

Type RM Length L Ch R = 1 ,2255    ,456,456,456
BEGIN DESCRIPTION:
Miller Tributary 1 5.0
END DESCRIPTION:
XS GIS Cut Line= 3
        2168825.       13855925.        2168925.       13856325.
      2169174.99     13856724.99
#Sta/Elev= 30
  4587.3 1045.47  4605.3 1042.76  4610.5 1043.06  4628.5 1037.48  4646.6 1034.04
  4682.6  1031.8  4784.8 1027.71    4894 1025.38  4948.1  1026.6  4968.7 1025.02
  4972.4 1022.55  4972.9 1022.05  4980.5 1022.55    4997 1025.07  5013.2 1026.18
  5049.7 1026.49  5065.1 1025.77  5211.3 1029.09  5247.3 1031.51    5275 1035.53
  5305.6 1034.81  5311.5 1035.97    5318 1038.68  5332.7 1041.13  5348.1  1045.1
  5405.9 1051.95  5421.2 1055.34  5427.1 1055.16  5440.3 1057.55  5471.3 1060.19
#Mann= 6 ,-1 , 0
  4587.3    .035       0  4682.6     .12       0  4784.8    .035       0
  4972.4    .035       0  4980.5    .035       0  5440.3     .12       0
Bank Sta=4972.4,4980.5
XS Rating Curve= 0 ,0
Exp/Cntr=0.3,0.1

Type RM Length L Ch R = 1 ,1799    ,444,444,444
BEGIN DESCRIPTION:
Miller Tributary 1 4.0
END DESCRIPTION:
XS GIS Cut Line= 3
      2168274.97     13856124.96        2168525.       13856475.
      2168775.01     13856825.02
#Sta/Elev= 30
  4574.6 1063.52  4611.5 1060.67  4653.3 1052.17  4684.4 1047.61  4688.9 1047.34
  4709.8 1039.83  4724.6 1036.37    4775 1030.44  4795.9 1026.12  4806.6 1026.83
  4840.1 1023.95    4947 1018.79  4967.9 1014.55  4982.6 1010.19    4987 1007.39
  4987.5 1006.89  4995.4 1007.39  5001.7 1010.84    5033 1013.26  5062.5  1018.7
  5159.2 1018.45  5190.3 1019.82    5226 1023.87  5276.4 1025.46  5326.7 1035.08
  5341.5 1035.59  5362.4 1034.14    5371 1035.85    5398 1044.91  5434.9 1047.66
#Mann= 6 ,-1 , 0
  4574.6     .12       0  4684.4     .07       0  4806.6     .12       0
    4987     .05       0  4995.4     .12       0  5159.2    .035       0
Bank Sta=4987,4995.4
XS Rating Curve= 0 ,0
Exp/Cntr=0.3,0.1

Type RM Length L Ch R = 1 ,1355    ,514,514,514
BEGIN DESCRIPTION:
Miller Tributary 1 3.0
END DESCRIPTION:
XS GIS Cut Line= 3
      2167924.99     13856324.98        2168175.       13856725.
      2168574.98     13856874.99
#Sta/Elev= 30
  4528.5 1058.72  4599.9    1049  4615.2 1043.64  4630.5  1040.1  4681.8 1034.33
  4716.5 1028.17  4730.8 1029.69  4767.3 1026.71  4788.5 1022.93  4819.2 1014.47
  4834.8 1013.46    4877 1011.53  4971.3 1012.72  4986.7 1011.68  4997.3 1007.98
  5005.8 1007.19  5006.3 1006.69  5014.2 1007.19  5015.3 1008.61  5048.9 1014.86
  5064.3 1015.73  5075.9  1013.2  5171.1 1014.22  5246.7 1020.75  5274.9 1021.91
  5326.8 1025.96  5357.1 1026.37    5382 1030.07  5395.4 1033.49  5427.4 1033.56
#Mann= 7 ,-1 , 0
  4528.5     .07       0  4716.5     .12       0  4834.8     .07       0
  5005.8     .05       0  5014.2     .07       0  5048.9     .12       0
  5274.9    .035       0
#XS Ineff= 2 , 0
       0                 5063.73       0 1015.99
Permanent Ineff=
       F       F
Bank Sta=5005.8,5014.2
XS Rating Curve= 0 ,0
Exp/Cntr=0.3,0.1

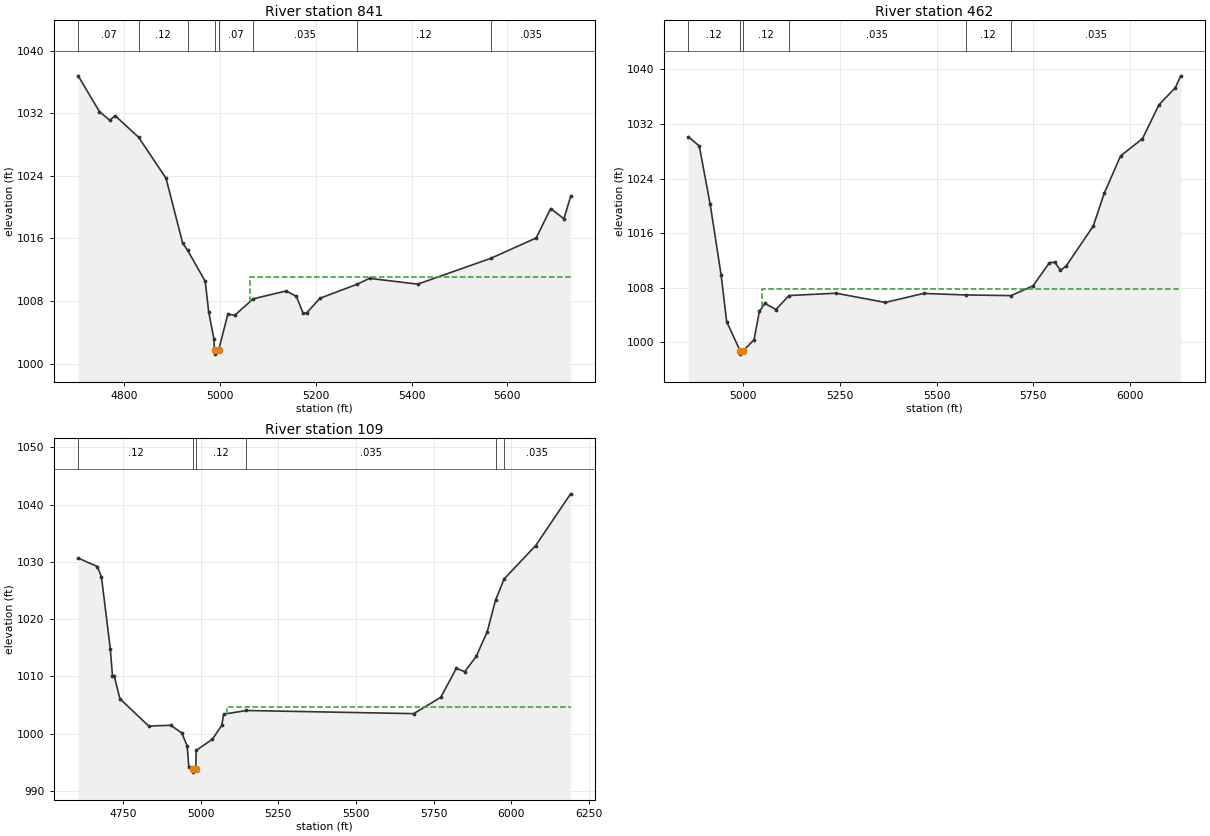
Type RM Length L Ch R = 1 ,841     ,379,379,379
BEGIN DESCRIPTION:
Miller Tributary 1 2.0
END DESCRIPTION:
XS GIS Cut Line= 3
      2167617.25     13856554.12      2167779.79     13856937.55
      2168300.39     13857258.24
#Sta/Elev= 30
  4704.1 1036.77  4748.5  1032.2  4770.2 1031.08  4781.1 1031.69  4830.3 1028.92
  4887.4  1023.7  4922.3 1015.39  4932.5 1014.49  4969.3 1010.52  4976.6  1006.6
  4987.4 1003.19  4988.7 1001.72  4989.2 1001.22  4997.2 1001.72  5016.6 1006.33
  5030.9 1006.18  5069.7 1008.29  5138.4 1009.29  5159.7 1008.59  5173.7 1006.43
    5181 1006.48  5208.9 1008.36  5285.6 1010.13  5312.3  1010.9  5412.8 1010.16
  5565.6 1013.46  5660.1 1016.06  5690.4 1019.82    5718 1018.51    5732 1021.36
#Mann= 8 ,-1 , 0
  4704.1     .07       0  4830.3     .12       0  4932.5     .07       0
  4988.7     .05       0  4997.2     .07       0  5069.7    .035       0
  5285.6     .12       0  5565.6    .035       0
#XS Ineff= 2 , 0
       0                    5063       0  1011.1
Permanent Ineff=
       F       F
Bank Sta=4988.7,4997.2
XS Rating Curve= 0 ,0
Exp/Cntr=0.3,0.1

Type RM Length L Ch R = 1 ,462     ,353,353,353
BEGIN DESCRIPTION:
Miller Tributary 1 1.0
END DESCRIPTION:
XS GIS Cut Line= 3
      2167375.02     13856975.02        2167475.       13857075.
      2168275.03     13857875.03
#Sta/Elev= 30
  4858.4 1030.13  4886.7 1028.77  4914.9 1020.22  4943.2 1009.84  4957.4 1003.06
    4992  998.79  4992.5  998.29  5000.5  998.79  5028.1 1000.39  5042.2 1004.58
  5056.4 1005.72  5084.6 1004.82  5118.6 1006.87  5240.2 1007.21  5367.5 1005.86
  5466.5 1007.18  5574.9 1006.96  5692.5 1006.86  5749.3 1008.29  5791.8 1011.69
  5805.9 1011.73    5820 1010.58  5834.2 1011.14  5904.9 1017.04  5933.2 1021.83
  5975.6 1027.32  6032.2 1029.85  6074.6  1034.8    6117 1037.31  6131.2 1039.05
#Mann= 6 ,-1 , 0
  4858.4     .12       0    4992     .05       0  5000.5     .12       0
  5118.6    .035       0  5574.9     .12       0  5692.5    .035       0
#XS Ineff= 2 , 0
       0                    5050       0 1007.77
Permanent Ineff=
       F       F
Bank Sta=4992,5000.5
XS Rating Curve= 0 ,0
Exp/Cntr=0.3,0.1

Type RM Length L Ch R = 1 ,109     ,0,0,0
BEGIN DESCRIPTION:
Miller Tributary 1 0.0
END DESCRIPTION:
XS GIS Cut Line= 5
      2167287.95     13856954.84      2167219.67     13857221.09
      2167266.71     13857330.98      2167660.23     13857580.46
      2168236.55     13858020.25
#Sta/Elev= 30
  4605.6 1030.66  4667.7 1029.19  4680.5  1027.4    4709 1014.85  4716.1 1010.09
  4721.3 1010.16    4740 1006.11  4832.9 1001.34  4903.9 1001.48  4939.1 1000.14
  4956.5  997.88  4961.9  994.17  4975.8   993.8  4976.3   993.3  4984.3   993.8
  4985.5  997.09  5037.5  999.03    5068 1001.49  5073.9 1003.41  5147.4 1004.06
  5685.8 1003.51    5773 1006.36  5822.9 1011.42    5850 1010.84    5887 1013.49
  5922.6 1017.84  5949.3 1023.33  5976.8 1027.02  6078.6 1032.86  6190.9 1041.88
#Mann= 6 ,-1 , 0
  4605.6     .12       0  4975.8     .05       0  4984.3     .12       0
  5147.4    .035       0  5949.3     .07       0  5976.8    .035       0
#XS Ineff= 2 , 0
       0                 5085.36       0 1004.73
Permanent Ineff=
       F       F
Bank Sta=4975.8,4984.3
XS Rating Curve= 0 ,0
Exp/Cntr=0.3,0.1

Chan Stop Cuts=-1
Use User Specified Reach Order=0
Composite Channel Slope=5