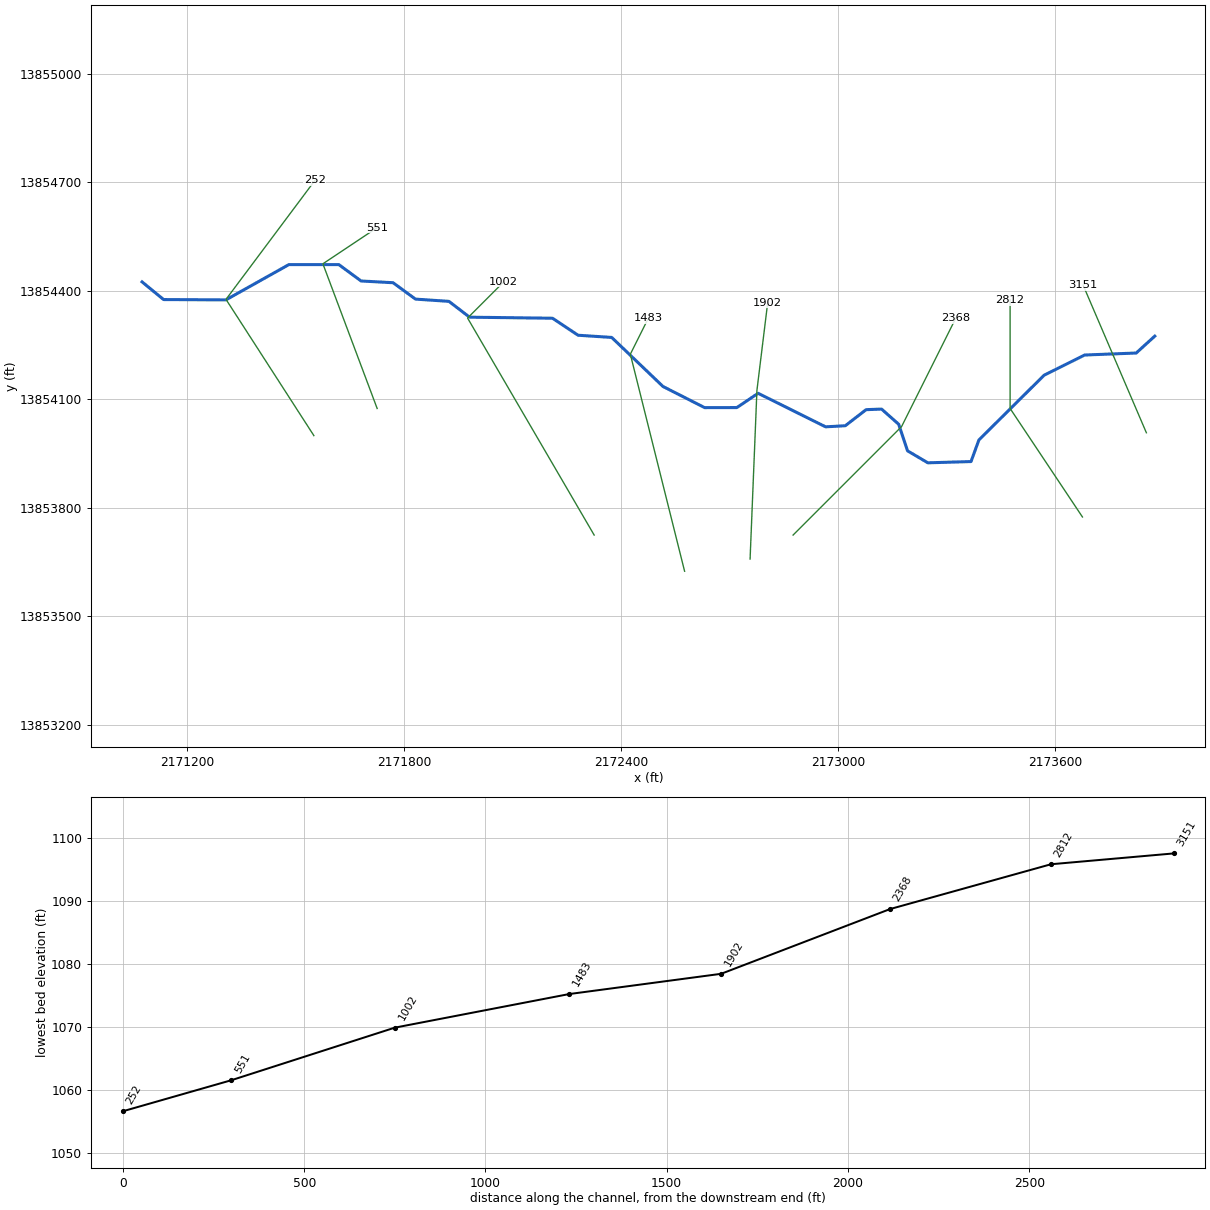
--- Miller Tributary 2.prj (project) ---

Proj Title=Miller Tributary 2 Base Level Engineering
Current Plan=p01
Default Exp/Contr=0.3,0.1
English Units
Geom File=g01
Flow File=f01
Plan File=p01
BEGIN DESCRIPTION:
Miller Tributary 2
END DESCRIPTION:

--- Miller Tributary 2.p01 (plan) ---

Plan Title=Multiple Run
Short Identifier=Multiple
Geom File=g01
Flow File=f01
Subcritical Flow
K Sum by GR= 0
Std Step Tol= 0.01
Critical Tol= 0.01
Num of Std Step Trials= 20
Max Error Tol= 0.3
Flow Tol Ratio= 0.001
Split Flow NTrial= 30
Split Flow Tol= 0.02
Split Flow Ratio= 0.02
Log Output Level= 0
Friction Slope Method= 1
Unsteady Friction Slope Method= 2
Unsteady Bridges Friction Slope Method= 1
Parabolic Critical Depth
Global Vel Dist=  1 , 1 , 1
Global Log Level= 0
CheckData=True
Encroach Param= -1, 0, 0, 0
BEGIN DESCRIPTION:
Multiple Run
END DESCRIPTION:

--- Miller Tributary 2.f01 (steady flow) ---

Flow Title=Multiple
Number of Profiles=7
Profile Names=10-year,25-year,50-year,1pct_min,100-year,1pct_plu,500-year
River Rch & RM= Miller Tributary,Reach-1,3151
    1174    2007    2805    1900    3790    7562    6850
Boundary for River Rch & Prof#=Miller Tributary,Reach-1,1
Up Type=0
Dn Type=3
Dn Slope=0.005
Boundary for River Rch & Prof#=Miller Tributary,Reach-1,2
Up Type=0
Dn Type=3
Dn Slope=0.005
Boundary for River Rch & Prof#=Miller Tributary,Reach-1,3
Up Type=0
Dn Type=3
Dn Slope=0.005
Boundary for River Rch & Prof#=Miller Tributary,Reach-1,4
Up Type=0
Dn Type=3
Dn Slope=0.005
Boundary for River Rch & Prof#=Miller Tributary,Reach-1,5
Up Type=0
Dn Type=3
Dn Slope=0.005
Boundary for River Rch & Prof#=Miller Tributary,Reach-1,6
Up Type=0
Dn Type=3
Dn Slope=0.005
Boundary for River Rch & Prof#=Miller Tributary,Reach-1,7
Up Type=0
Dn Type=3
Dn Slope=0.005

--- Miller Tributary 2.g01 (geometry) ---

Geom Title=Existing Conditions

River Reach=Miller Tributary,Reach-1
Reach XY= 30
      2173875.00     13854275.00      2173823.63     13854228.30
      2173680.93     13854222.76      2173568.94     13854166.86
      2173388.74     13853987.95      2173366.99     13853928.22
      2173247.58     13853924.73      2173191.46     13853957.87
      2173166.95     13854031.41      2173119.56     13854073.34
      2173076.78     13854071.67      2173019.44     13854027.31
      2172964.95     13854024.22      2172778.32     13854116.95
      2172719.51     13854077.49      2172630.56     13854077.26
      2172515.32     13854135.76      2172373.50     13854271.39
      2172280.57     13854277.47      2172209.78     13854324.48
      2171980.53     13854327.38      2171923.40     13854371.14
      2171830.97     13854377.35      2171769.03     13854422.65
      2171680.57     13854427.47      2171619.06     13854472.75
      2171480.93     13854472.77      2171306.74     13854375.20
      2171134.55     13854376.10      2171075.00     13854425.00

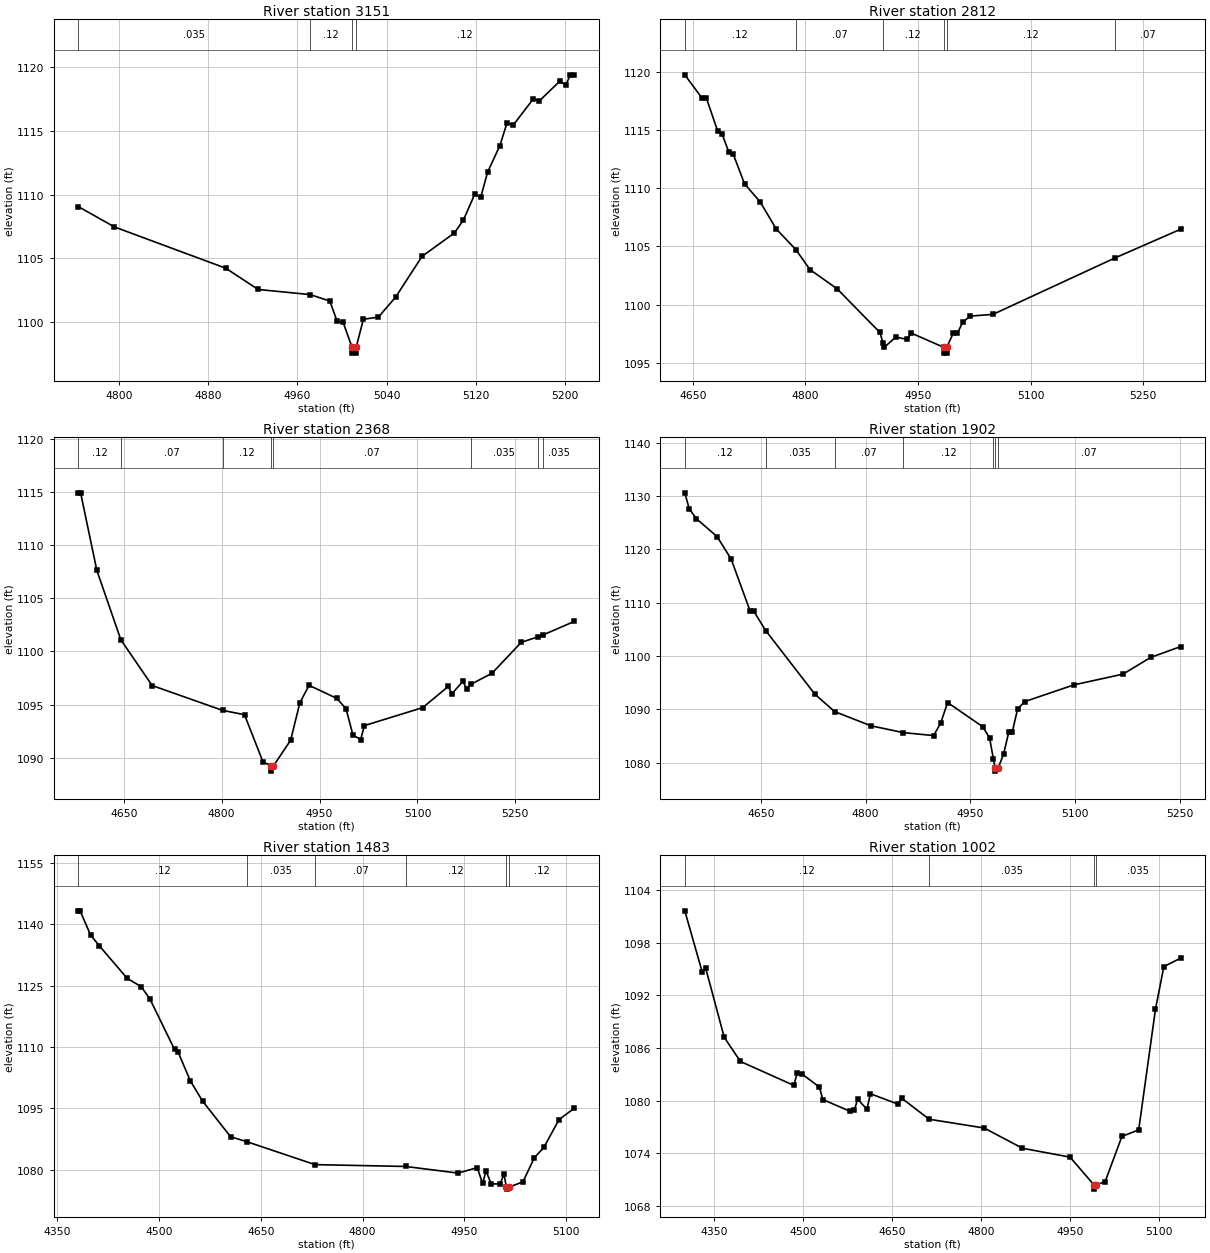
Type RM Length L Ch R = 1,3151,339,339,339
BEGIN DESCRIPTION:
Miller Tributary 2 7.0
END DESCRIPTION:
XS GIS Cut Line= 2
      2173851.75     13854007.85      2173676.73     13854416.22
#Sta/Elev= 30
  4763.8 1109.06  4796.2 1107.46  4895.9 1104.22  4924.9 1102.55  4971.4 1102.15
  4989.2 1101.64  4995.7 1100.04  5001.1 1099.96  5008.9 1098.05  5009.2 1097.55
  5012.7 1097.55  5012.9 1098.05  5019.2 1100.21  5032.7 1100.38  5048.2 1101.96
  5071.8 1105.15  5100.8 1106.99  5108.9 1108.01  5119.0 1110.03  5124.4 1109.80
  5130.6 1111.78  5141.5 1113.84  5148.0 1115.65  5153.4 1115.45  5171.5 1117.52
  5177.0 1117.37  5195.1 1118.90  5200.6 1118.61  5204.7 1119.41  5208.1 1119.41
#Mann=4,-1,0
  4763.8   0.035       0  4971.4    0.12       0  5008.9    0.05       0
  5012.9    0.12       0
Bank Sta=5008.9,5012.9
Exp/Cntr=0.3,0.1

Type RM Length L Ch R = 1,2812,444,444,444
BEGIN DESCRIPTION:
Miller Tributary 2 6.0
END DESCRIPTION:
XS GIS Cut Line= 3
      2173675.00     13853775.00      2173475.00     13854075.00
      2173475.00     13854375.04
#Sta/Elev= 30
  4639.4 1119.73  4661.9 1117.77  4667.9 1117.78  4683.0 1114.94  4689.0 1114.66
  4698.0 1113.10  4704.0 1112.91  4719.0 1110.37  4740.1 1108.79  4761.1 1106.50
  4787.4 1104.72  4806.2 1103.00  4842.2 1101.36  4899.3 1097.61  4903.4 1096.74
  4905.3 1096.34  4920.3 1097.20  4935.4 1097.02  4941.4 1097.54  4984.4 1096.33
  4984.7 1095.83  4988.2 1095.83  4988.4 1096.33  4997.0 1097.53  5002.5 1097.53
  5010.0 1098.52  5020.0 1099.01  5050.0 1099.16  5213.1 1104.02  5300.0 1106.47
#Mann=6,-1,0
  4639.4    0.12       0  4787.4    0.07       0  4903.4    0.12       0
  4984.4    0.05       0  4988.4    0.12       0  5213.1    0.07       0
Bank Sta=4984.4,4988.4
Exp/Cntr=0.3,0.1

Type RM Length L Ch R = 1,2368,466,466,466
BEGIN DESCRIPTION:
Miller Tributary 2 5.0
END DESCRIPTION:
XS GIS Cut Line= 3
      2172875.00     13853725.00      2173175.00     13854025.00
      2173325.01     13854325.03
#Sta/Elev= 30
  4580.4 1114.96  4583.9 1114.96  4608.7 1107.66  4645.5 1101.11  4693.5 1096.79
  4801.3 1094.45  4835.0 1094.04  4863.2 1089.61  4875.4 1089.22  4875.6 1088.72
  4879.4 1089.22  4905.7 1091.63  4919.8 1095.16  4933.9 1096.81  4976.4 1095.58
  4990.5 1094.61  5001.1 1092.14  5013.0 1091.69  5018.6 1093.01  5108.1 1094.71
  5147.2 1096.70  5152.8 1096.01  5169.6 1097.19  5175.2 1096.49  5181.4 1096.89
  5214.3 1097.95  5259.0 1100.86  5284.0 1101.37  5293.1 1101.58  5340.1 1102.83
#Mann=8,-1,0
  4580.4    0.12       0  4645.5    0.07       0  4801.3    0.12       0
  4875.4    0.05       0  4879.4    0.07       0  5181.4   0.035       0
  5284.0    0.07       0  5293.1   0.035       0
Bank Sta=4875.4,4879.4
Exp/Cntr=0.3,0.1

Type RM Length L Ch R = 1,1902,419,419,419
BEGIN DESCRIPTION:
Miller Tributary 2 4.0
END DESCRIPTION:
XS GIS Cut Line= 3
      2172756.11     13853658.69      2172775.00     13854125.00
      2172804.72     13854366.99
#Sta/Elev= 30
  4540.9 1130.58  4547.2 1127.61  4557.2 1125.76  4587.2 1122.38  4607.3 1118.17
  4634.7 1108.37  4639.7 1108.42  4656.9 1104.76  4727.4 1092.85  4755.5 1089.61
  4807.4 1086.95  4854.1 1085.66  4897.5 1085.11  4907.5 1087.43  4917.5 1091.30
  4967.6 1086.79  4977.6 1084.70  4983.1 1080.75  4985.6 1078.95  4985.8 1078.45
  4989.6 1078.95  4997.6 1081.58  5005.1 1085.74  5010.1 1085.74  5017.7 1090.05
  5027.7 1091.46  5098.3 1094.60  5168.8 1096.62  5208.4 1099.74  5251.4 1101.78
#Mann=7,-1,0
  4540.9    0.12       0  4656.9   0.035       0  4755.5    0.07       0
  4854.1    0.12       0  4983.1    0.07       0  4985.6    0.05       0
  4989.6    0.07       0
Bank Sta=4985.6,4989.6
Exp/Cntr=0.3,0.1

Type RM Length L Ch R = 1,1483,481,481,481
BEGIN DESCRIPTION:
Miller Tributary 2 3.0
END DESCRIPTION:
XS GIS Cut Line= 3
      2172575.00     13853625.02      2172425.00     13854225.00
      2172474.98     13854324.96
#Sta/Elev= 30
  4381.3 1143.28  4383.9 1143.28  4399.3 1137.38  4412.2 1134.73  4453.4 1126.75
  4474.0 1124.73  4486.9 1121.67  4523.0 1109.38  4528.2 1108.76  4546.2 1101.73
  4564.2 1096.78  4605.5 1088.05  4629.2 1086.85  4729.9 1081.23  4863.5 1080.78
  4940.5 1079.16  4968.8 1080.49  4976.6 1076.64  4981.7 1079.66  4989.4 1076.50
  5002.5 1076.53  5008.1 1078.93  5011.7 1075.74  5012.0 1075.24  5015.7 1075.74
  5036.1 1077.02  5052.9 1082.92  5066.8 1085.42  5089.2 1092.24  5111.5 1094.99
#Mann=6,-1,0
  4381.3    0.12       0  4629.2   0.035       0  4729.9    0.07       0
  4863.5    0.12       0  5011.7    0.05       0  5015.7    0.12       0
Bank Sta=5011.7,5015.7
Exp/Cntr=0.3,0.1

Type RM Length L Ch R = 1,1002,451,451,451
BEGIN DESCRIPTION:
Miller Tributary 2 2.0
END DESCRIPTION:
XS GIS Cut Line= 3
      2172324.98     13853725.04      2171975.00     13854325.00
      2172075.00     13854425.00
#Sta/Elev= 30
  4300.9 1101.65  4330.2 1094.69  4336.0 1095.14  4367.4 1087.22  4394.7 1084.47
  4484.8 1081.74  4490.6 1083.21  4497.7 1083.08  4527.8 1081.55  4533.6 1080.13
  4578.7 1078.81  4586.6 1078.89  4592.3 1080.16  4608.1 1079.02  4613.8 1080.79
  4659.7 1079.62  4666.8 1080.27  4712.9 1077.88  4805.7 1076.88  4870.2 1074.57
  4950.4 1073.56  4990.6 1070.41  4990.8 1069.91  4994.6 1070.41  5009.6 1070.76
  5037.9 1075.92  5066.2 1076.67  5094.5 1090.43  5108.6 1095.29  5136.9 1096.25
#Mann=4,-1,0
  4300.9    0.12       0  4712.9   0.035       0  4990.6   0.035       0
  4994.6   0.035       0
Bank Sta=4990.6,4994.6
Exp/Cntr=0.3,0.1

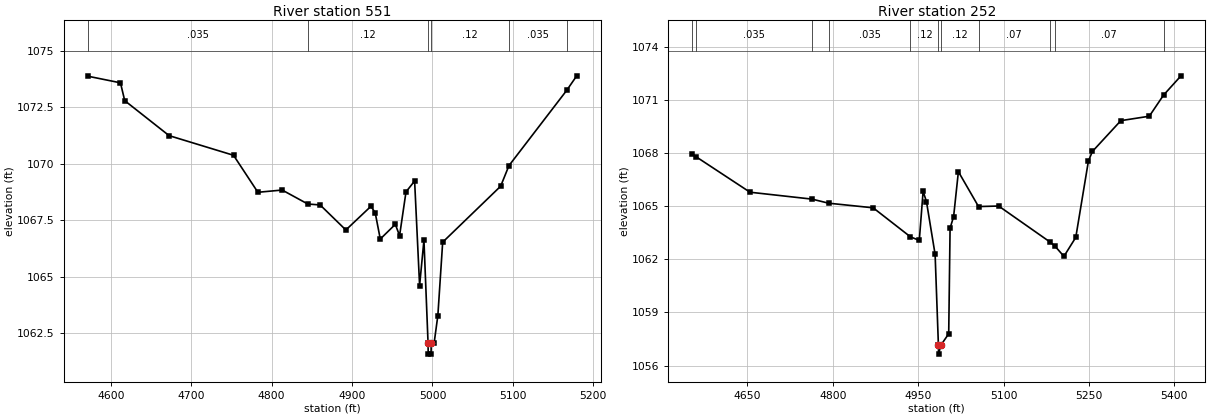
Type RM Length L Ch R = 1,551,299,299,299
BEGIN DESCRIPTION:
Miller Tributary 2 1.0
END DESCRIPTION:
XS GIS Cut Line= 3
      2171725.02     13854074.96      2171575.00     13854475.00
      2171724.98     13854574.99
#Sta/Elev= 30
  4571.9 1073.88  4612.0 1073.59  4617.3 1072.80  4672.5 1071.25  4752.6 1070.38
  4782.9 1068.74  4813.1 1068.84  4845.0 1068.22  4860.3 1068.18  4892.3 1067.07
  4923.5 1068.12  4928.8 1067.83  4935.1 1066.67  4953.8 1067.32  4959.1 1066.82
  4967.1 1068.76  4977.8 1069.24  4984.0 1064.61  4989.4 1066.62  4994.5 1062.07
  4994.7 1061.57  4998.2 1061.57  4998.5 1062.07  5002.1 1062.07  5006.7 1063.28
  5012.7 1066.53  5084.8 1069.01  5095.1 1069.92  5166.8 1073.25  5179.4 1073.90
#Mann=6,-1,0
  4571.9   0.035       0  4845.0    0.12       0  4994.5    0.05       0
  4998.5    0.12       0  5095.1   0.035       0  5166.8   0.063       0
Bank Sta=4994.5,4998.5
Exp/Cntr=0.3,0.1

Type RM Length L Ch R = 1,252,0,0,0
BEGIN DESCRIPTION:
Miller Tributary 2 0.1
END DESCRIPTION:
XS GIS Cut Line= 3
      2171550.00     13854000.00      2171307.11     13854376.66
      2171552.77     13854705.31
#Sta/Elev= 30
  4553.4 1067.93  4560.3 1067.78  4654.5 1065.79  4763.5 1065.40  4792.6 1065.17
  4870.9 1064.91  4936.5 1063.27  4952.0 1063.07  4958.7 1065.84  4964.6 1065.26
  4979.8 1062.28  4985.6 1057.15  4985.9 1056.65  4989.8 1057.15  5003.7 1057.80
  5006.1 1063.76  5012.3 1064.41  5020.7 1066.95  5056.1 1064.98  5091.5 1065.01
  5181.7 1062.98  5190.3 1062.75  5206.2 1062.17  5227.0 1063.24  5249.2 1067.55
  5256.2 1068.09  5306.2 1069.83  5356.2 1070.08  5381.2 1071.27  5411.9 1072.36
#Mann=11,-1,0
  4553.4    0.07       0  4560.3   0.035       0  4763.5    0.12       0
  4792.6   0.035       0  4936.5    0.12       0  4985.6    0.05       0
  4989.8    0.12       0  5056.1    0.07       0  5181.7   0.035       0
  5190.3    0.07       0  5381.2   0.035       0
Bank Sta=4985.6,4989.8
Exp/Cntr=0.3,0.1

Chan Stop Cuts=-1