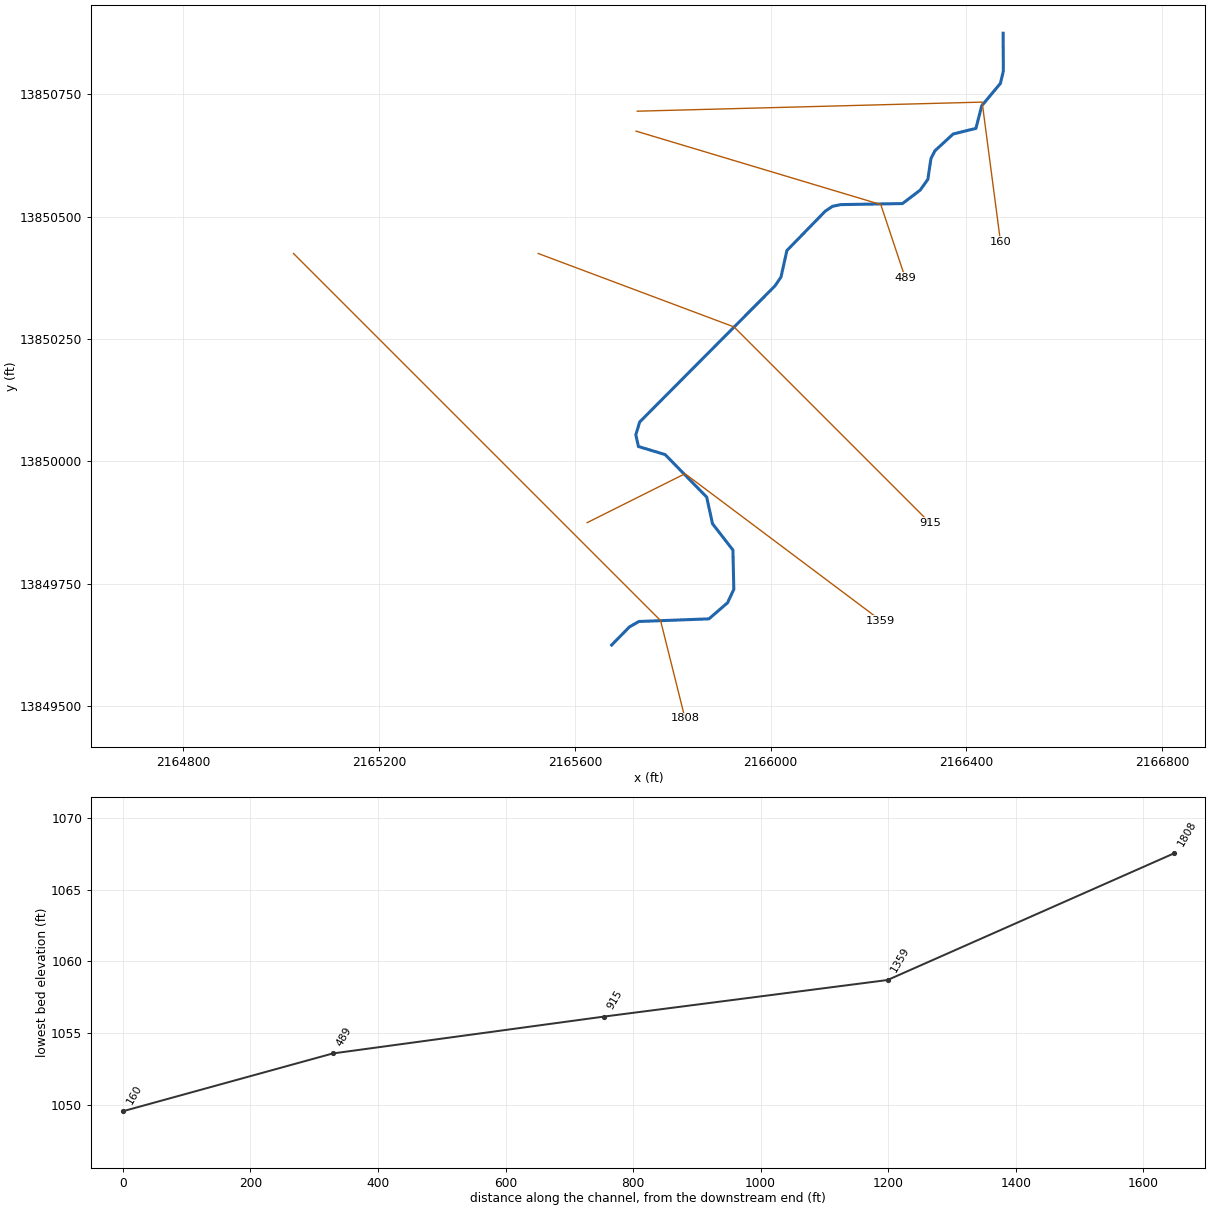
--- Miller Tributary 4.prj (project) ---

Proj Title=Miller Tributary 4 Base Level Engineering
Current Plan=p01
Default Exp/Contr=0.3,0.1
English Units
Geom File=g01
Flow File=f01
Plan File=p01
BEGIN DESCRIPTION:
Miller Tributary 4
END DESCRIPTION:

--- Miller Tributary 4.p01 (plan) ---

Plan Title=Multiple Run
Short Identifier=Multiple
Geom File=g01
Flow File=f01
Subcritical Flow
K Sum by GR= 0
Std Step Tol= 0.01
Critical Tol= 0.01
Num of Std Step Trials= 20
Max Error Tol= 0.3
Flow Tol Ratio= 0.001
Split Flow NTrial= 30
Split Flow Tol= 0.02
Split Flow Ratio= 0.02
Log Output Level= 0
Friction Slope Method= 1
Unsteady Friction Slope Method= 2
Unsteady Bridges Friction Slope Method= 1
Parabolic Critical Depth
Global Vel Dist=  1 , 1 , 1
Global Log Level= 0
CheckData=True
Encroach Param= -1, 0, 0, 0
BEGIN DESCRIPTION:
Multiple Run
END DESCRIPTION:

--- Miller Tributary 4.f01 (steady flow) ---

Flow Title=Multiple
Number of Profiles=7
Profile Names=10-year,25-year,50-year,1pct_min,100-year,1pct_plu,500-year
River Rch & RM= Miller Tributary,Reach-1,1808
    1265    2179    3061    2084    4158    8295    7593
Boundary for River Rch & Prof#=Miller Tributary,Reach-1,1
Up Type=0
Dn Type=3
Dn Slope=0.005
Boundary for River Rch & Prof#=Miller Tributary,Reach-1,2
Up Type=0
Dn Type=3
Dn Slope=0.005
Boundary for River Rch & Prof#=Miller Tributary,Reach-1,3
Up Type=0
Dn Type=3
Dn Slope=0.005
Boundary for River Rch & Prof#=Miller Tributary,Reach-1,4
Up Type=0
Dn Type=3
Dn Slope=0.005
Boundary for River Rch & Prof#=Miller Tributary,Reach-1,5
Up Type=0
Dn Type=3
Dn Slope=0.005
Boundary for River Rch & Prof#=Miller Tributary,Reach-1,6
Up Type=0
Dn Type=3
Dn Slope=0.005
Boundary for River Rch & Prof#=Miller Tributary,Reach-1,7
Up Type=0
Dn Type=3
Dn Slope=0.005

--- Miller Tributary 4.g01 (geometry) ---

Geom Title=Existing Conditions

River Reach=Miller Tributary,Reach-1
Reach XY= 30
      2165675.00     13849625.00      2165711.50     13849662.08
      2165730.79     13849673.09      2165873.78     13849678.44
      2165911.84     13849711.27      2165924.66     13849738.76
      2165922.86     13849819.03      2165881.15     13849872.83
      2165869.17     13849927.31      2165784.35     13850014.12
      2165729.74     13850030.62      2165724.42     13850054.58
      2165732.34     13850080.75      2166008.35     13850358.33
      2166021.02     13850376.65      2166033.15     13850431.07
      2166111.66     13850511.64      2166126.46     13850521.46
      2166143.22     13850524.89      2166269.32     13850526.99
      2166305.41     13850554.43      2166321.12     13850576.43
      2166327.50     13850619.08      2166335.71     13850634.96
      2166372.80     13850669.11      2166419.38     13850680.62
      2166431.25     13850726.84      2166469.38     13850772.58
      2166475.38     13850797.56      2166475.00     13850875.00

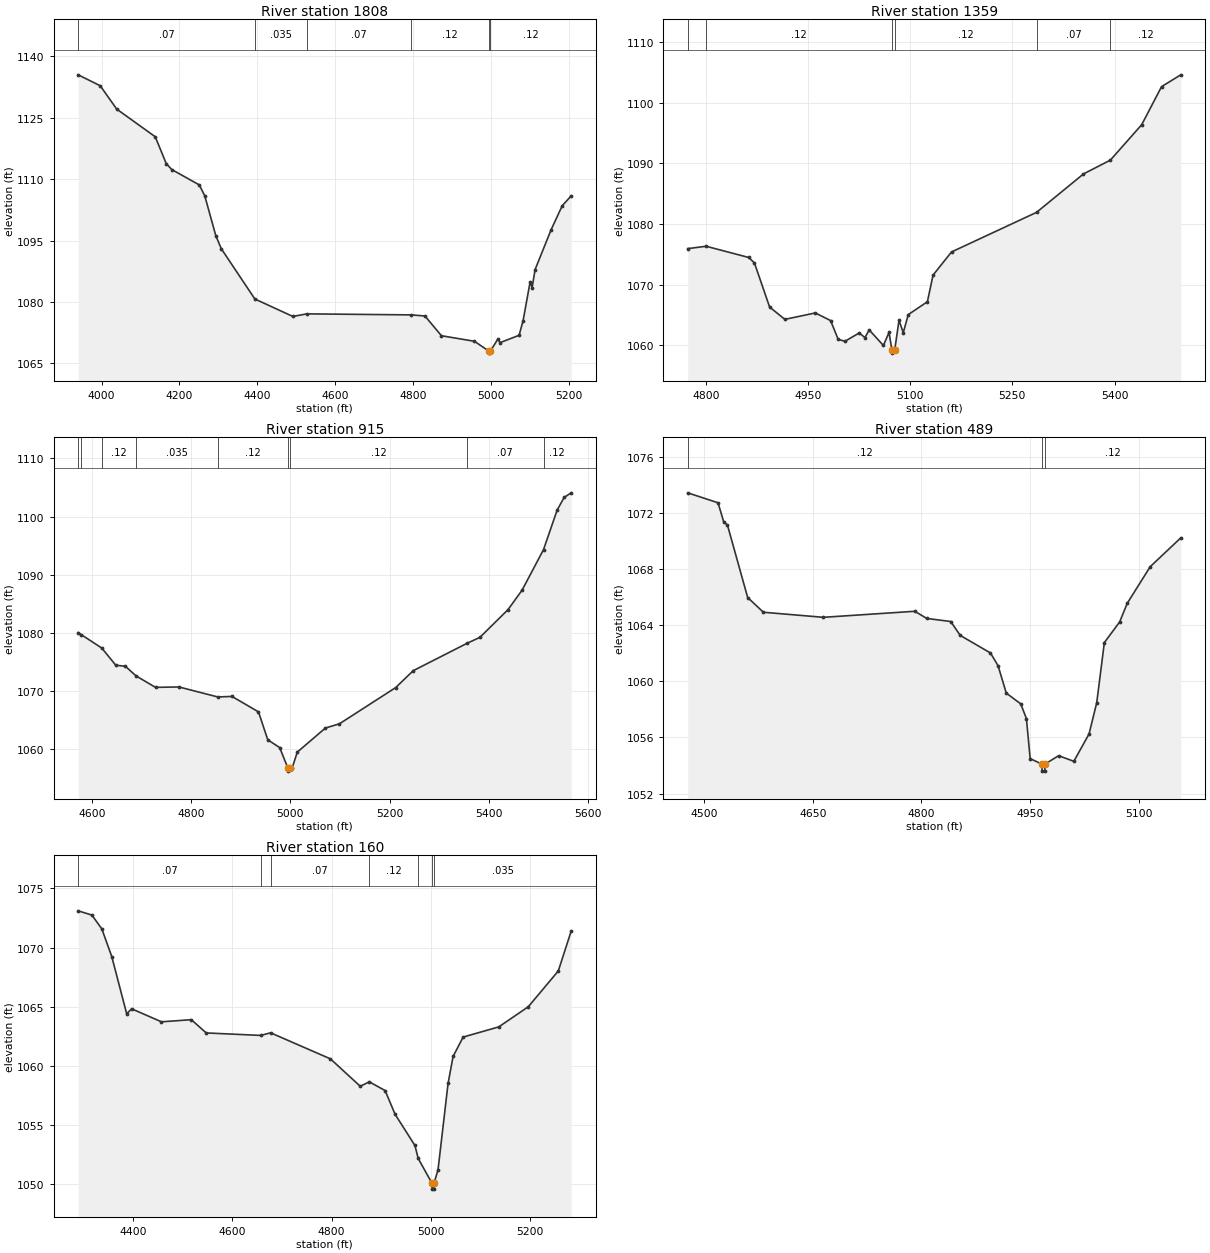
Type RM Length L Ch R = 1,1808,449,449,449
BEGIN DESCRIPTION:
Miller Tributary 4 4.0
END DESCRIPTION:
XS GIS Cut Line= 3
      2165024.97     13850425.03      2165775.00     13849675.00
      2165825.01     13849474.95
#Sta/Elev= 30
  3939.7 1135.50  3996.3 1132.83  4038.7 1127.13  4137.7 1120.37  4166.0 1113.81
  4180.2 1112.36  4250.9 1108.61  4265.0 1105.93  4293.3 1096.21  4307.4 1093.02
  4393.7 1080.74  4491.3 1076.48  4527.3 1077.11  4795.6 1076.86  4830.7 1076.59
  4873.1 1071.77  4958.0 1070.41  4994.9 1068.02  4995.1 1067.52  4998.9 1068.02
  5018.4 1070.99  5023.6 1070.08  5072.6 1071.87  5082.9 1075.44  5100.9 1084.88
  5106.1 1083.53  5113.8 1087.94  5155.0 1097.68  5183.4 1103.51  5206.6 1105.95
#Mann=6,-1,0
  3939.7    0.07       0  4393.7   0.035       0  4527.3    0.07       0
  4795.6    0.12       0  4994.9    0.05       0  4998.9    0.12       0
Bank Sta=4994.9,4998.9
Exp/Cntr=0.3,0.1

Type RM Length L Ch R = 1,1359,444,444,444
BEGIN DESCRIPTION:
Miller Tributary 4 3.0
END DESCRIPTION:
XS GIS Cut Line= 3
      2165624.96     13849874.98      2165825.00     13849975.00
      2166225.04     13849674.97
#Sta/Elev= 30
  4773.5 1075.95  4800.5 1076.34  4863.0 1074.49  4871.4 1073.59  4893.7 1066.31
  4916.1 1064.28  4960.8 1065.34  4983.2 1064.08  4994.4 1060.97  5004.4 1060.67
  5025.3 1062.04  5033.6 1061.27  5039.9 1062.54  5060.7 1059.97  5069.0 1062.14
  5073.2 1059.21  5073.5 1058.71  5077.3 1059.21  5083.6 1064.11  5089.9 1062.09
  5097.2 1065.06  5125.3 1067.19  5133.6 1071.58  5160.7 1075.40  5285.5 1081.93
  5354.4 1088.27  5393.9 1090.55  5439.9 1096.40  5469.0 1102.67  5497.2 1104.62
#Mann=6,-1,0
  4773.5    0.07       0  4800.5    0.12       0  5073.2    0.05       0
  5077.3    0.12       0  5285.5    0.07       0  5393.9    0.12       0
Bank Sta=5073.2,5077.3
Exp/Cntr=0.3,0.1

Type RM Length L Ch R = 1,915,426,426,426
BEGIN DESCRIPTION:
Miller Tributary 4 2.0
END DESCRIPTION:
XS GIS Cut Line= 3
      2165525.02     13850424.99      2165925.00     13850275.00
      2166325.03     13849874.97
#Sta/Elev= 30
  4572.8 1080.02  4579.3 1079.65  4620.3 1077.36  4648.4 1074.41  4668.0 1074.21
  4689.2 1072.57  4728.5 1070.59  4775.7 1070.66  4853.8 1068.94  4882.5 1069.03
  4935.9 1066.37  4954.6 1061.56  4978.6 1060.22  4995.2 1056.67  4995.5 1056.17
  4999.4 1056.67  5003.5 1056.67  5014.1 1059.45  5070.7 1063.59  5099.0 1064.32
  5212.1 1070.55  5247.5 1073.46  5355.8 1078.17  5381.8 1079.20  5438.4 1083.97
  5466.7 1087.32  5509.9 1094.30  5537.4 1101.12  5551.5 1103.29  5565.7 1104.08
#Mann=9,-1,0
  4572.8   0.035       0  4579.3    0.07       0  4620.3    0.12       0
  4689.2   0.035       0  4853.8    0.12       0  4995.2    0.05       0
  4999.4    0.12       0  5355.8    0.07       0  5509.9    0.12       0
Bank Sta=4995.2,4999.4
Exp/Cntr=0.3,0.1

Type RM Length L Ch R = 1,489,329,329,329
BEGIN DESCRIPTION:
Miller Tributary 4 1.0
END DESCRIPTION:
XS GIS Cut Line= 3
      2165725.00     13850675.00      2166225.00     13850525.00
      2166274.99     13850375.03
#Sta/Elev= 30
  4477.6 1073.43  4519.4 1072.72  4527.2 1071.37  4532.4 1071.13  4560.3 1065.97
  4582.0 1064.92  4664.7 1064.56  4790.8 1064.99  4807.3 1064.48  4840.4 1064.26
  4853.5 1063.27  4895.2 1062.02  4905.7 1061.11  4917.0 1059.16  4937.0 1058.39
  4944.8 1057.34  4950.0 1054.49  4966.2 1054.10  4966.4 1053.60  4970.1 1053.60
  4970.4 1054.10  4989.2 1054.70  5010.2 1054.30  5031.2 1056.25  5041.8 1058.48
  5052.3 1062.76  5073.4 1064.23  5083.9 1065.56  5115.6 1068.17  5157.7 1070.22
#Mann=3,-1,0
  4477.6    0.12       0  4966.2    0.05       0  4970.4    0.12       0
Bank Sta=4966.2,4970.4
Exp/Cntr=0.3,0.1

Type RM Length L Ch R = 1,160,0,0,0
BEGIN DESCRIPTION:
Miller Tributary 4 0.1
END DESCRIPTION:
XS GIS Cut Line= 3
      2165727.43     13850715.78      2166432.04     13850734.31
      2166469.53     13850449.22
#Sta/Elev= 30
  4290.0 1073.10  4317.6 1072.74  4337.6 1071.57  4357.6 1069.23  4387.6 1064.40
  4397.6 1064.82  4457.6 1063.72  4517.7 1063.90  4547.7 1062.78  4657.4 1062.57
  4677.3 1062.79  4797.7 1060.59  4857.8 1058.27  4875.9 1058.65  4907.8 1057.91
  4927.8 1055.91  4967.8 1053.27  4974.4 1052.17  5002.1 1050.08  5002.4 1049.58
  5006.1 1049.58  5006.3 1050.08  5014.3 1051.22  5034.5 1058.51  5044.6 1060.79
  5064.8 1062.43  5136.5 1063.29  5195.9 1064.99  5256.4 1068.02  5282.4 1071.40
#Mann=7,-1,0
  4290.0    0.07       0  4657.4    0.12       0  4677.3    0.07       0
  4875.9    0.12       0  4974.4   0.035       0  5002.1   0.035       0
  5006.3   0.035       0
Bank Sta=5002.1,5006.3
Exp/Cntr=0.3,0.1

Chan Stop Cuts=-1