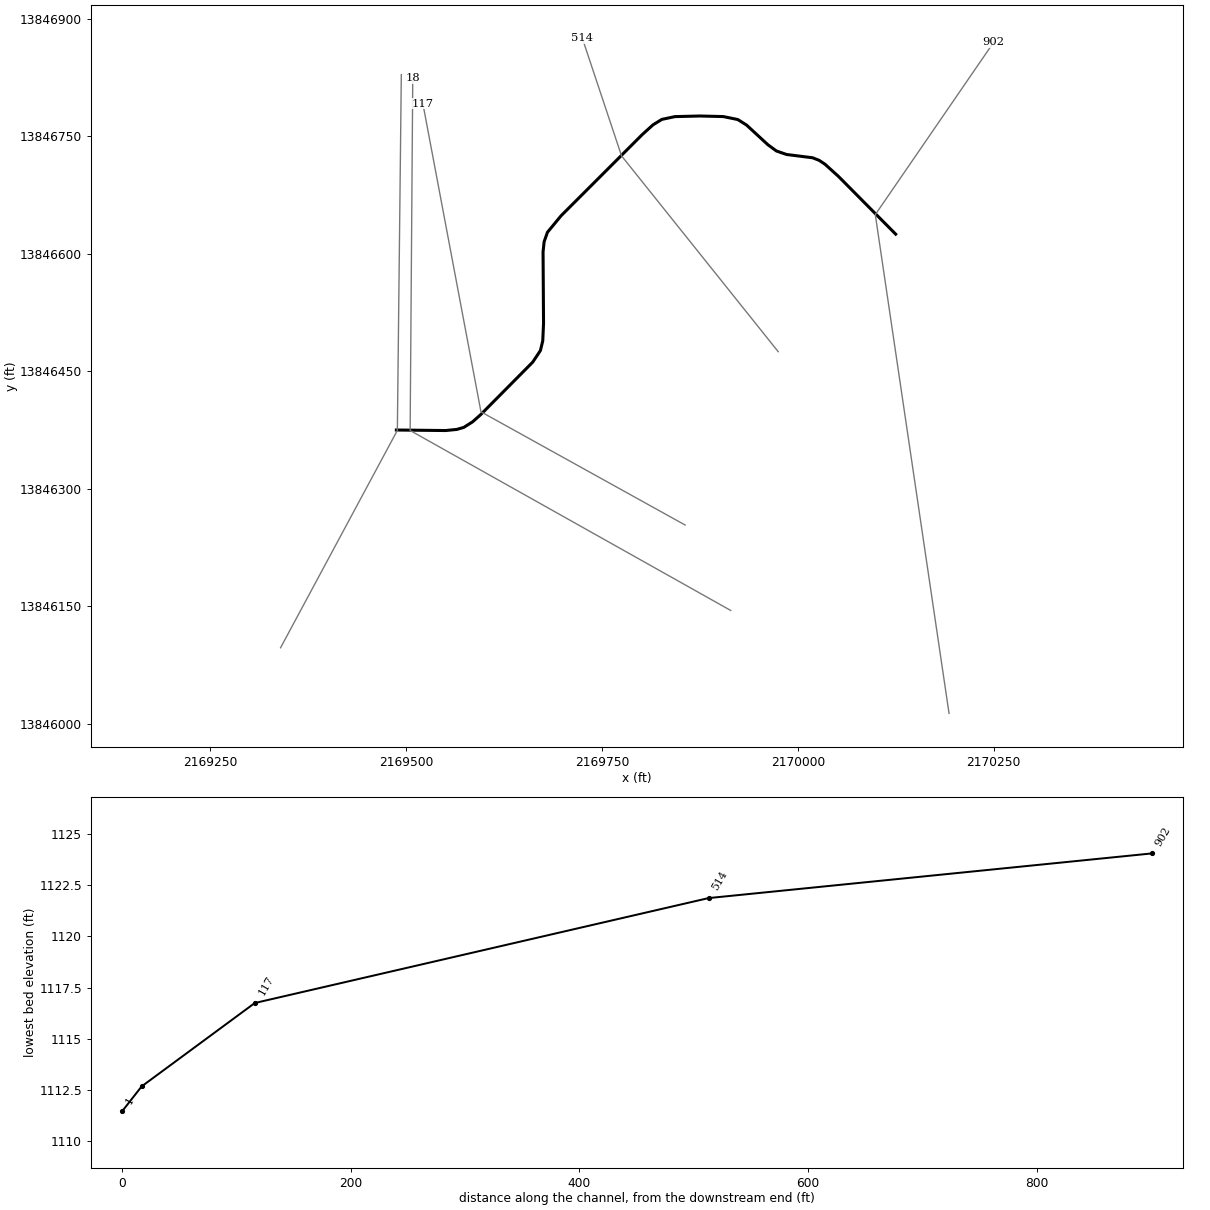
--- Miller Tributary 8.prj (project) ---

Proj Title=Miller Tributary 8 Base Level Engineering
Current Plan=p01
Default Exp/Contr=0.3,0.1
English Units
Geom File=g01
Flow File=f01
Plan File=p01
BEGIN DESCRIPTION:
Miller Tributary 8
END DESCRIPTION:

--- Miller Tributary 8.p01 (plan) ---

Plan Title=Multiple Run
Short Identifier=Multiple
Geom File=g01
Flow File=f01
Subcritical Flow
K Sum by GR= 0
Std Step Tol= 0.01
Critical Tol= 0.01
Num of Std Step Trials= 20
Max Error Tol= 0.3
Flow Tol Ratio= 0.001
Split Flow NTrial= 30
Split Flow Tol= 0.02
Split Flow Ratio= 0.02
Log Output Level= 0
Friction Slope Method= 1
Unsteady Friction Slope Method= 2
Unsteady Bridges Friction Slope Method= 1
Parabolic Critical Depth
Global Vel Dist=  1 , 1 , 1
Global Log Level= 0
CheckData=True
Encroach Param= -1, 0, 0, 0
BEGIN DESCRIPTION:
Multiple Run
END DESCRIPTION:

--- Miller Tributary 8.f01 (steady flow) ---

Flow Title=Multiple
Number of Profiles=7
Profile Names=10-year,25-year,50-year,1pct_min,100-year,1pct_plu,500-year
River Rch & RM= Miller Tributary,Reach-1,902
    1797    3137    4445    3046    6078   12128   11257
Boundary for River Rch & Prof#=Miller Tributary,Reach-1,1
Up Type=0
Dn Type=3
Dn Slope=0.005
Boundary for River Rch & Prof#=Miller Tributary,Reach-1,2
Up Type=0
Dn Type=3
Dn Slope=0.005
Boundary for River Rch & Prof#=Miller Tributary,Reach-1,3
Up Type=0
Dn Type=3
Dn Slope=0.005
Boundary for River Rch & Prof#=Miller Tributary,Reach-1,4
Up Type=0
Dn Type=3
Dn Slope=0.005
Boundary for River Rch & Prof#=Miller Tributary,Reach-1,5
Up Type=0
Dn Type=3
Dn Slope=0.005
Boundary for River Rch & Prof#=Miller Tributary,Reach-1,6
Up Type=0
Dn Type=3
Dn Slope=0.005
Boundary for River Rch & Prof#=Miller Tributary,Reach-1,7
Up Type=0
Dn Type=3
Dn Slope=0.005

--- Miller Tributary 8.g01 (geometry) ---

Geom Title=Existing Conditions

River Reach=Miller Tributary,Reach-1
Reach XY= 30
      2170125.00     13846625.00      2170051.86     13846698.80
      2170034.71     13846714.30      2170027.32     13846719.21
      2170018.97     13846722.52      2169985.71     13846726.71
      2169972.83     13846731.14      2169961.96     13846739.06
      2169934.65     13846764.25      2169923.41     13846771.33
      2169904.90     13846775.12      2169874.99     13846775.85
      2169843.28     13846775.07      2169826.50     13846771.54
      2169815.21     13846764.57      2169801.48     13846752.16
      2169697.86     13846648.53      2169680.47     13846627.45
      2169676.21     13846615.41      2169674.83     13846602.35
      2169675.45     13846511.17      2169674.45     13846488.86
      2169671.46     13846476.46      2169661.64     13846461.65
      2169595.20     13846394.61      2169584.85     13846385.42
      2169573.63     13846378.33      2169564.70     13846375.74
      2169550.28     13846374.32      2169487.57     13846375.00

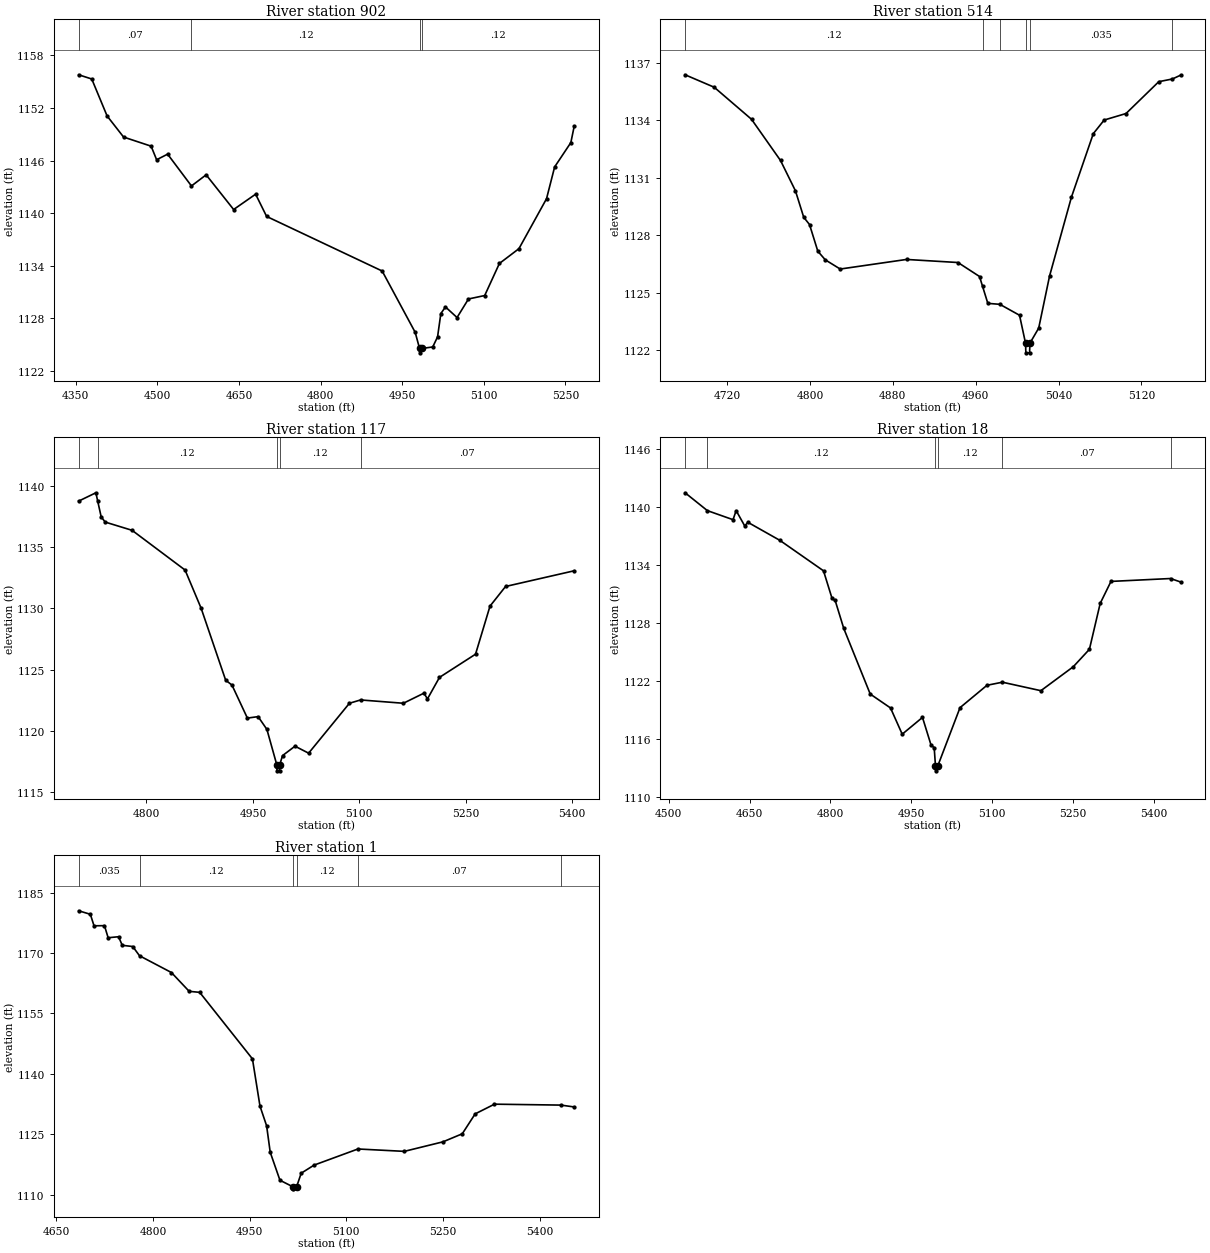
Type RM Length L Ch R = 1,902,388,388,388
BEGIN DESCRIPTION:
Miller Tributary 8 2.0
END DESCRIPTION:
XS GIS Cut Line= 3
      2170193.09     13846013.27      2170098.95     13846649.94
      2170250.06     13846869.95
#Sta/Elev= 30
  4355.5 1155.79  4379.6 1155.31  4407.8 1151.09  4438.1 1148.68  4488.7 1147.64
  4498.8 1146.09  4519.0 1146.73  4562.8 1143.10  4589.8 1144.37  4640.3 1140.41
  4680.7 1142.16  4700.9 1139.62  4913.2 1133.39  4973.9 1126.39  4981.9 1124.55
  4982.2 1124.05  4986.0 1124.55  5006.1 1124.72  5015.0 1125.87  5021.0 1128.53
  5029.5 1129.29  5050.8 1128.08  5071.8 1130.20  5101.6 1130.59  5128.6 1134.25
  5164.5 1135.94  5215.2 1141.64  5230.1 1145.27  5259.9 1148.05  5266.0 1149.90
#Mann=4,-1,0
  4355.5    0.07       0  4562.8    0.12       0  4981.9    0.05       0
  4986.0    0.12       0
Bank Sta=4981.9,4986
Exp/Cntr=0.3,0.1

Type RM Length L Ch R = 1,514,397,397,397
BEGIN DESCRIPTION:
Miller Tributary 8 1.0
END DESCRIPTION:
XS GIS Cut Line= 3
      2169975.03     13846474.97      2169775.00     13846725.00
      2169725.00     13846874.99
#Sta/Elev= 30
  4679.5 1136.37  4707.6 1135.72  4743.6 1134.05  4771.6 1131.90  4786.0 1130.32
  4794.0 1128.94  4799.6 1128.56  4807.6 1127.17  4814.8 1126.72  4829.2 1126.24
  4893.2 1126.74  4942.9 1126.58  4963.7 1125.85  4966.6 1125.34  4971.7 1124.45
  4983.3 1124.40  5002.3 1123.83  5008.1 1122.37  5008.4 1121.87  5012.0 1121.87
  5012.3 1122.37  5020.8 1123.16  5031.3 1125.88  5052.4 1129.99  5073.5 1133.30
  5084.0 1134.01  5105.1 1134.35  5136.7 1136.01  5149.8 1136.15  5157.8 1136.35
#Mann=6,-1,0
  4679.5    0.12       0  4966.6    0.07       0  4983.3   0.035       0
  5008.1   0.035       0  5012.3   0.035       0  5149.8    0.07       0
Bank Sta=5008.1,5012.3
Exp/Cntr=0.3,0.1

Type RM Length L Ch R = 1,117,99,99,99
BEGIN DESCRIPTION:
Miller Tributary 8 0.2
END DESCRIPTION:
XS GIS Cut Line= 3
      2169856.21     13846253.69      2169595.56     13846398.24
      2169521.42     13846791.56
#Sta/Elev= 30
  4704.4 1138.74  4728.7 1139.42  4731.2 1138.76  4736.2 1137.45  4741.9 1137.03
  4779.7 1136.36  4854.4 1133.12  4877.0 1130.01  4911.6 1124.14  4920.5 1123.74
  4942.2 1121.05  4957.3 1121.17  4969.7 1120.13  4983.6 1117.25  4983.9 1116.75
  4987.5 1116.75  4987.8 1117.25  4991.7 1117.99  5009.3 1118.76  5028.5 1118.19
  5086.0 1122.26  5101.7 1122.53  5162.0 1122.26  5190.9 1123.08  5196.0 1122.62
  5212.9 1124.37  5263.7 1126.26  5284.1 1130.18  5306.0 1131.78  5402.7 1133.06
#Mann=5,-1,0
  4704.4    0.07       0  4731.2    0.12       0  4983.6    0.05       0
  4987.8    0.12       0  5101.7    0.07       0
Bank Sta=4983.6,4987.8
Exp/Cntr=0.3,0.1

Type RM Length L Ch R = 1,18,17,17,17
BEGIN DESCRIPTION:
Miller Tributary 8 0.1
END DESCRIPTION:
XS GIS Cut Line= 3
      2169914.36     13846144.66      2169505.16     13846374.39
      2169508.49     13846824.20
#Sta/Elev= 30
  4530.4 1141.51  4571.7 1139.66  4619.3 1138.72  4625.1 1139.66  4641.0 1138.07
  4646.8 1138.45  4706.1 1136.58  4787.1 1133.42  4803.0 1130.55  4808.7 1130.35
  4824.7 1127.44  4873.8 1120.64  4911.4 1119.20  4933.1 1116.48  4970.7 1118.22
  4986.7 1115.33  4992.4 1115.09  4994.8 1113.18  4995.1 1112.68  4999.0 1113.18
  5040.3 1119.23  5090.3 1121.55  5118.9 1121.87  5190.3 1120.99  5250.3 1123.47
  5280.3 1125.28  5300.3 1130.04  5320.3 1132.32  5430.7 1132.62  5449.5 1132.26
#Mann=6,-1,0
  4530.4    0.07       0  4571.7    0.12       0  4994.8    0.05       0
  4999.0    0.12       0  5118.9    0.07       0  5430.7   0.035       0
Bank Sta=4994.8,4999
Exp/Cntr=0.3,0.1

Type RM Length L Ch R = 1,1,0,0,0
BEGIN DESCRIPTION:
Miller Tributary 8 0.0
END DESCRIPTION:
XS GIS Cut Line= 3
      2169339.75     13846097.02      2169488.84     13846374.53
      2169493.89     13846828.68
#Sta/Elev= 30
  4684.5 1180.47  4702.7 1179.60  4708.4 1176.74  4724.6 1176.78  4730.3 1173.78
  4746.5 1174.03  4752.2 1171.90  4768.5 1171.60  4779.0 1169.31  4828.5 1165.15
  4856.1 1160.48  4872.4 1160.23  4954.3 1143.72  4966.0 1132.00  4976.3 1127.11
  4981.9 1120.54  4997.0 1113.60  5017.2 1111.97  5017.6 1111.47  5022.8 1111.97
  5030.0 1115.35  5050.0 1117.36  5118.1 1121.36  5190.0 1120.77  5250.0 1123.13
  5280.0 1125.13  5300.0 1130.07  5330.0 1132.48  5433.1 1132.25  5453.7 1131.79
#Mann=6,-1,0
  4684.5   0.035       0  4779.0    0.12       0  5017.2    0.05       0
  5022.8    0.12       0  5118.1    0.07       0  5433.1   0.035       0
Bank Sta=5017.2,5022.8
Exp/Cntr=0.3,0.1

Chan Stop Cuts=-1