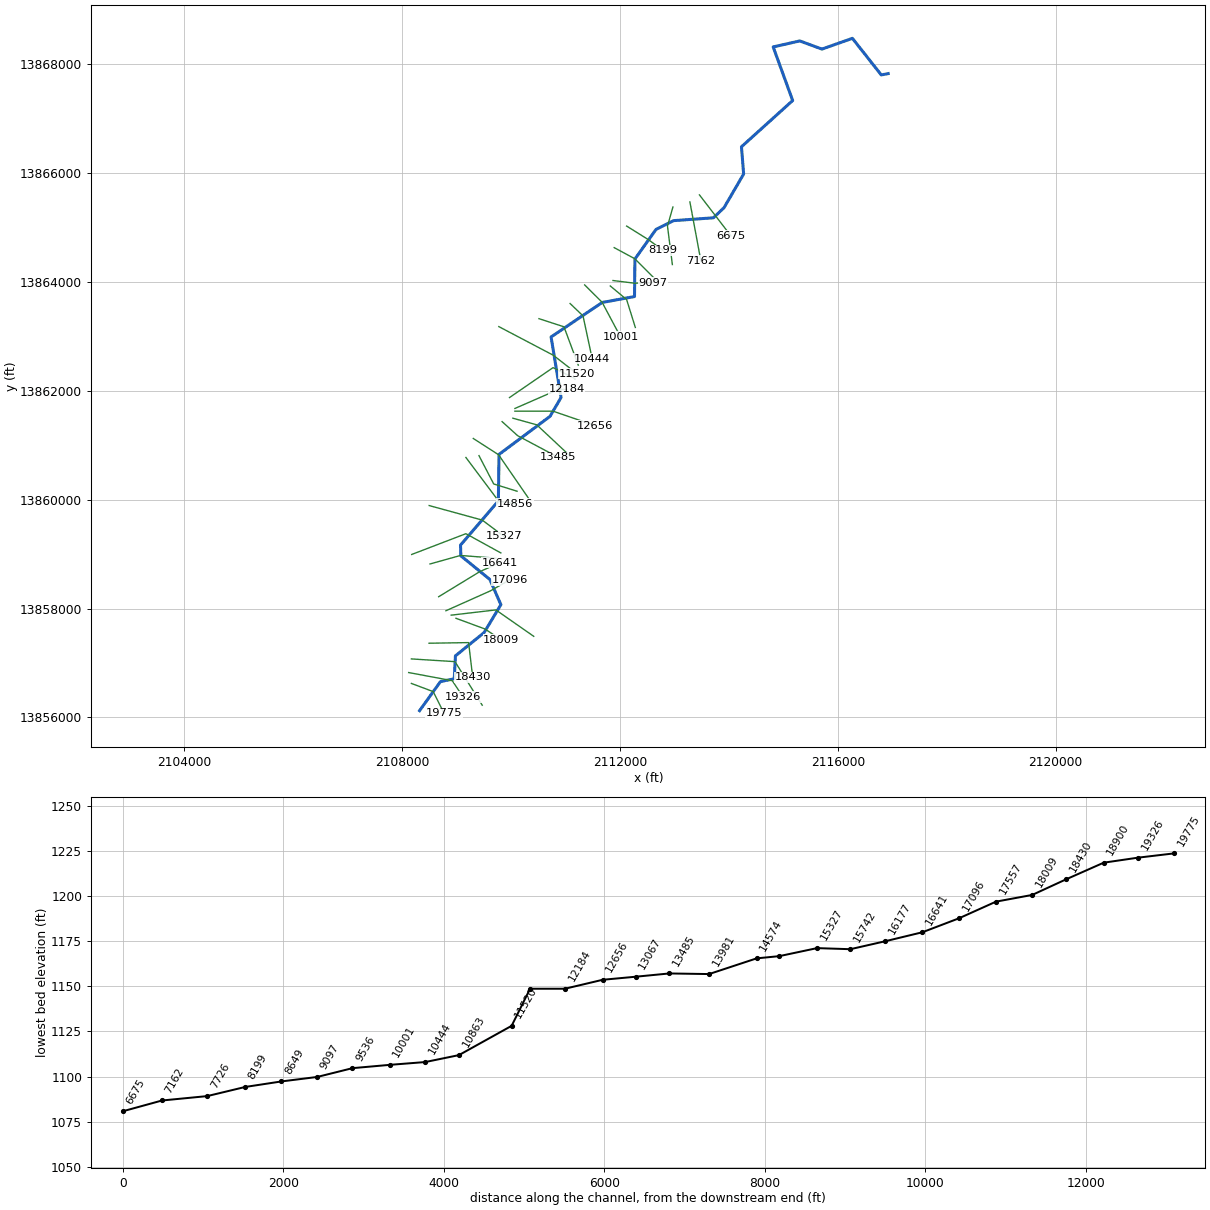
--- PANTHER CREEK.prj (project) ---

Proj Title=PANTHER CREEK Base Level Engineering
Current Plan=p01
Default Exp/Contr=0.3,0.1
English Units
Geom File=g01
Flow File=f01
Plan File=p01
BEGIN DESCRIPTION:
PANTHER CREEK
END DESCRIPTION:

--- PANTHER CREEK.p01 (plan) ---

Plan Title=Multiple Run
Short Identifier=Multiple
Geom File=g01
Flow File=f01
Subcritical Flow
K Sum by GR= 0
Std Step Tol= 0.01
Critical Tol= 0.01
Num of Std Step Trials= 20
Max Error Tol= 0.3
Flow Tol Ratio= 0.001
Split Flow NTrial= 30
Split Flow Tol= 0.02
Split Flow Ratio= 0.02
Log Output Level= 0
Friction Slope Method= 1
Unsteady Friction Slope Method= 2
Unsteady Bridges Friction Slope Method= 1
Parabolic Critical Depth
Global Vel Dist=  1 , 1 , 1
Global Log Level= 0
CheckData=True
Encroach Param= -1, 0, 0, 0
BEGIN DESCRIPTION:
Multiple Run
END DESCRIPTION:

--- PANTHER CREEK.f01 (steady flow) ---

Flow Title=Multiple
Number of Profiles=7
Profile Names=10-year,25-year,50-year,1pct_min,100-year,1pct_plu,500-year
River Rch & RM= PANTHER CREEK,Reach-1,19775
    1162    1959    2713    1820    3631    7244    6432
River Rch & RM= PANTHER CREEK,Reach-1,18009
    2294    4011    5691    3901    7783   15528   14413
River Rch & RM= PANTHER CREEK,Reach-1,10863
    2674    4701    6696    4605    9187   18331   17126
River Rch & RM= PANTHER CREEK,Reach-1,7726
    2879    5066    7219    4964    9905   19763   18466
River Rch & RM= PANTHER CREEK,Reach-1,2706
    2791    4921    7020    4832    9641   19236   18017
River Rch & RM= PANTHER CREEK,Reach-1,2308
    2810    4954    7065    4862    9702   19357   18122
Boundary for River Rch & Prof#=PANTHER CREEK,Reach-1,1
Up Type=0
Dn Type=3
Dn Slope=0.005
Boundary for River Rch & Prof#=PANTHER CREEK,Reach-1,2
Up Type=0
Dn Type=3
Dn Slope=0.005
Boundary for River Rch & Prof#=PANTHER CREEK,Reach-1,3
Up Type=0
Dn Type=3
Dn Slope=0.005
Boundary for River Rch & Prof#=PANTHER CREEK,Reach-1,4
Up Type=0
Dn Type=3
Dn Slope=0.005
Boundary for River Rch & Prof#=PANTHER CREEK,Reach-1,5
Up Type=0
Dn Type=3
Dn Slope=0.005
Boundary for River Rch & Prof#=PANTHER CREEK,Reach-1,6
Up Type=0
Dn Type=3
Dn Slope=0.005
Boundary for River Rch & Prof#=PANTHER CREEK,Reach-1,7
Up Type=0
Dn Type=3
Dn Slope=0.005

--- PANTHER CREEK.g01 (geometry) ---

Geom Title=Existing Conditions

River Reach=PANTHER CREEK,Reach-1
Reach XY= 30
      2108325.00     13856125.00      2108708.23     13856658.57
      2108961.65     13856711.19      2108982.85     13857131.19
      2109508.58     13857558.08      2109817.22     13858071.60
      2109614.53     13858534.82      2109082.81     13858968.81
      2109076.38     13859165.34      2109771.25     13859976.55
      2109782.81     13860831.19      2110719.42     13861530.58
      2110921.53     13861876.50      2110738.53     13862988.38
      2111676.47     13863621.45      2112269.76     13863730.44
      2112277.38     13864419.47      2112665.19     13864964.49
      2112985.62     13865124.40      2113719.38     13865176.73
      2113914.30     13865365.03      2114272.63     13865980.53
      2114232.82     13866481.19      2115172.66     13867330.52
      2114814.90     13868314.74      2115302.31     13868425.10
      2115709.73     13868275.37      2116269.07     13868472.77
      2116798.26     13867800.69      2116925.00     13867825.00

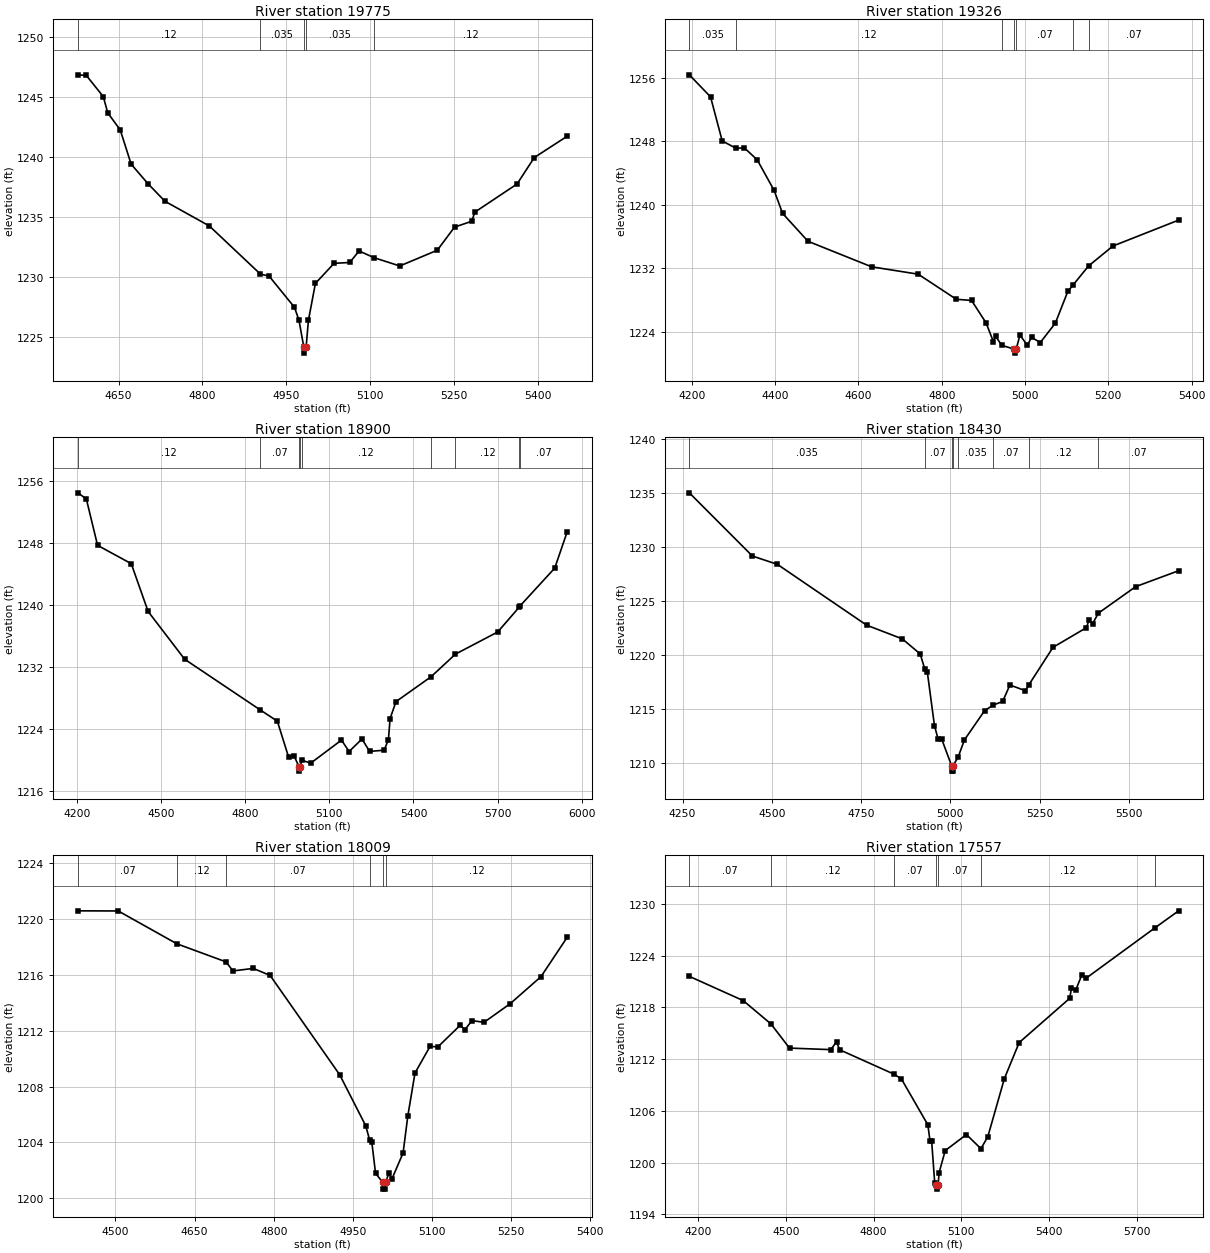
Type RM Length L Ch R = 1,19775,449,449,449
BEGIN DESCRIPTION:
PANTHER CREEK 43.0
END DESCRIPTION:
XS GIS Cut Line= 3
      2108175.02     13856624.99      2108575.00     13856475.00
      2108775.00     13856074.99
#Sta/Elev= 30
  4577.4 1246.82  4592.5 1246.77  4622.8 1245.01  4630.8 1243.65  4653.0 1242.25
  4672.6 1239.39  4702.9 1237.75  4733.1 1236.30  4812.3 1234.25  4903.7 1230.24
  4919.1 1230.08  4964.5 1227.48  4972.5 1226.41  4981.2 1224.17  4981.4 1223.67
  4985.3 1224.17  4989.4 1226.39  5001.9 1229.47  5035.3 1231.14  5063.3 1231.21
  5080.0 1232.17  5106.6 1231.61  5152.7 1230.92  5219.8 1232.23  5250.5 1234.15
  5281.3 1234.64  5286.9 1235.40  5362.3 1237.74  5393.1 1239.94  5451.8 1241.71
#Mann=5,-1,0
  4577.4    0.12       0  4903.7   0.035       0  4981.2   0.035       0
  4985.3   0.035       0  5106.6    0.12       0
Bank Sta=4981.2,4985.3
Exp/Cntr=0.3,0.1

Type RM Length L Ch R = 1,19326,426,426,426
BEGIN DESCRIPTION:
PANTHER CREEK 42.0
END DESCRIPTION:
XS GIS Cut Line= 3
      2108125.00     13856825.00      2108925.00     13856675.00
      2109125.00     13856375.00
#Sta/Elev= 30
  4194.2 1256.41  4245.1 1253.63  4273.1 1248.07  4307.1 1247.12  4325.6 1247.22
  4357.0 1245.70  4397.7 1241.83  4418.0 1238.93  4479.1 1235.41  4631.7 1232.19
  4743.6 1231.26  4835.2 1228.09  4871.6 1227.95  4906.4 1225.13  4924.2 1222.73
  4929.3 1223.46  4944.0 1222.28  4974.7 1221.80  4975.0 1221.30  4978.9 1221.80
  4987.8 1223.58  5005.6 1222.29  5015.7 1223.29  5036.7 1222.64  5072.7 1225.07
  5102.8 1229.09  5115.5 1229.90  5152.6 1232.30  5211.0 1234.81  5368.7 1238.08
#Mann=7,-1,0
  4194.2   0.035       0  4307.1    0.12       0  4944.0    0.07       0
  4974.7    0.05       0  4978.9    0.07       0  5115.5    0.12       0
  5152.6    0.07       0
Bank Sta=4974.7,4978.9
Exp/Cntr=0.3,0.1

Type RM Length L Ch R = 1,18900,470,470,470
BEGIN DESCRIPTION:
PANTHER CREEK 41.0
END DESCRIPTION:
XS GIS Cut Line= 3
      2108174.96     13857075.00      2108975.00     13857025.00
      2109475.00     13856225.00
#Sta/Elev= 30
  4203.1 1254.47  4233.2 1253.69  4273.3 1247.69  4393.5 1245.32  4453.6 1239.15
  4583.9 1232.98  4852.0 1226.47  4914.5 1224.98  4954.6 1220.35  4974.6 1220.47
  4992.6 1219.03  4992.8 1218.53  4996.8 1219.03  5000.7 1219.95  5033.6 1219.56
  5143.3 1222.54  5170.4 1221.06  5216.4 1222.68  5243.5 1221.08  5295.4 1221.23
  5310.7 1222.60  5316.6 1225.32  5337.8 1227.51  5462.5 1230.71  5549.8 1233.64
  5700.5 1236.50  5777.5 1239.72  5779.0 1239.82  5903.9 1244.75  5948.1 1249.42
#Mann=9,-1,0
  4203.1    0.12       0  4852.0    0.07       0  4992.6    0.05       0
  4996.8    0.07       0  5000.7    0.12       0  5462.5    0.07       0
  5549.8    0.12       0  5777.5   0.035       0  5779.0    0.07       0
Bank Sta=4992.6,4996.8
Exp/Cntr=0.3,0.1

Type RM Length L Ch R = 1,18430,421,421,421
BEGIN DESCRIPTION:
PANTHER CREEK 40.0
END DESCRIPTION:
XS GIS Cut Line= 3
      2108498.42     13857363.22      2109225.00     13857375.00
      2109300.52     13856735.62
#Sta/Elev= 30
  4269.0 1235.00  4445.6 1229.16  4515.6 1228.39  4765.6 1222.77  4865.7 1221.50
  4915.7 1220.11  4928.1 1218.76  4935.7 1218.42  4955.7 1213.47  4965.7 1212.26
  4975.7 1212.26  5003.6 1209.78  5003.9 1209.28  5007.6 1209.28  5007.8 1209.78
  5022.1 1210.59  5039.6 1212.17  5096.4 1214.88  5120.8 1215.39  5146.7 1215.72
  5166.9 1217.24  5210.5 1216.71  5219.5 1217.23  5287.7 1220.72  5381.3 1222.54
  5388.4 1223.22  5398.5 1222.90  5414.8 1223.88  5519.3 1226.33  5639.5 1227.80
#Mann=8,-1,0
  4269.0   0.035       0  4928.1    0.07       0  5003.6    0.05       0
  5007.8    0.07       0  5022.1   0.035       0  5120.8    0.07       0
  5219.5    0.12       0  5414.8    0.07       0
Bank Sta=5003.6,5007.8
Exp/Cntr=0.3,0.1

Type RM Length L Ch R = 1,18009,452,452,452
BEGIN DESCRIPTION:
PANTHER CREEK 39.0
END DESCRIPTION:
XS GIS Cut Line= 3
      2108993.22     13857821.56      2109525.00     13857625.00
      2109825.00     13857425.00
#Sta/Elev= 30
  4428.8 1220.57  4505.3 1220.56  4616.5 1218.21  4709.5 1216.92  4722.8 1216.27
  4761.2 1216.45  4793.2 1215.95  4925.0 1208.85  4974.4 1205.20  4981.8 1204.19
  4985.9 1204.06  4993.1 1201.79  5006.4 1201.16  5006.9 1200.66  5011.7 1200.66
  5012.2 1201.16  5018.3 1201.79  5024.3 1201.40  5045.3 1203.25  5054.3 1205.90
  5067.9 1208.97  5096.4 1210.87  5111.4 1210.84  5153.5 1212.38  5162.5 1212.07
  5176.0 1212.72  5198.6 1212.59  5248.1 1213.92  5306.7 1215.86  5356.3 1218.67
#Mann=6,-1,0
  4428.8    0.07       0  4616.5    0.12       0  4709.5    0.07       0
  4981.8    0.12       0  5006.4    0.05       0  5012.2    0.12       0
Bank Sta=5006.4,5012.2
Exp/Cntr=0.3,0.1

Type RM Length L Ch R = 1,17557,461,461,461
BEGIN DESCRIPTION:
PANTHER CREEK 38.0
END DESCRIPTION:
XS GIS Cut Line= 3
      2108904.72     13857878.85      2109725.00     13857975.00
      2110420.21     13857490.11
#Sta/Elev= 30
  4169.6 1221.61  4353.7 1218.80  4448.5 1216.10  4512.2 1213.29  4653.2 1213.11
  4673.3 1214.02  4683.4 1213.10  4869.9 1210.26  4894.8 1209.72  4985.4 1204.39
  4993.0 1202.48  4998.5 1202.48  5009.0 1197.60  5014.9 1197.43  5015.4 1196.93
  5020.7 1197.43  5023.8 1198.82  5044.8 1201.40  5117.4 1203.26  5167.0 1201.62
  5190.5 1203.01  5247.2 1209.75  5297.8 1213.93  5470.6 1219.06  5476.6 1220.23
  5491.5 1220.03  5512.4 1221.81  5527.3 1221.41  5762.4 1227.24  5843.1 1229.21
#Mann=7,-1,0
  4169.6    0.07       0  4448.5    0.12       0  4869.9    0.07       0
  5014.9    0.05       0  5020.7    0.07       0  5167.0    0.12       0
  5762.4    0.07       0
Bank Sta=5014.9,5020.7
Exp/Cntr=0.3,0.1

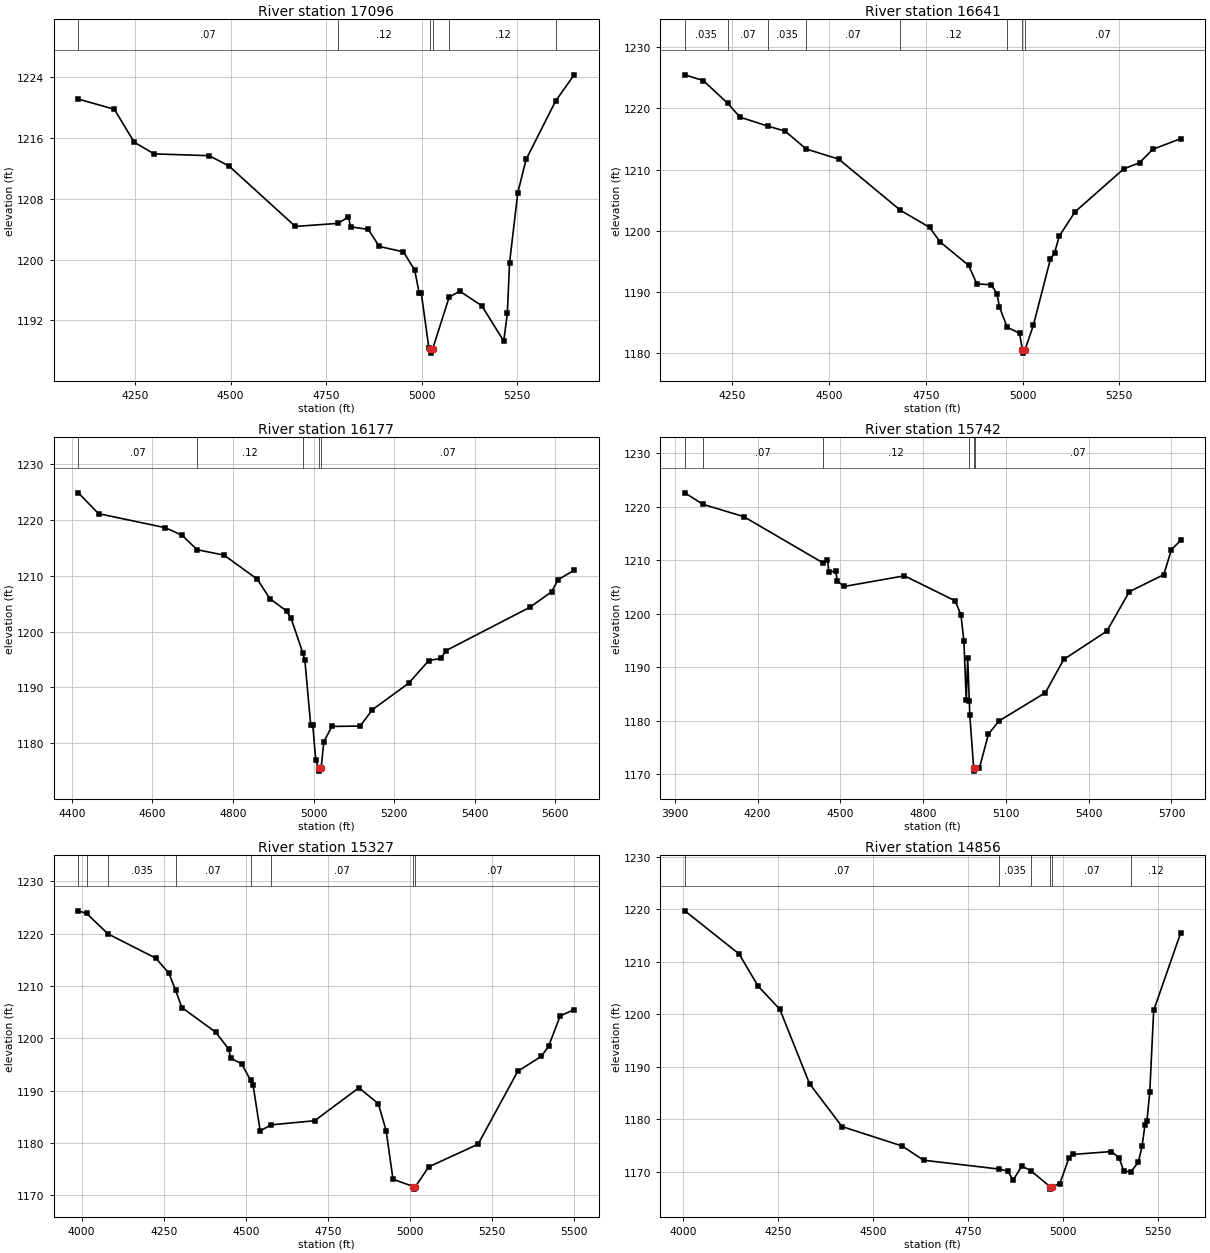
Type RM Length L Ch R = 1,17096,455,455,455
BEGIN DESCRIPTION:
PANTHER CREEK 37.0
END DESCRIPTION:
XS GIS Cut Line= 3
      2108808.32     13857959.57      2109625.00     13858325.00
      2109974.98     13858524.99
#Sta/Elev= 30
  4101.4 1221.07  4195.6 1219.74  4247.5 1215.42  4299.4 1213.88  4444.0 1213.64
  4495.9 1212.28  4669.3 1204.35  4781.3 1204.75  4808.4 1205.61  4813.9 1204.30
  4860.3 1203.96  4889.0 1201.72  4952.3 1201.01  4981.8 1198.62  4993.4 1195.63
  4999.0 1195.63  5019.1 1188.32  5022.7 1188.21  5023.2 1187.71  5028.5 1188.21
  5072.0 1195.06  5099.8 1195.84  5157.4 1193.94  5214.9 1189.29  5224.3 1192.92
  5230.1 1199.57  5251.7 1208.78  5273.3 1213.14  5350.9 1220.84  5399.2 1224.26
#Mann=6,-1,0
  4101.4    0.07       0  4781.3    0.12       0  5022.7    0.05       0
  5028.5    0.12       0  5072.0    0.12       0  5350.9    0.07       0
Bank Sta=5022.7,5028.5
Exp/Cntr=0.3,0.1

Type RM Length L Ch R = 1,16641,464,464,464
BEGIN DESCRIPTION:
PANTHER CREEK 36.0
END DESCRIPTION:
XS GIS Cut Line= 3
      2108675.48     13858217.36      2109425.00     13858675.00
      2109791.34     13858841.77
#Sta/Elev= 30
  4127.7 1225.49  4175.5 1224.55  4238.9 1220.81  4270.3 1218.57  4341.5 1217.12
  4386.5 1216.29  4441.4 1213.36  4525.5 1211.70  4684.5 1203.35  4759.8 1200.56
  4787.2 1198.17  4860.7 1194.34  4882.0 1191.32  4918.8 1191.16  4934.2 1189.73
  4940.1 1187.60  4960.4 1184.22  4992.3 1183.25  4999.9 1180.49  5000.4 1179.99
  5006.1 1180.49  5027.9 1184.51  5071.8 1195.30  5082.8 1196.38  5094.8 1199.09
  5135.4 1203.08  5261.7 1210.12  5302.3 1211.12  5336.4 1213.31  5408.4 1215.05
#Mann=8,-1,0
  4127.7   0.035       0  4238.9    0.07       0  4341.5   0.035       0
  4441.4    0.07       0  4684.5    0.12       0  4960.4    0.07       0
  4999.9    0.05       0  5006.1    0.07       0
Bank Sta=4999.9,5006.1
Exp/Cntr=0.3,0.1

Type RM Length L Ch R = 1,16177,435,435,435
BEGIN DESCRIPTION:
PANTHER CREEK 35.0
END DESCRIPTION:
XS GIS Cut Line= 3
      2108516.63     13858818.94      2109075.00     13858975.00
      2109724.97     13858925.72
#Sta/Elev= 30
  4415.8 1224.85  4466.0 1221.12  4632.2 1218.60  4673.7 1217.23  4710.8 1214.66
  4777.5 1213.70  4860.5 1209.37  4891.7 1205.87  4933.3 1203.68  4944.3 1202.36
  4973.9 1196.07  4978.5 1194.85  4993.0 1183.26  4998.1 1183.26  5005.6 1176.96
  5012.5 1175.50  5013.0 1175.00  5018.8 1175.50  5025.7 1180.30  5045.7 1183.01
  5115.9 1183.07  5146.0 1185.99  5236.3 1190.74  5286.4 1194.81  5316.5 1195.19
  5328.9 1196.58  5537.1 1204.34  5591.6 1207.13  5607.3 1209.29  5647.4 1210.98
#Mann=5,-1,0
  4415.8    0.07       0  4710.8    0.12       0  4973.9    0.07       0
  5012.5    0.05       0  5018.8    0.07       0
Bank Sta=5012.5,5018.8
Exp/Cntr=0.3,0.1

Type RM Length L Ch R = 1,15742,415,415,415
BEGIN DESCRIPTION:
PANTHER CREEK 34.0
END DESCRIPTION:
XS GIS Cut Line= 3
      2108180.69     13858993.42      2109175.00     13859375.00
      2109816.17     13859022.07
#Sta/Elev= 30
  3936.2 1222.56  4002.0 1220.41  4149.8 1218.12  4436.3 1209.50  4453.3 1210.03
  4458.6 1207.80  4483.3 1207.92  4488.7 1206.08  4513.3 1205.07  4732.1 1207.06
  4915.5 1202.41  4936.9 1199.80  4947.7 1194.86  4956.2 1183.80  4961.5 1191.66
  4967.2 1183.69  4969.1 1181.03  4983.1 1171.09  4983.6 1170.59  4989.4 1171.09
  5004.1 1171.20  5036.7 1177.51  5074.6 1179.95  5243.2 1185.24  5309.4 1191.44
  5465.7 1196.73  5547.1 1204.09  5672.1 1207.29  5699.6 1211.95  5733.1 1213.66
#Mann=6,-1,0
  3936.2    0.12       0  4002.0    0.07       0  4436.3    0.12       0
  4967.2    0.07       0  4983.1    0.05       0  4989.4    0.07       0
Bank Sta=4983.1,4989.4
Exp/Cntr=0.3,0.1

Type RM Length L Ch R = 1,15327,471,471,471
BEGIN DESCRIPTION:
PANTHER CREEK 33.0
END DESCRIPTION:
XS GIS Cut Line= 3
      2108500.99     13859891.88      2109475.00     13859625.00
      2109874.99     13859325.00
#Sta/Elev= 30
  3989.9 1224.33  4015.0 1223.84  4080.1 1219.93  4225.7 1215.29  4265.4 1212.45
  4286.2 1209.16  4305.1 1205.86  4408.4 1201.15  4448.1 1197.90  4453.3 1196.22
  4487.8 1195.09  4514.7 1191.94  4522.2 1190.98  4543.6 1182.30  4576.5 1183.46
  4709.5 1184.25  4844.3 1190.54  4903.3 1187.51  4927.2 1182.37  4948.1 1173.08
  5010.1 1171.69  5010.6 1171.19  5016.5 1171.69  5057.1 1175.45  5207.1 1179.76
  5327.9 1193.68  5399.8 1196.55  5421.7 1198.43  5457.1 1204.25  5499.8 1205.47
#Mann=8,-1,0
  3989.9   0.035       0  4015.0    0.07       0  4080.1   0.035       0
  4286.2    0.07       0  4514.7   0.035       0  4576.5    0.07       0
  5010.1    0.05       0  5016.5    0.07       0
Bank Sta=5010.1,5016.5
Exp/Cntr=0.3,0.1

Type RM Length L Ch R = 1,14856,282,282,282
BEGIN DESCRIPTION:
PANTHER CREEK 32.0
END DESCRIPTION:
XS GIS Cut Line= 3
      2109175.01     13860774.99      2109775.00     13859975.00
      2110074.97     13859925.00
#Sta/Elev= 30
  4004.9 1219.71  4147.6 1211.51  4197.6 1205.39  4254.9 1200.96  4333.0 1186.80
  4418.4 1178.65  4576.8 1174.94  4633.0 1172.24  4831.3 1170.56  4854.9 1170.16
  4868.4 1168.43  4891.3 1171.12  4914.4 1170.28  4965.2 1167.24  4965.7 1166.74
  4971.6 1167.24  4991.3 1167.80  5015.0 1172.62  5025.2 1173.34  5126.5 1173.89
  5146.8 1172.74  5159.5 1170.19  5177.6 1170.01  5197.5 1171.81  5207.6 1174.89
  5215.3 1179.00  5220.3 1179.64  5227.9 1185.27  5238.1 1200.74  5309.0 1215.48
#Mann=6,-1,0
  4004.9    0.07       0  4831.3   0.035       0  4914.4    0.07       0
  4965.2    0.05       0  4971.6    0.07       0  5177.6    0.12       0
Bank Sta=4965.2,4971.6
Exp/Cntr=0.3,0.1

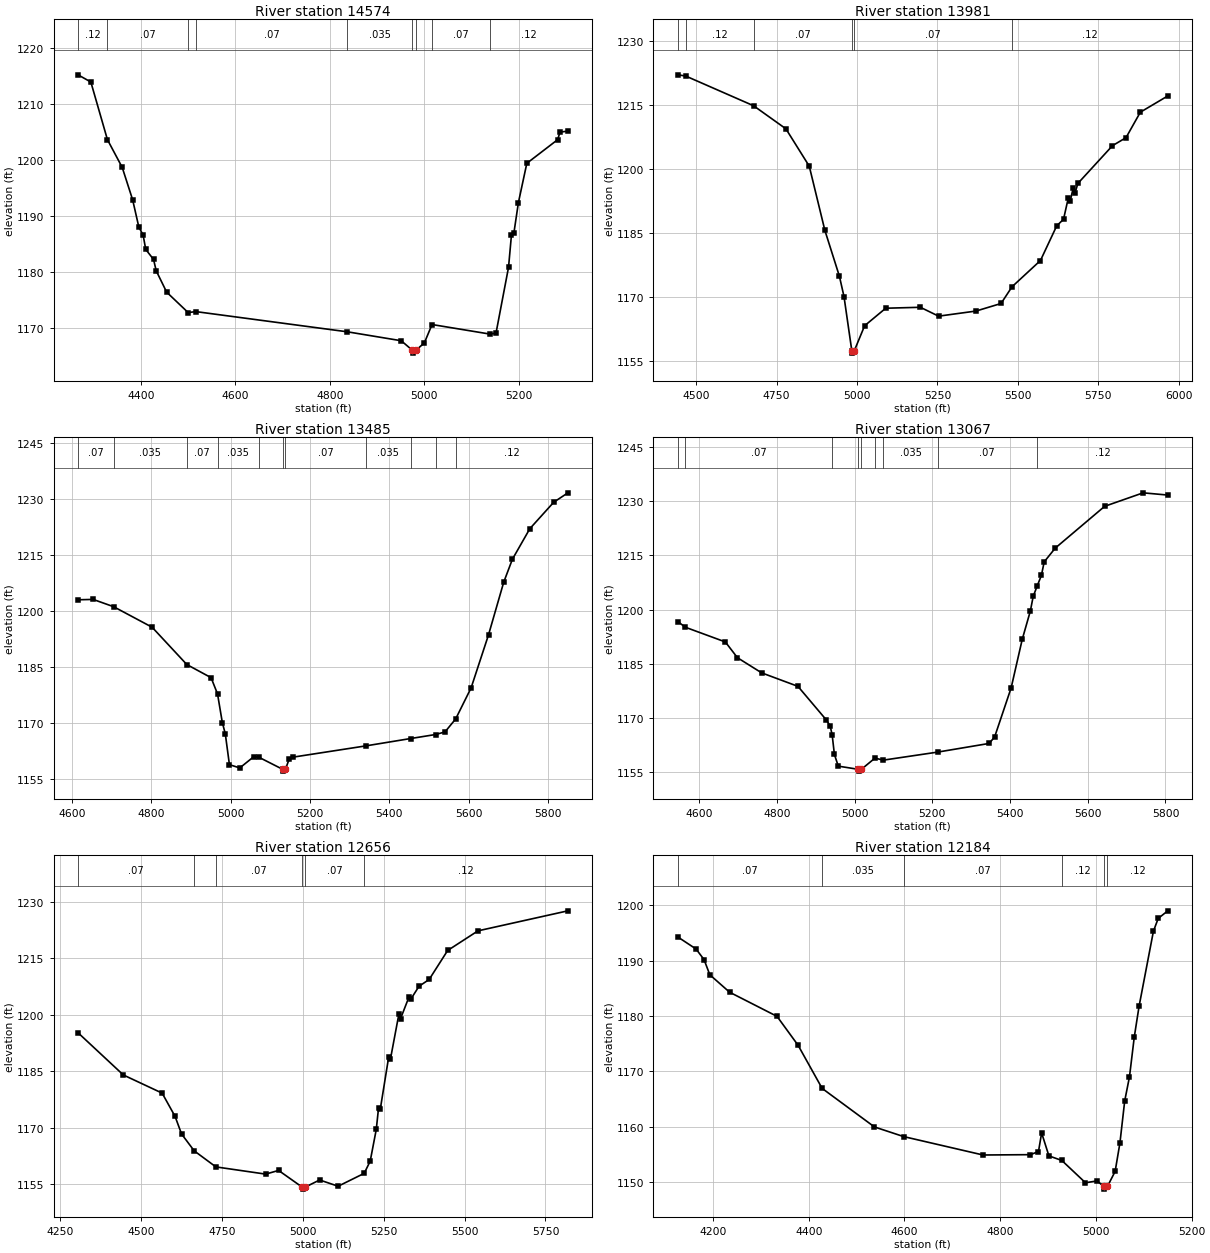
Type RM Length L Ch R = 1,14574,593,593,593
BEGIN DESCRIPTION:
PANTHER CREEK 31.0
END DESCRIPTION:
XS GIS Cut Line= 3
      2109414.89     13860809.08      2109685.76     13860288.17
      2110114.99     13860154.82
#Sta/Elev= 30
  4267.0 1215.14  4294.1 1213.86  4329.2 1203.58  4360.5 1198.63  4382.6 1192.84
  4395.6 1188.01  4404.7 1186.57  4410.3 1184.00  4426.8 1182.22  4432.4 1180.20
  4454.5 1176.39  4499.9 1172.75  4516.7 1172.91  4837.1 1169.31  4950.9 1167.72
  4974.7 1166.01  4975.2 1165.51  4981.9 1166.01  4999.9 1167.34  5016.1 1170.61
  5138.4 1168.91  5151.5 1169.08  5178.0 1180.82  5184.1 1186.52  5189.3 1186.91
  5198.9 1192.36  5216.7 1199.36  5281.8 1203.57  5287.0 1204.93  5303.6 1205.10
#Mann=9,-1,0
  4267.0    0.12       0  4329.2    0.07       0  4499.9   0.035       0
  4516.7    0.07       0  4837.1   0.035       0  4974.7   0.035       0
  4981.9   0.035       0  5016.1    0.07       0  5138.4    0.12       0
Bank Sta=4974.7,4981.9
Exp/Cntr=0.3,0.1

Type RM Length L Ch R = 1,13981,496,496,496
BEGIN DESCRIPTION:
PANTHER CREEK 30.0
END DESCRIPTION:
XS GIS Cut Line= 3
      2109310.94     13861123.64      2109775.00     13860825.00
      2110325.02     13860024.98
#Sta/Elev= 30
  4443.4 1222.07  4467.5 1221.79  4678.5 1214.82  4779.0 1209.41  4851.6 1200.65
  4900.1 1185.61  4945.4 1174.82  4959.6 1170.08  4984.0 1157.31  4984.5 1156.81
  4991.3 1157.31  5023.7 1163.23  5089.3 1167.34  5196.9 1167.56  5253.7 1165.48
  5370.1 1166.68  5447.8 1168.45  5481.9 1172.37  5570.3 1178.53  5621.0 1186.68
  5642.0 1188.19  5656.9 1193.23  5663.0 1192.53  5671.8 1195.45  5677.9 1194.43
  5686.7 1196.61  5794.2 1205.46  5836.2 1207.33  5880.8 1213.31  5966.1 1217.12
#Mann=6,-1,0
  4443.4    0.07       0  4467.5    0.12       0  4678.5    0.07       0
  4984.0    0.05       0  4991.3    0.07       0  5481.9    0.12       0
Bank Sta=4984,4991.3
Exp/Cntr=0.3,0.1

Type RM Length L Ch R = 1,13485,418,418,418
BEGIN DESCRIPTION:
PANTHER CREEK 29.0
END DESCRIPTION:
XS GIS Cut Line= 3
      2109839.57     13861433.55      2110125.00     13861175.00
      2110874.98     13860775.01
#Sta/Elev= 30
  4615.1 1203.03  4653.2 1203.13  4704.8 1201.18  4801.9 1195.68  4889.4 1185.69
  4950.5 1182.18  4966.8 1177.83  4978.9 1170.17  4986.4 1167.14  4996.8 1158.88
  5022.9 1158.01  5057.9 1160.99  5070.5 1160.90  5130.8 1157.65  5131.3 1157.15
  5138.1 1157.65  5147.6 1160.42  5156.4 1160.88  5340.2 1163.90  5453.8 1165.88
  5516.4 1166.95  5540.3 1167.64  5567.3 1171.14  5606.2 1179.45  5650.1 1193.65
  5688.4 1207.74  5710.3 1213.89  5754.2 1222.06  5814.4 1229.14  5850.2 1231.67
#Mann=11,-1,0
  4615.1    0.07       0  4704.8   0.035       0  4889.4    0.07       0
  4966.8   0.035       0  5070.5    0.07       0  5130.8   0.035       0
  5138.1    0.07       0  5340.2   0.035       0  5453.8    0.07       0
  5516.4   0.035       0  5567.3    0.12       0
Bank Sta=5130.8,5138.1
Exp/Cntr=0.3,0.1

Type RM Length L Ch R = 1,13067,411,411,411
BEGIN DESCRIPTION:
PANTHER CREEK 28.0
END DESCRIPTION:
XS GIS Cut Line= 3
      2110037.46     13861496.05      2110475.00     13861375.00
      2111063.55     13860824.15
#Sta/Elev= 30
  4545.8 1196.70  4564.4 1195.16  4667.8 1191.07  4698.9 1186.71  4761.2 1182.52
  4854.5 1178.79  4927.1 1169.55  4937.5 1167.81  4942.6 1165.32  4948.3 1159.95
  4958.3 1156.72  5009.8 1155.84  5010.3 1155.34  5017.7 1155.84  5052.6 1158.94
  5074.3 1158.38  5213.7 1160.60  5346.4 1163.00  5360.5 1164.81  5403.0 1178.39
  5431.4 1191.75  5452.4 1199.66  5459.7 1203.68  5469.5 1206.44  5480.7 1209.46
  5488.0 1213.23  5516.3 1217.02  5643.5 1228.59  5742.5 1232.32  5805.9 1231.70
#Mann=9,-1,0
  4545.8   0.035       0  4564.4    0.07       0  4942.6   0.035       0
  5009.8   0.035       0  5017.7   0.035       0  5052.6    0.07       0
  5074.3   0.035       0  5213.7    0.07       0  5469.5    0.12       0
Bank Sta=5009.8,5017.7
Exp/Cntr=0.3,0.1

Type RM Length L Ch R = 1,12656,472,472,472
BEGIN DESCRIPTION:
PANTHER CREEK 27.0
END DESCRIPTION:
XS GIS Cut Line= 3
      2110075.02     13861625.00      2110775.00     13861625.00
      2111545.32     13861360.62
#Sta/Elev= 30
  4305.0 1195.22  4445.0 1184.00  4565.0 1179.17  4605.0 1172.98  4625.0 1168.32
  4664.1 1163.83  4731.1 1159.56  4885.0 1157.64  4925.0 1158.62  4998.5 1154.15
  4999.0 1153.65  5006.5 1154.15  5051.9 1156.08  5109.1 1154.42  5189.6 1157.84
  5208.2 1161.08  5227.0 1169.51  5234.1 1175.27  5239.4 1174.90  5265.4 1188.78
  5270.7 1188.16  5296.7 1200.08  5302.0 1198.94  5327.9 1204.68  5333.2 1204.07
  5359.2 1207.58  5390.5 1209.38  5447.7 1217.09  5541.5 1222.31  5819.4 1227.63
#Mann=6,-1,0
  4305.0    0.07       0  4664.1   0.035       0  4731.1    0.07       0
  4998.5    0.05       0  5006.5    0.07       0  5189.6    0.12       0
Bank Sta=4998.5,5006.5
Exp/Cntr=0.3,0.1

Type RM Length L Ch R = 1,12184,434,434,434
BEGIN DESCRIPTION:
PANTHER CREEK 26.0
END DESCRIPTION:
XS GIS Cut Line= 3
      2110075.03     13861675.01      2110875.00     13862025.00
      2111025.02     13862025.00
#Sta/Elev= 30
  4126.8 1194.25  4164.6 1192.09  4181.3 1190.18  4193.4 1187.43  4234.7 1184.28
  4333.8 1179.91  4377.8 1174.68  4428.0 1166.89  4537.3 1159.92  4598.2 1158.18
  4764.1 1154.85  4863.2 1154.91  4879.9 1155.48  4886.5 1158.84  4901.7 1154.69
  4928.7 1153.86  4978.1 1149.83  5002.5 1150.17  5015.9 1149.18  5016.4 1148.68
  5024.0 1149.18  5040.0 1151.88  5050.0 1157.01  5060.0 1164.62  5070.0 1169.00
  5080.0 1176.18  5090.0 1181.73  5120.0 1195.31  5130.0 1197.62  5150.0 1198.99
#Mann=6,-1,0
  4126.8    0.07       0  4428.0   0.035       0  4598.2    0.07       0
  4928.7    0.12       0  5015.9    0.05       0  5024.0    0.12       0
Bank Sta=5015.9,5024
Exp/Cntr=0.3,0.1

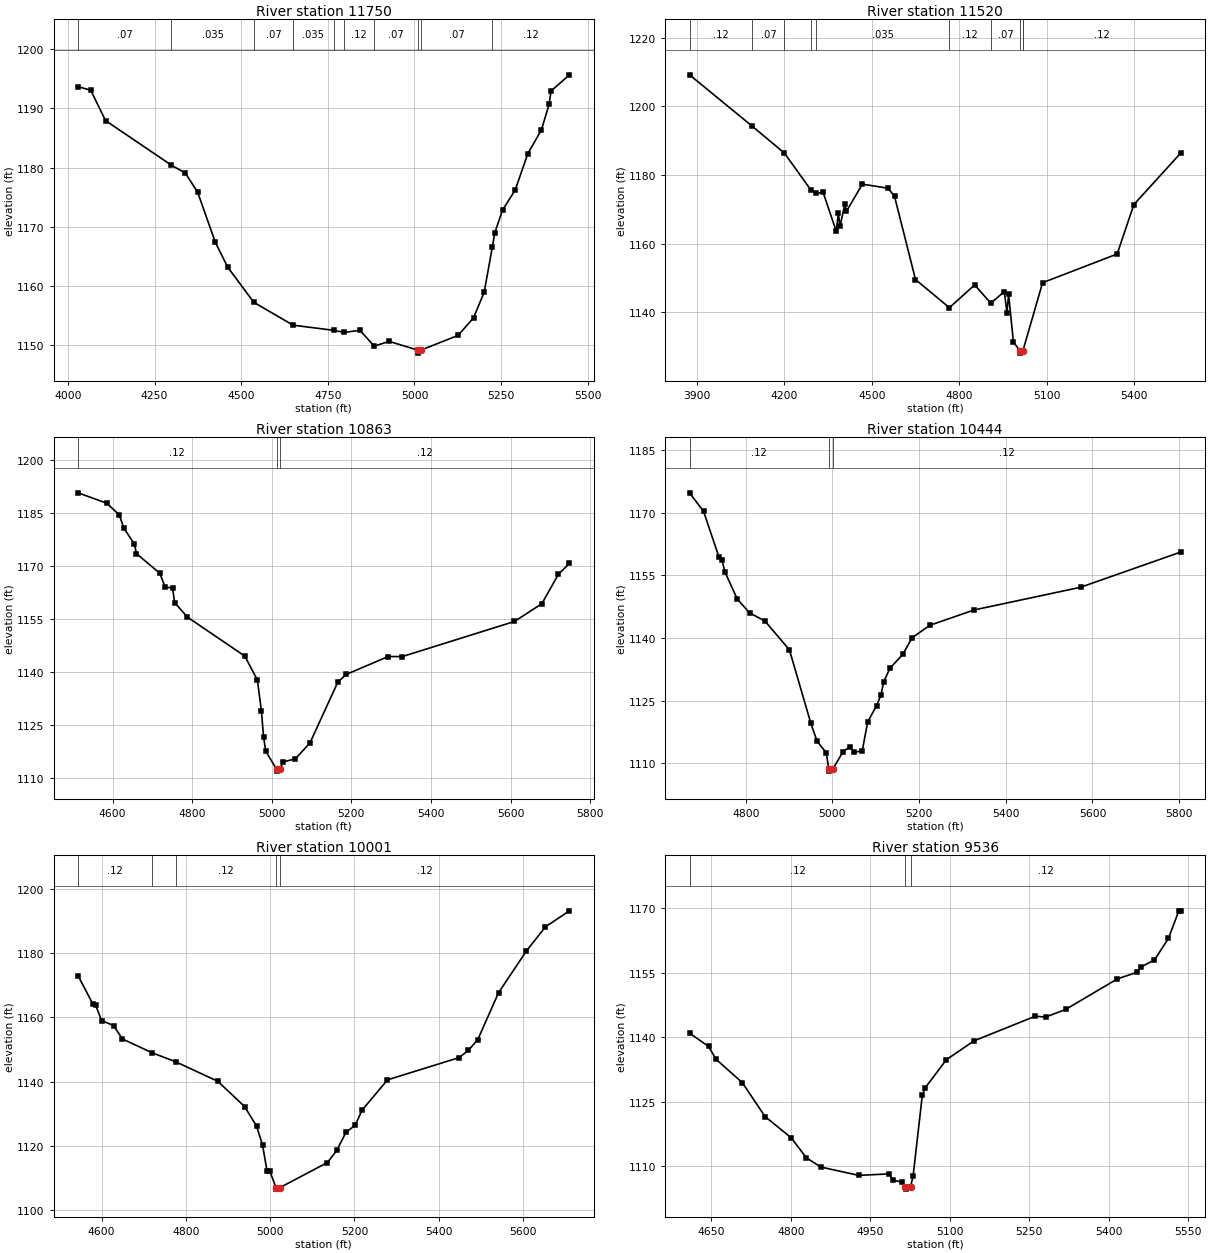
Type RM Length L Ch R = 1,11750,230,230,230
BEGIN DESCRIPTION:
PANTHER CREEK 25.0
END DESCRIPTION:
XS GIS Cut Line= 3
      2109975.00     13861875.00      2110775.00     13862425.00
      2111174.97     13862225.02
#Sta/Elev= 30
  4029.2 1193.68  4065.6 1193.08  4108.4 1187.95  4298.4 1180.42  4338.4 1179.10
  4374.2 1175.86  4425.0 1167.43  4460.8 1163.21  4536.3 1157.26  4649.7 1153.40
  4766.8 1152.53  4797.6 1152.18  4842.3 1152.54  4883.9 1149.87  4927.2 1150.66
  5010.0 1149.18  5010.5 1148.68  5018.1 1149.18  5125.8 1151.67  5170.5 1154.64
  5201.3 1158.99  5224.7 1166.57  5232.0 1169.05  5254.4 1172.87  5290.7 1176.22
  5327.0 1182.35  5366.2 1186.36  5388.5 1190.69  5394.1 1192.94  5447.2 1195.68
#Mann=10,-1,0
  4029.2    0.07       0  4298.4   0.035       0  4536.3    0.07       0
  4649.7   0.035       0  4766.8    0.07       0  4797.6    0.12       0
  4883.9    0.07       0  5010.0    0.05       0  5018.1    0.07       0
  5224.7    0.12       0
Bank Sta=5010,5018.1
Exp/Cntr=0.3,0.1

Type RM Length L Ch R = 1,11520,657,657,657
BEGIN DESCRIPTION:
PANTHER CREEK 24.0
END DESCRIPTION:
XS GIS Cut Line= 3
      2109779.71     13863178.31      2110779.69     13862652.28
      2111217.21     13862311.12
#Sta/Elev= 30
  3875.4 1209.21  4091.2 1194.18  4200.6 1186.42  4290.8 1175.75  4309.6 1174.64
  4333.3 1175.01  4378.5 1163.63  4385.7 1168.81  4391.4 1165.11  4407.8 1171.46
  4413.4 1169.45  4468.2 1177.36  4556.4 1176.17  4578.4 1173.78  4650.2 1149.57
  4766.5 1141.37  4853.1 1148.00  4908.5 1142.67  4954.8 1146.06  4963.8 1139.83
  4969.5 1145.27  4985.9 1131.39  5009.6 1128.63  5010.1 1128.13  5017.8 1128.63
  5018.0 1128.67  5086.0 1148.65  5341.7 1157.01  5399.0 1171.41  5560.1 1186.46
#Mann=10,-1,0
  3875.4    0.12       0  4091.2    0.07       0  4200.6   0.035       0
  4290.8    0.07       0  4309.6   0.035       0  4766.5    0.12       0
  4908.5    0.07       0  5009.6    0.05       0  5017.8    0.07       0
  5018.0    0.12       0
Bank Sta=5009.6,5017.8
Exp/Cntr=0.3,0.1

Type RM Length L Ch R = 1,10863,419,419,419
BEGIN DESCRIPTION:
PANTHER CREEK 23.0
END DESCRIPTION:
XS GIS Cut Line= 3
      2110516.70     13863324.15      2110975.00     13863175.00
      2111238.01     13862470.02
#Sta/Elev= 30
  4513.5 1190.77  4585.3 1187.83  4616.9 1184.53  4628.2 1180.83  4654.9 1176.20
  4660.2 1173.53  4718.8 1167.97  4732.5 1163.97  4750.7 1163.88  4756.0 1159.67
  4787.9 1155.57  4932.4 1144.49  4963.9 1137.73  4974.2 1128.81  4979.5 1121.57
  4984.9 1117.57  5012.2 1112.40  5012.7 1111.90  5021.4 1112.40  5027.5 1114.48
  5059.5 1115.39  5096.2 1119.94  5166.2 1137.17  5187.6 1139.33  5292.4 1144.37
  5328.1 1144.37  5609.9 1154.32  5678.5 1159.34  5720.4 1167.69  5747.9 1170.78
#Mann=3,-1,0
  4513.5    0.12       0  5012.2    0.05       0  5021.4    0.12       0
Bank Sta=5012.2,5021.4
Exp/Cntr=0.3,0.1

Type RM Length L Ch R = 1,10444,443,443,443
BEGIN DESCRIPTION:
PANTHER CREEK 22.0
END DESCRIPTION:
XS GIS Cut Line= 3
      2111087.00     13863602.78      2111325.00     13863375.00
      2111492.93     13862588.56
#Sta/Elev= 30
  4670.3 1174.82  4702.7 1170.36  4737.9 1159.50  4745.1 1158.68  4752.1 1155.82
  4780.4 1149.34  4808.7 1146.04  4844.2 1144.07  4900.8 1137.15  4950.2 1119.53
  4964.4 1115.27  4985.7 1112.46  4991.6 1108.56  4992.1 1108.06  5001.0 1108.56
  5024.5 1112.75  5040.6 1113.89  5050.9 1112.54  5068.9 1112.99  5081.5 1119.95
  5102.0 1123.75  5112.2 1126.44  5118.4 1129.53  5132.7 1132.73  5162.8 1136.13
  5183.8 1140.06  5224.7 1143.04  5326.9 1146.72  5572.4 1152.16  5803.9 1160.62
#Mann=3,-1,0
  4670.3    0.12       0  4991.6    0.05       0  5001.0    0.12       0
Bank Sta=4991.6,5001
Exp/Cntr=0.3,0.1

Type RM Length L Ch R = 1,10001,465,465,465
BEGIN DESCRIPTION:
PANTHER CREEK 21.0
END DESCRIPTION:
XS GIS Cut Line= 3
      2111355.17     13863943.99      2111675.00     13863625.00
      2112010.75     13862994.76
#Sta/Elev= 30
  4544.4 1172.97  4578.9 1164.32  4586.0 1163.81  4600.1 1159.03  4628.4 1157.48
  4649.6 1153.29  4720.5 1148.96  4776.0 1146.18  4875.9 1140.10  4939.5 1132.22
  4967.8 1126.15  4982.0 1120.25  4992.6 1112.27  4998.9 1112.27  5013.9 1107.00
  5014.4 1106.50  5023.7 1107.00  5136.0 1114.79  5158.0 1118.54  5180.0 1124.21
  5201.9 1126.41  5218.2 1131.10  5278.5 1140.55  5448.5 1147.49  5470.5 1149.77
  5492.5 1153.02  5542.0 1167.70  5608.0 1180.68  5653.3 1188.24  5710.2 1193.22
#Mann=5,-1,0
  4544.4    0.12       0  4720.5   0.035       0  4776.0    0.12       0
  5013.9    0.05       0  5023.7    0.12       0
Bank Sta=5013.9,5023.7
Exp/Cntr=0.3,0.1

Type RM Length L Ch R = 1,9536,439,439,439
BEGIN DESCRIPTION:
PANTHER CREEK 20.0
END DESCRIPTION:
XS GIS Cut Line= 3
      2111825.00     13863925.00      2112125.00     13863675.00
      2112284.90     13863162.69
#Sta/Elev= 30
  4609.1 1140.97  4644.9 1137.89  4659.2 1134.89  4708.7 1129.45  4751.6 1121.57
  4801.1 1116.60  4829.7 1111.95  4857.1 1109.80  4928.7 1107.87  4985.9 1108.22
  4992.5 1106.83  5010.1 1106.27  5016.2 1105.17  5016.7 1104.67  5026.1 1105.17
  5031.0 1107.70  5048.4 1126.54  5053.6 1128.21  5093.9 1134.80  5145.8 1139.17
  5261.5 1144.91  5281.1 1144.72  5318.8 1146.48  5416.3 1153.59  5454.0 1155.15
  5460.5 1156.35  5486.5 1158.00  5512.9 1163.02  5532.5 1169.44  5536.3 1169.44
#Mann=3,-1,0
  4609.1    0.12       0  5016.2    0.05       0  5026.1    0.12       0
Bank Sta=5016.2,5026.1
Exp/Cntr=0.3,0.1

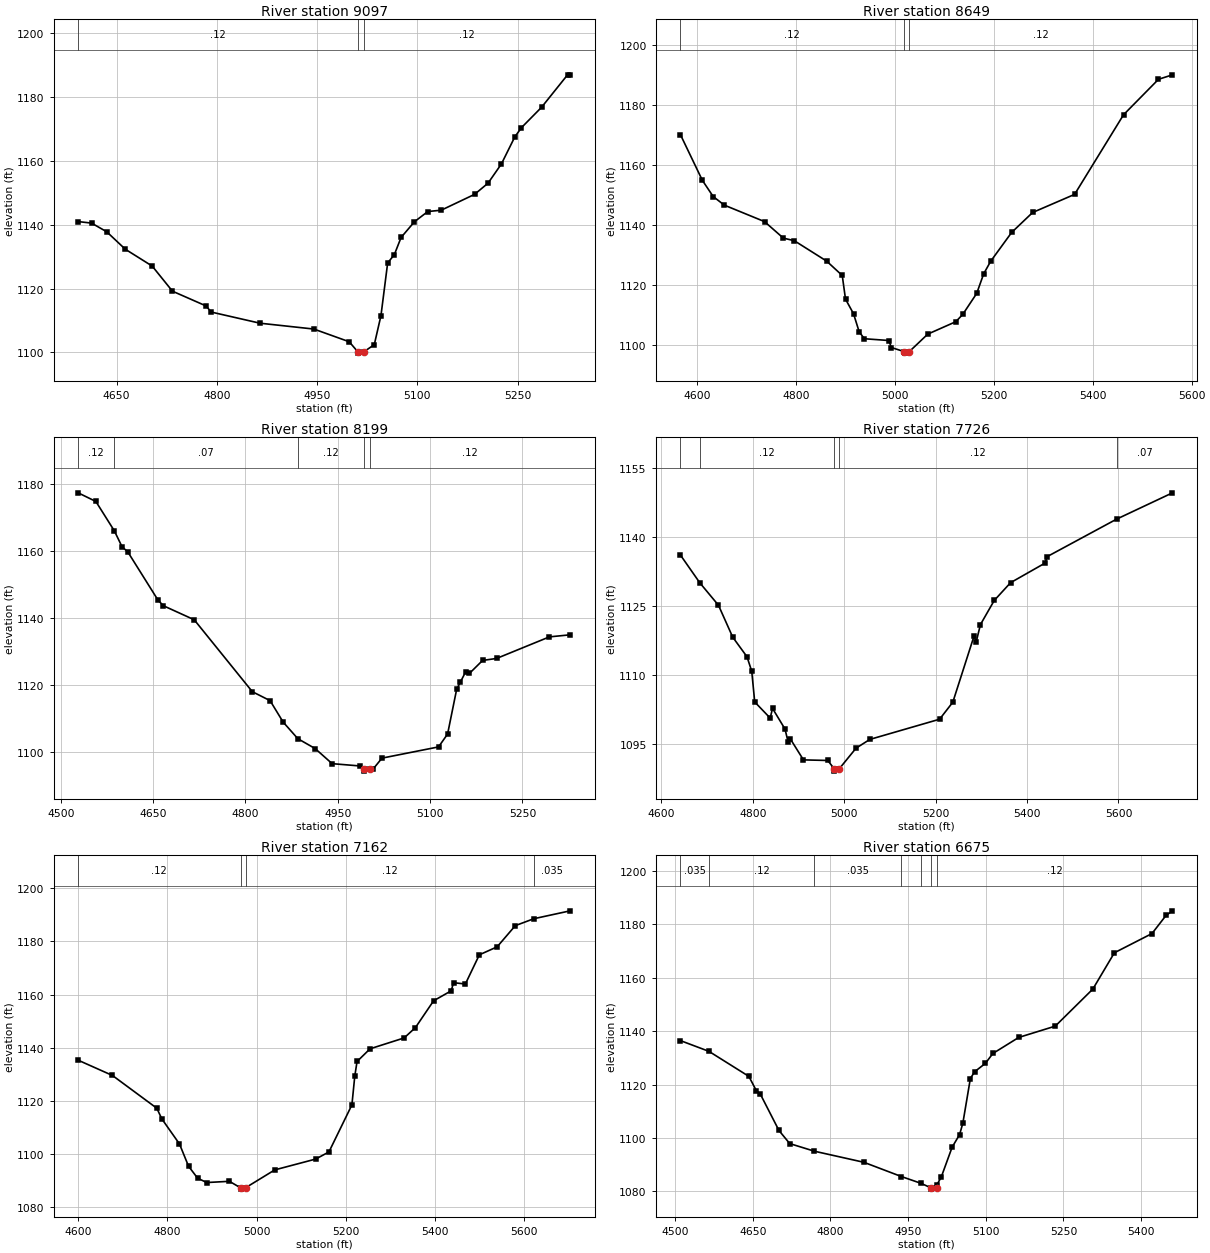
Type RM Length L Ch R = 1,9097,448,448,448
BEGIN DESCRIPTION:
PANTHER CREEK 19.0
END DESCRIPTION:
XS GIS Cut Line= 3
      2111875.02     13864025.00      2112275.00     13863975.00
      2112607.85     13863988.22
#Sta/Elev= 30
  4592.4 1141.00  4612.5 1140.52  4635.2 1137.80  4662.9 1132.35  4703.2 1127.06
  4733.5 1119.20  4783.9 1114.57  4791.4 1112.67  4864.5 1109.17  4945.1 1107.34
  4998.0 1103.36  5010.5 1100.30  5011.0 1099.80  5020.5 1100.30  5035.5 1102.46
  5045.5 1111.57  5055.5 1128.04  5065.5 1130.64  5075.6 1136.03  5095.6 1140.95
  5115.6 1144.15  5135.6 1144.56  5185.6 1149.53  5205.7 1153.03  5225.7 1159.05
  5245.7 1167.50  5255.7 1170.42  5285.7 1176.78  5324.7 1186.96  5328.6 1186.96
#Mann=3,-1,0
  4592.4    0.12       0  5010.5    0.05       0  5020.5    0.12       0
Bank Sta=5010.5,5020.5
Exp/Cntr=0.3,0.1

Type RM Length L Ch R = 1,8649,450,450,450
BEGIN DESCRIPTION:
PANTHER CREEK 18.0
END DESCRIPTION:
XS GIS Cut Line= 3
      2111896.87     13864628.85      2112275.00     13864425.00
      2112675.03     13864024.97
#Sta/Elev= 30
  4565.9 1170.15  4610.3 1154.90  4632.2 1149.51  4654.7 1146.65  4736.0 1141.16
  4774.1 1135.65  4796.0 1134.81  4861.7 1127.98  4893.2 1123.19  4899.8 1115.31
  4916.0 1110.44  4927.4 1104.44  4937.9 1102.10  4987.4 1101.51  4992.6 1099.16
  5018.7 1097.80  5019.2 1097.30  5028.8 1097.80  5066.2 1103.64  5122.8 1107.77
  5136.9 1110.20  5165.2 1117.22  5179.3 1123.75  5193.5 1127.95  5235.9 1137.55
  5278.3 1144.20  5363.2 1150.24  5462.2 1176.79  5532.9 1188.62  5561.2 1190.11
#Mann=3,-1,0
  4565.9    0.12       0  5018.7    0.05       0  5028.8    0.12       0
Bank Sta=5018.7,5028.8
Exp/Cntr=0.3,0.1

Type RM Length L Ch R = 1,8199,473,473,473
BEGIN DESCRIPTION:
PANTHER CREEK 17.0
END DESCRIPTION:
XS GIS Cut Line= 3
      2112125.04     13865024.98      2112525.00     13864775.00
      2112790.03     13864582.02
#Sta/Elev= 30
  4528.1 1177.34  4556.9 1174.76  4587.0 1165.96  4599.4 1161.25  4608.8 1159.70
  4657.8 1145.33  4666.6 1143.63  4716.7 1139.44  4811.1 1117.97  4840.0 1115.29
  4861.2 1108.89  4885.1 1103.93  4913.1 1101.00  4940.8 1096.48  4986.2 1095.79
  4991.8 1094.75  4992.3 1094.25  5001.9 1094.75  5007.1 1094.81  5021.8 1098.13
  5113.7 1101.48  5128.4 1105.32  5143.1 1118.64  5149.3 1120.89  5157.8 1123.90
  5164.0 1123.44  5185.3 1127.30  5208.0 1127.89  5293.8 1134.33  5327.6 1134.95
#Mann=5,-1,0
  4528.1    0.12       0  4587.0    0.07       0  4885.1    0.12       0
  4991.8    0.05       0  5001.9    0.12       0
Bank Sta=4991.8,5001.9
Exp/Cntr=0.3,0.1

Type RM Length L Ch R = 1,7726,564,564,564
BEGIN DESCRIPTION:
PANTHER CREEK 16.0
END DESCRIPTION:
XS GIS Cut Line= 3
      2112975.00     13865375.01      2112875.00     13865025.00
      2112964.36     13864318.15
#Sta/Elev= 30
  4641.7 1136.06  4684.3 1130.01  4724.9 1125.17  4756.1 1118.25  4787.3 1114.00
  4797.7 1110.85  4804.2 1104.20  4838.0 1100.70  4843.2 1102.79  4870.5 1098.31
  4877.0 1095.60  4882.2 1096.17  4910.8 1091.63  4964.1 1091.50  4978.1 1089.69
  4978.6 1089.19  4989.1 1089.69  5025.9 1094.17  5056.1 1096.07  5208.7 1100.45
  5237.6 1104.14  5283.9 1118.45  5288.9 1117.28  5298.0 1120.97  5328.3 1126.22
  5364.0 1130.07  5439.1 1134.30  5444.2 1135.73  5596.1 1143.86  5718.2 1149.56
#Mann=5,-1,0
  4641.7   0.035       0  4684.3    0.12       0  4978.1    0.05       0
  4989.1    0.12       0  5596.1    0.07       0
Bank Sta=4978.1,4989.1
Exp/Cntr=0.3,0.1

Type RM Length L Ch R = 1,7162,487,487,487
BEGIN DESCRIPTION:
PANTHER CREEK 15.0
END DESCRIPTION:
XS GIS Cut Line= 2
      2113286.42     13865468.29      2113488.02     13864384.07
#Sta/Elev= 30
  4600.0 1135.28  4676.9 1129.53  4776.3 1117.20  4787.6 1113.18  4827.1 1103.76
  4847.5 1095.35  4867.8 1090.87  4888.1 1089.23  4939.0 1089.69  4964.0 1087.25
  4964.5 1086.75  4975.1 1087.25  5040.7 1093.99  5132.3 1098.06  5162.1 1100.75
  5213.6 1118.47  5220.0 1129.25  5225.1 1134.79  5254.3 1139.57  5330.7 1143.66
  5356.0 1147.56  5396.7 1157.64  5436.2 1161.40  5441.3 1164.45  5467.9 1163.96
  5499.2 1174.94  5539.1 1177.95  5579.8 1185.92  5621.3 1188.53  5702.8 1191.50
#Mann=4,-1,0
  4600.0    0.12       0  4964.0    0.05       0  4975.1    0.12       0
  5621.3   0.035       0
Bank Sta=4964,4975.1
Exp/Cntr=0.3,0.1

Type RM Length L Ch R = 1,6675,294,294,294
BEGIN DESCRIPTION:
PANTHER CREEK 14.0
END DESCRIPTION:
XS GIS Cut Line= 2
      2113461.47     13865597.46      2114040.34     13864843.68
#Sta/Elev= 30
  4510.2 1136.47  4565.2 1132.45  4642.4 1123.06  4656.9 1117.66  4664.6 1116.38
  4700.5 1102.78  4721.3 1097.87  4769.0 1095.01  4864.5 1090.86  4937.1 1085.51
  4974.8 1082.98  4993.9 1081.30  4994.4 1080.80  5005.1 1081.30  5005.8 1082.51
  5014.0 1085.33  5034.9 1096.49  5049.4 1101.25  5055.7 1105.53  5070.2 1122.26
  5078.4 1124.80  5099.2 1127.94  5113.7 1131.65  5163.6 1137.66  5234.2 1141.90
  5306.8 1155.80  5348.4 1169.40  5421.0 1176.60  5448.1 1183.38  5460.6 1185.12
#Mann=7,-1,0
  4510.2   0.035       0  4565.2    0.12       0  4769.0   0.035       0
  4937.1    0.07       0  4974.8    0.12       0  4993.9    0.05       0
  5005.1    0.12       0
Bank Sta=4993.9,5005.1
Exp/Cntr=0.3,0.1