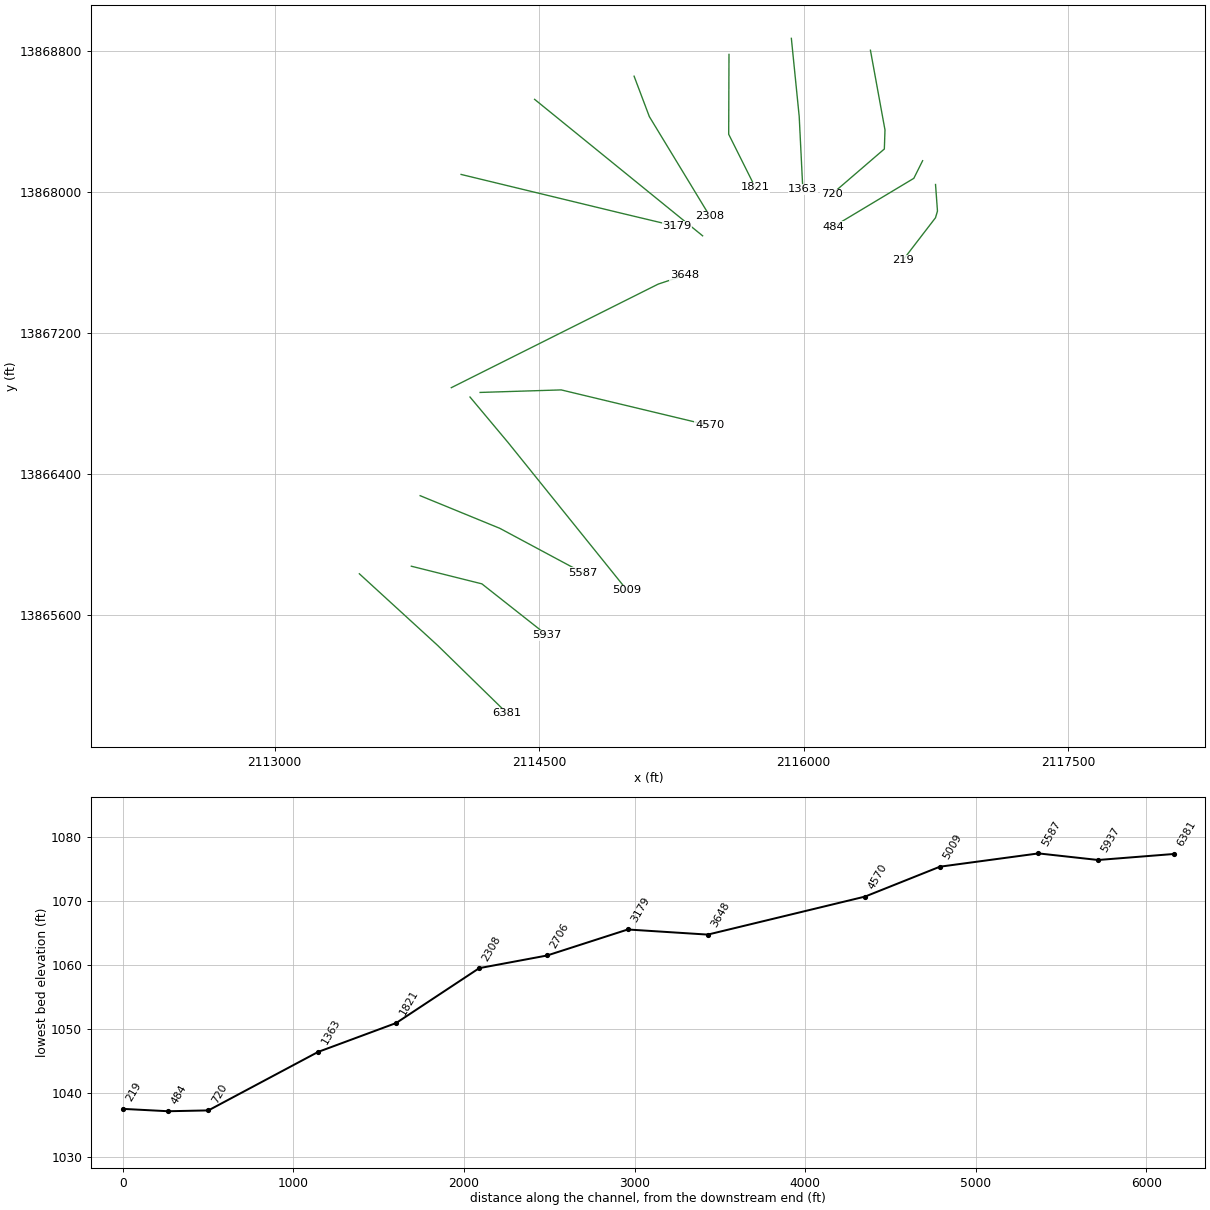
HEC-RAS study PANTHER CREEK.prj: PANTHER CREEK Base Level Engineering

--- PANTHER CREEK.g01 (geometry) --- (continued)

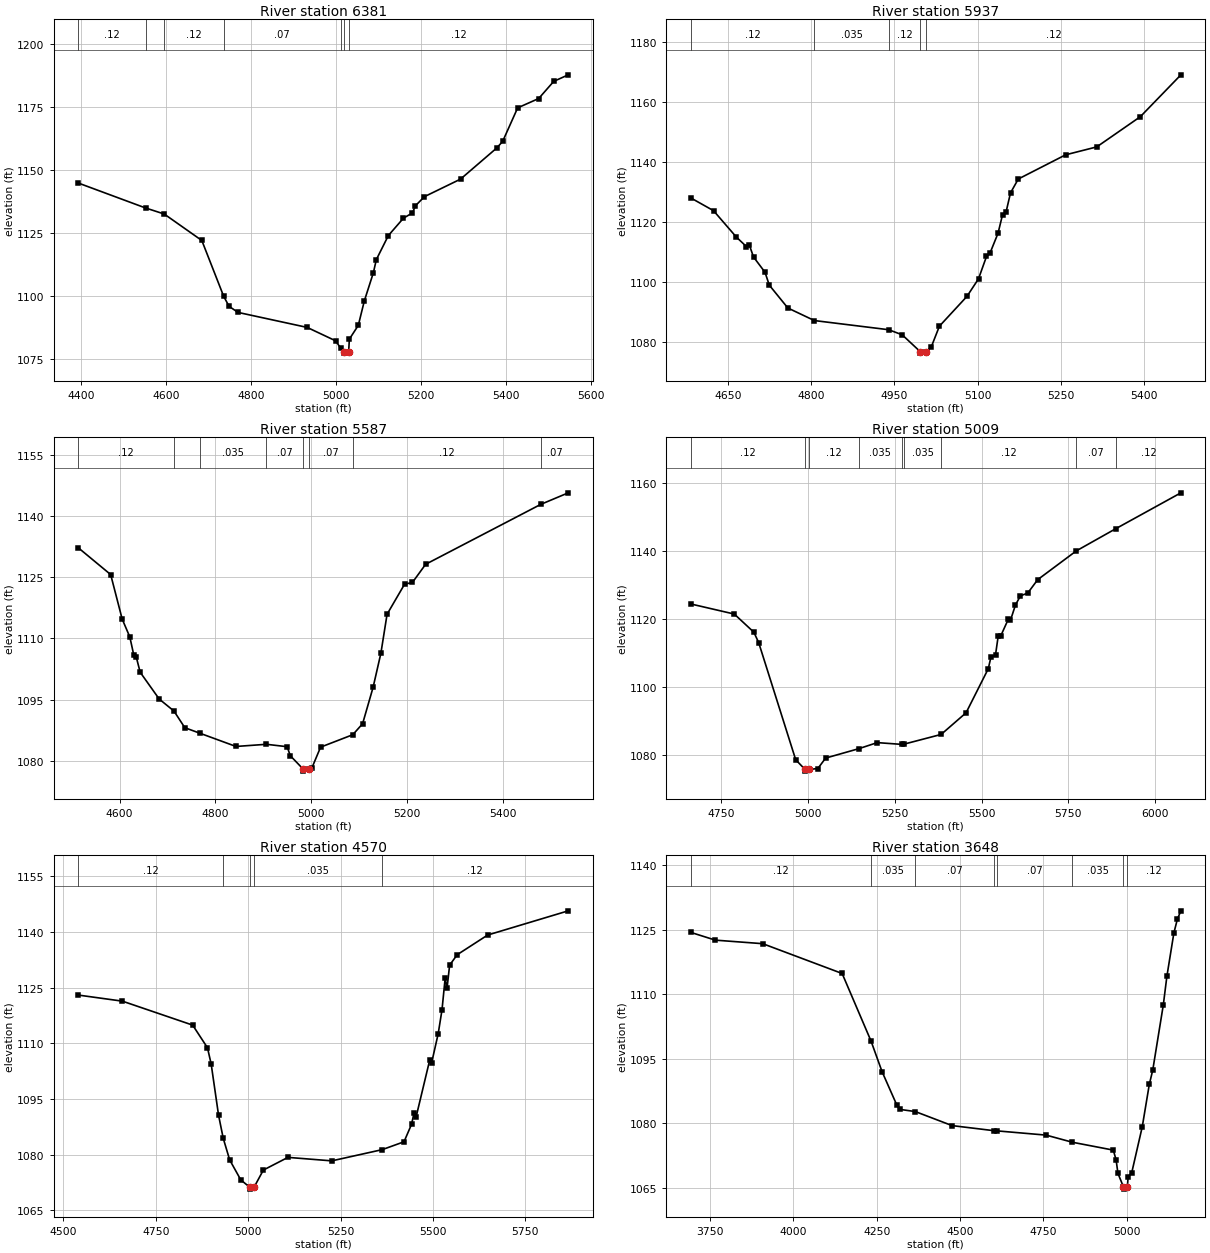
Type RM Length L Ch R = 1,6381,444,444,444
BEGIN DESCRIPTION:
PANTHER CREEK 13.0
END DESCRIPTION:
XS GIS Cut Line= 3
      2113480.19     13865831.99      2113925.00     13865425.00
      2114318.76     13865040.30
#Sta/Elev= 30
  4392.3 1144.80  4551.2 1134.88  4594.9 1132.50  4683.5 1122.00  4735.0 1099.85
  4747.6 1095.91  4768.6 1093.50  4931.4 1087.55  4998.7 1082.21  5010.3 1079.26
  5017.8 1077.86  5018.3 1077.36  5029.0 1077.86  5030.6 1082.90  5051.7 1088.37
  5065.8 1098.03  5087.1 1109.21  5094.1 1114.42  5122.4 1123.96  5157.9 1130.84
  5179.0 1132.93  5186.2 1135.78  5207.3 1139.37  5292.2 1146.32  5377.0 1158.60
  5391.2 1161.23  5426.6 1174.56  5476.1 1178.26  5511.5 1185.06  5545.7 1187.65
#Mann=7,-1,0
  4392.3    0.12       0  4551.2   0.035       0  4594.9    0.12       0
  4735.0    0.07       0  5010.3    0.12       0  5017.8    0.05       0
  5029.0    0.12       0
Bank Sta=5017.8,5029
Exp/Cntr=0.3,0.1

Type RM Length L Ch R = 1,5937,350,350,350
BEGIN DESCRIPTION:
PANTHER CREEK 12.0
END DESCRIPTION:
XS GIS Cut Line= 3
      2113775.04     13865874.99      2114175.00     13865775.00
      2114545.28     13865483.04
#Sta/Elev= 30
  4582.9 1128.10  4624.1 1123.83  4665.3 1115.03  4683.4 1111.89  4688.5 1112.48
  4696.2 1108.42  4716.9 1103.34  4724.6 1099.05  4758.1 1091.44  4805.9 1087.26
  4939.9 1084.21  4964.2 1082.52  4996.7 1076.92  4997.2 1076.42  5008.0 1076.92
  5016.8 1078.54  5031.3 1085.39  5081.0 1095.31  5101.8 1101.15  5116.2 1108.59
  5122.6 1109.74  5137.0 1116.32  5145.1 1122.45  5151.5 1123.40  5159.5 1129.75
  5173.5 1134.37  5258.9 1142.43  5315.0 1145.06  5393.6 1155.12  5466.7 1169.05
#Mann=5,-1,0
  4582.9    0.12       0  4805.9   0.035       0  4939.9    0.12       0
  4996.7    0.05       0  5008.0    0.12       0
Bank Sta=4996.7,5008
Exp/Cntr=0.3,0.1

Type RM Length L Ch R = 1,5587,578,578,578
BEGIN DESCRIPTION:
PANTHER CREEK 11.0
END DESCRIPTION:
XS GIS Cut Line= 3
      2113824.97     13866275.01      2114277.08     13866089.78
      2114748.47     13865837.16
#Sta/Elev= 30
  4513.1 1132.28  4581.2 1125.66  4605.2 1114.75  4621.2 1110.35  4629.2 1106.04
  4634.6 1105.44  4642.8 1101.70  4682.6 1095.12  4713.3 1092.19  4736.0 1088.10
  4766.7 1086.78  4842.8 1083.50  4906.4 1084.03  4949.6 1083.44  4956.2 1081.23
  4983.0 1077.95  4983.5 1077.45  4994.3 1077.95  5001.4 1078.27  5019.4 1083.33
  5086.6 1086.38  5107.1 1089.07  5129.0 1097.99  5145.3 1106.36  5158.2 1115.92
  5194.8 1123.31  5211.1 1123.72  5238.7 1128.18  5478.9 1142.87  5536.5 1145.71
#Mann=8,-1,0
  4513.1    0.12       0  4713.3    0.07       0  4766.7   0.035       0
  4906.4    0.07       0  4983.0    0.05       0  4994.3    0.07       0
  5086.6    0.12       0  5478.9    0.07       0
Bank Sta=4983,4994.3
Exp/Cntr=0.3,0.1

Type RM Length L Ch R = 1,5009,439,439,439
BEGIN DESCRIPTION:
PANTHER CREEK 10.0
END DESCRIPTION:
XS GIS Cut Line= 3
      2114107.84     13866834.55      2114325.00     13866575.00
      2114998.73     13865738.49
#Sta/Elev= 30
  4661.6 1124.45  4787.3 1121.48  4843.6 1116.15  4857.5 1113.11  4964.2 1078.71
  4991.1 1075.87  4991.6 1075.37  5002.4 1075.87  5028.0 1076.13  5050.4 1079.20
  5146.7 1081.98  5199.2 1083.74  5270.0 1083.22  5275.9 1083.28  5383.2 1086.14
  5455.1 1092.50  5519.1 1105.44  5526.5 1108.74  5539.9 1109.49  5547.9 1115.17
  5554.3 1114.90  5576.7 1119.96  5583.1 1119.67  5597.5 1124.18  5611.9 1126.84
  5632.7 1127.63  5661.5 1131.58  5772.8 1140.03  5886.8 1146.56  6074.1 1157.07
#Mann=9,-1,0
  4661.6    0.12       0  4991.1    0.05       0  5002.4    0.12       0
  5146.7   0.035       0  5270.0    0.12       0  5275.9   0.035       0
  5383.2    0.12       0  5772.8    0.07       0  5886.8    0.12       0
Bank Sta=4991.1,5002.4
Exp/Cntr=0.3,0.1

Type RM Length L Ch R = 1,4570,922,922,922
BEGIN DESCRIPTION:
PANTHER CREEK 9.0
END DESCRIPTION:
XS GIS Cut Line= 3
      2114165.06     13866860.62      2114625.00     13866875.00
      2115467.18     13866673.12
#Sta/Elev= 30
  4539.9 1123.01  4659.9 1121.36  4850.0 1114.90  4890.0 1108.80  4900.0 1104.43
  4920.0 1090.62  4932.6 1084.41  4950.0 1078.59  4980.1 1073.18  5004.6 1071.19
  5005.1 1070.69  5016.0 1071.19  5041.2 1075.83  5107.7 1079.25  5226.3 1078.31
  5362.6 1081.33  5421.7 1083.45  5442.2 1088.19  5448.9 1091.30  5454.1 1090.01
  5491.0 1105.38  5496.1 1104.59  5514.2 1112.60  5524.5 1119.03  5533.0 1127.53
  5538.1 1124.83  5545.1 1131.06  5565.6 1133.88  5647.9 1139.18  5866.1 1145.71
#Mann=5,-1,0
  4539.9    0.12       0  4932.6   0.035       0  5004.6   0.035       0
  5016.0   0.035       0  5362.6    0.12       0
Bank Sta=5004.6,5016
Exp/Cntr=0.3,0.1

Type RM Length L Ch R = 1,3648,469,469,469
BEGIN DESCRIPTION:
PANTHER CREEK 8.0
END DESCRIPTION:
XS GIS Cut Line= 3
      2114001.78     13866887.69      2115175.00     13867475.00
      2115324.98     13867524.99
#Sta/Elev= 30
  3692.1 1124.36  3766.3 1122.55  3908.2 1121.73  4146.3 1114.81  4232.9 1099.13
  4266.0 1092.02  4310.8 1084.17  4319.6 1083.25  4365.7 1082.75  4476.0 1079.49
  4600.5 1078.32  4610.1 1078.27  4758.1 1077.28  4836.5 1075.63  4959.4 1073.80
  4967.8 1071.56  4973.4 1068.40  4990.0 1065.24  4990.5 1064.74  5001.5 1065.24
  5004.1 1067.67  5014.7 1068.54  5046.3 1079.22  5067.4 1089.04  5077.9 1092.43
  5109.5 1107.55  5120.1 1114.12  5141.1 1124.21  5151.7 1127.46  5162.2 1129.36
#Mann=8,-1,0
  3692.1    0.12       0  4232.9   0.035       0  4365.7    0.07       0
  4600.5   0.035       0  4610.1    0.07       0  4836.5   0.035       0
  4990.0    0.05       0  5001.5    0.12       0
Bank Sta=4990,5001.5
Exp/Cntr=0.3,0.1

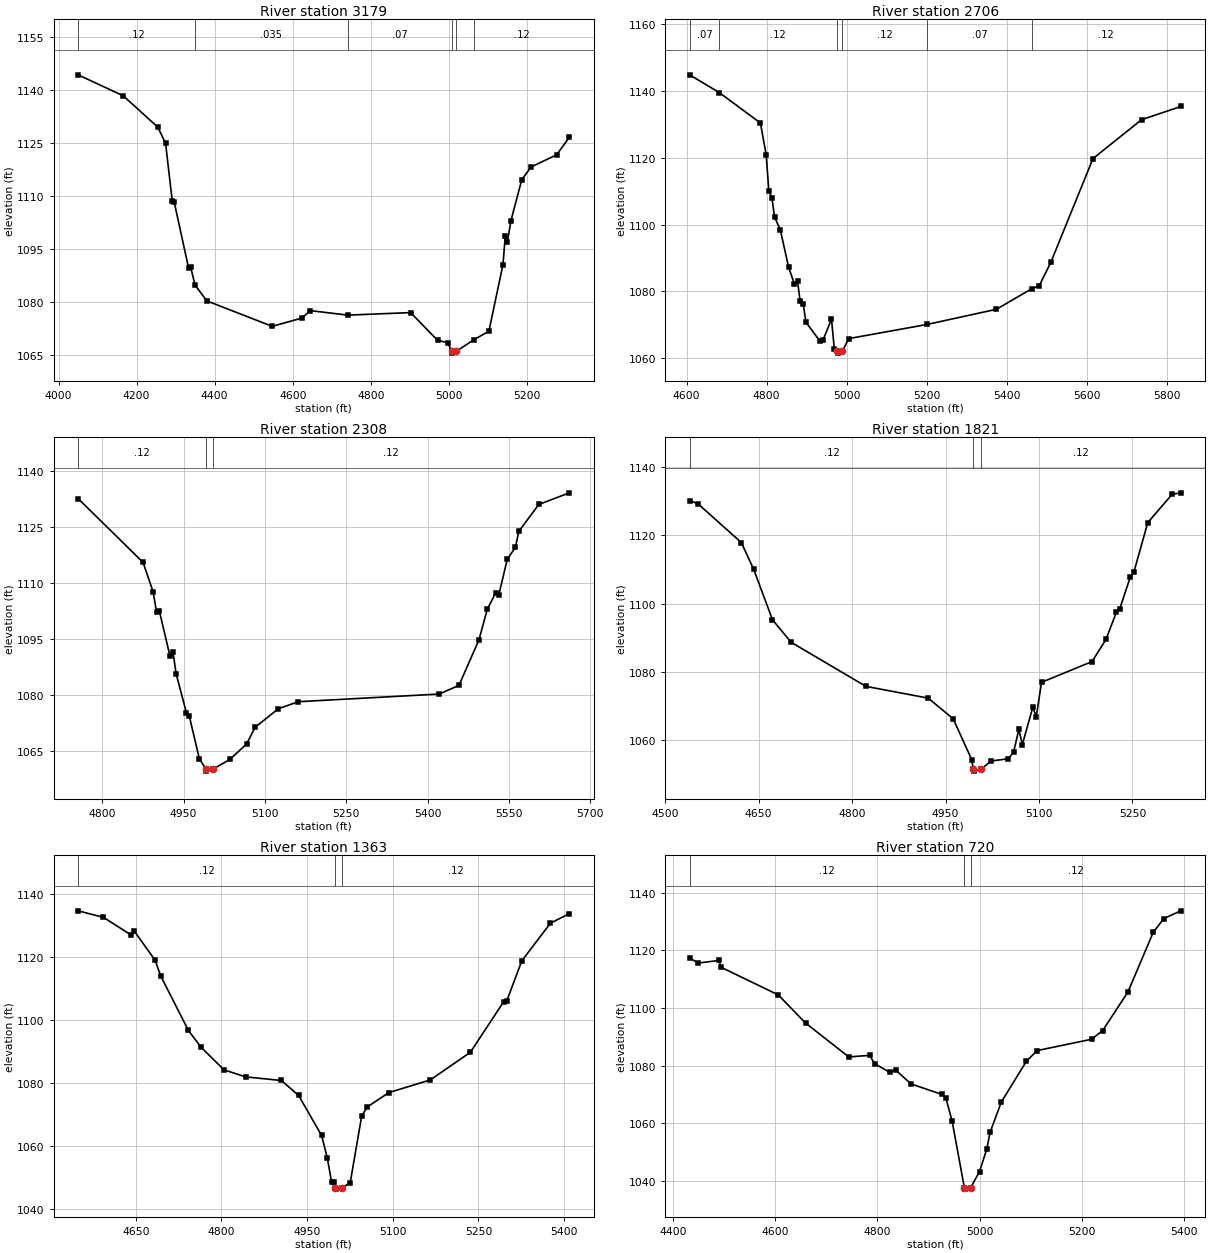
Type RM Length L Ch R = 1,3179,473,473,473
BEGIN DESCRIPTION:
PANTHER CREEK 7.0
END DESCRIPTION:
XS GIS Cut Line= 3
      2114057.23     13868097.09      2114975.00     13867875.00
      2115280.50     13867802.25
#Sta/Elev= 30
  4050.2 1144.21  4165.8 1138.28  4254.6 1129.39  4274.3 1124.81  4291.3 1108.57
  4296.4 1108.23  4333.1 1089.62  4338.3 1089.98  4349.7 1084.76  4380.1 1080.30
  4547.5 1073.11  4624.1 1075.47  4644.6 1077.56  4741.1 1076.28  4901.9 1077.00
  4971.0 1069.15  4997.0 1068.51  5007.2 1066.04  5007.7 1065.54  5018.7 1066.04
  5064.6 1069.37  5102.4 1071.73  5138.4 1090.55  5144.5 1098.69  5149.7 1096.92
  5158.9 1103.00  5186.7 1114.60  5210.3 1118.14  5276.1 1121.61  5308.5 1126.56
#Mann=6,-1,0
  4050.2    0.12       0  4349.7   0.035       0  4741.1    0.07       0
  5007.2    0.05       0  5018.7    0.07       0  5064.6    0.12       0
Bank Sta=5007.2,5018.7
Exp/Cntr=0.3,0.1

Type RM Length L Ch R = 1,2706,398,398,398
BEGIN DESCRIPTION:
PANTHER CREEK 6.0
END DESCRIPTION:
XS GIS Cut Line= 2
      2114474.14     13868523.02      2115427.18     13867748.94
#Sta/Elev= 30
  4607.4 1144.86  4681.4 1139.56  4784.5 1130.42  4798.9 1120.79  4805.4 1110.15
  4813.3 1107.84  4819.7 1102.27  4834.1 1098.41  4854.9 1087.20  4869.3 1082.17
  4877.2 1083.01  4883.7 1077.00  4891.6 1076.09  4898.0 1070.77  4933.2 1065.05
  4941.2 1065.47  4962.0 1071.64  4969.2 1062.63  4976.7 1061.97  4977.2 1061.47
  4988.8 1061.97  5005.1 1065.82  5200.5 1070.05  5374.3 1074.61  5462.6 1080.77
  5481.3 1081.67  5510.1 1088.64  5615.6 1119.77  5737.1 1131.42  5835.2 1135.37
#Mann=6,-1,0
  4607.4    0.07       0  4681.4    0.12       0  4976.7    0.05       0
  4988.8    0.12       0  5200.5    0.07       0  5462.6    0.12       0
Bank Sta=4976.7,4988.8
Exp/Cntr=0.3,0.1

Type RM Length L Ch R = 1,2308,487,487,487
BEGIN DESCRIPTION:
PANTHER CREEK 5.0
END DESCRIPTION:
XS GIS Cut Line= 3
      2115038.49     13868654.26      2115125.00     13868425.00
      2115468.17     13867859.99
#Sta/Elev= 30
  4755.4 1132.60  4875.2 1115.48  4893.6 1107.65  4900.1 1102.24  4905.4 1102.39
  4924.9 1090.33  4930.3 1091.50  4936.3 1085.56  4955.1 1075.20  4960.5 1074.25
  4979.1 1062.76  4991.7 1059.99  4992.2 1059.49  5003.9 1059.99  5035.5 1062.64
  5066.3 1066.80  5081.8 1071.23  5124.5 1076.20  5161.3 1078.11  5421.6 1080.17
  5457.9 1082.50  5494.7 1094.69  5510.2 1102.95  5525.6 1107.29  5531.5 1106.85
  5547.0 1116.31  5562.0 1119.54  5568.3 1123.81  5605.1 1131.01  5661.5 1134.14
#Mann=3,-1,0
  4755.4    0.12       0  4991.7    0.05       0  5003.9    0.12       0
Bank Sta=4991.7,5003.9
Exp/Cntr=0.3,0.1

Type RM Length L Ch R = 1,1821,458,458,458
BEGIN DESCRIPTION:
PANTHER CREEK 4.0
END DESCRIPTION:
XS GIS Cut Line= 3
      2115576.70     13868777.95      2115575.00     13868325.00
      2115725.02     13868024.97
#Sta/Elev= 30
  4539.3 1130.16  4552.3 1129.32  4622.3 1117.89  4642.3 1109.99  4672.3 1095.26
  4702.3 1088.65  4822.3 1075.74  4922.3 1072.29  4962.3 1066.24  4992.3 1054.17
  4994.5 1051.40  4995.0 1050.90  5006.7 1051.40  5023.0 1053.86  5051.0 1054.53
  5059.3 1056.51  5067.7 1063.13  5073.3 1058.69  5090.1 1069.62  5095.7 1066.89
  5104.1 1076.92  5185.1 1083.00  5207.5 1089.48  5224.2 1097.44  5229.8 1098.53
  5246.6 1107.82  5252.2 1109.15  5274.6 1123.73  5313.7 1132.03  5327.7 1132.46
#Mann=3,-1,0
  4539.3    0.12       0  4994.5    0.05       0  5006.7    0.12       0
Bank Sta=4994.5,5006.7
Exp/Cntr=0.3,0.1

Type RM Length L Ch R = 1,1363,643,643,643
BEGIN DESCRIPTION:
PANTHER CREEK 3.0
END DESCRIPTION:
XS GIS Cut Line= 3
      2115930.44     13868869.06      2115975.00     13868425.00
      2115995.54     13868011.90
#Sta/Elev= 30
  4549.2 1134.57  4593.5 1132.50  4641.8 1126.94  4646.9 1128.30  4683.9 1118.93
  4694.0 1113.86  4742.2 1096.67  4764.3 1091.37  4804.5 1084.18  4842.5 1081.94
  4905.0 1080.80  4935.2 1076.06  4975.4 1063.38  4985.4 1056.23  4993.0 1048.54
  4998.0 1048.54  4999.4 1046.87  4999.9 1046.37  5011.7 1046.87  5025.5 1048.36
  5045.6 1069.56  5055.6 1072.46  5093.4 1076.98  5165.7 1080.98  5235.8 1089.73
  5294.2 1105.78  5299.2 1105.87  5325.9 1118.74  5376.0 1130.65  5409.1 1133.68
#Mann=3,-1,0
  4549.2    0.12       0  4999.4    0.05       0  5011.7    0.12       0
Bank Sta=4999.4,5011.7
Exp/Cntr=0.3,0.1

Type RM Length L Ch R = 1,720,236,236,236
BEGIN DESCRIPTION:
PANTHER CREEK 2.0
END DESCRIPTION:
XS GIS Cut Line= 4
      2116378.95     13868801.54      2116461.51     13868349.41
      2116457.88     13868241.48      2116159.18     13867984.40
#Sta/Elev= 30
  4432.4 1117.35  4449.2 1115.58  4489.4 1116.47  4494.4 1114.08  4606.0 1104.54
  4659.3 1094.80  4744.0 1083.04  4784.7 1083.58  4794.8 1080.69  4824.1 1077.69
  4835.5 1078.52  4866.0 1073.67  4926.4 1070.05  4934.2 1068.77  4946.4 1060.71
  4970.3 1037.72  4970.8 1037.22  4982.6 1037.72  5000.0 1043.32  5014.0 1051.02
  5020.6 1056.85  5042.5 1067.37  5091.9 1081.58  5112.8 1085.24  5219.2 1089.16
  5241.1 1092.19  5290.5 1105.56  5339.9 1126.18  5360.7 1131.00  5394.1 1133.68
#Mann=3,-1,0
  4432.4    0.12       0  4970.3    0.05       0  4982.6    0.12       0
Bank Sta=4970.3,4982.6
Exp/Cntr=0.3,0.1

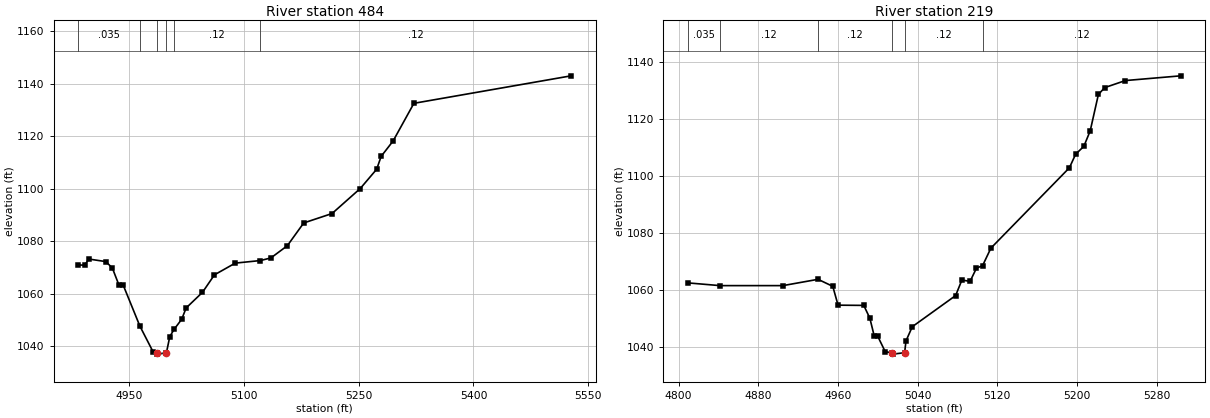
Type RM Length L Ch R = 1,484,265,265,265
BEGIN DESCRIPTION:
PANTHER CREEK 1.0
END DESCRIPTION:
XS GIS Cut Line= 3
      2116675.00     13868175.00      2116625.00     13868075.00
      2116168.86     13867801.41
#Sta/Elev= 30
  4883.8 1071.06  4892.2 1070.98  4897.8 1073.31  4920.1 1072.33  4928.5 1069.82
  4936.9 1063.49  4942.5 1063.44  4964.4 1047.74  4981.6 1037.97  4986.7 1037.59
  4987.2 1037.09  4999.0 1037.59  5003.4 1043.76  5009.0 1046.52  5018.9 1050.34
  5024.8 1054.69  5046.1 1060.63  5061.7 1067.29  5088.9 1071.76  5121.8 1072.74
  5135.5 1073.75  5156.9 1078.39  5178.3 1087.06  5215.3 1090.65  5252.1 1100.17
  5273.6 1107.54  5279.4 1112.42  5295.0 1118.28  5322.2 1132.64  5527.5 1143.11
#Mann=6,-1,0
  4883.8   0.035       0  4964.4    0.12       0  4986.7    0.05       0
  4999.0    0.12       0  5009.0    0.12       0  5121.8    0.12       0
Bank Sta=4986.7,4999
Exp/Cntr=0.3,0.1

Type RM Length L Ch R = 1,219,0,0,0
BEGIN DESCRIPTION:
PANTHER CREEK 0.0
END DESCRIPTION:
XS GIS Cut Line= 4
      2116748.15     13868040.11      2116759.19     13867889.39
      2116748.01     13867851.43      2116562.75     13867610.28
#Sta/Elev= 30
  4809.3 1062.46  4841.6 1061.50  4904.7 1061.50  4940.0 1063.71  4954.8 1061.25
  4960.1 1054.64  4985.9 1054.56  4992.0 1050.09  4996.5 1043.68  5000.0 1043.68
  5007.5 1038.27  5014.6 1037.96  5015.1 1037.46  5026.9 1037.96  5028.3 1042.11
  5034.6 1047.08  5078.1 1058.01  5084.4 1063.46  5092.6 1062.99  5099.0 1067.61
  5105.2 1068.53  5113.5 1074.65  5192.3 1102.85  5198.6 1107.63  5206.8 1110.37
  5213.2 1115.82  5221.4 1128.57  5227.7 1130.98  5248.5 1133.46  5304.1 1135.12
#Mann=6,-1,0
  4809.3   0.035       0  4841.6    0.12       0  4940.0    0.12       0
  5014.6    0.05       0  5026.9    0.12       0  5105.2    0.12       0
Bank Sta=5014.6,5026.9
Exp/Cntr=0.3,0.1

Chan Stop Cuts=-1