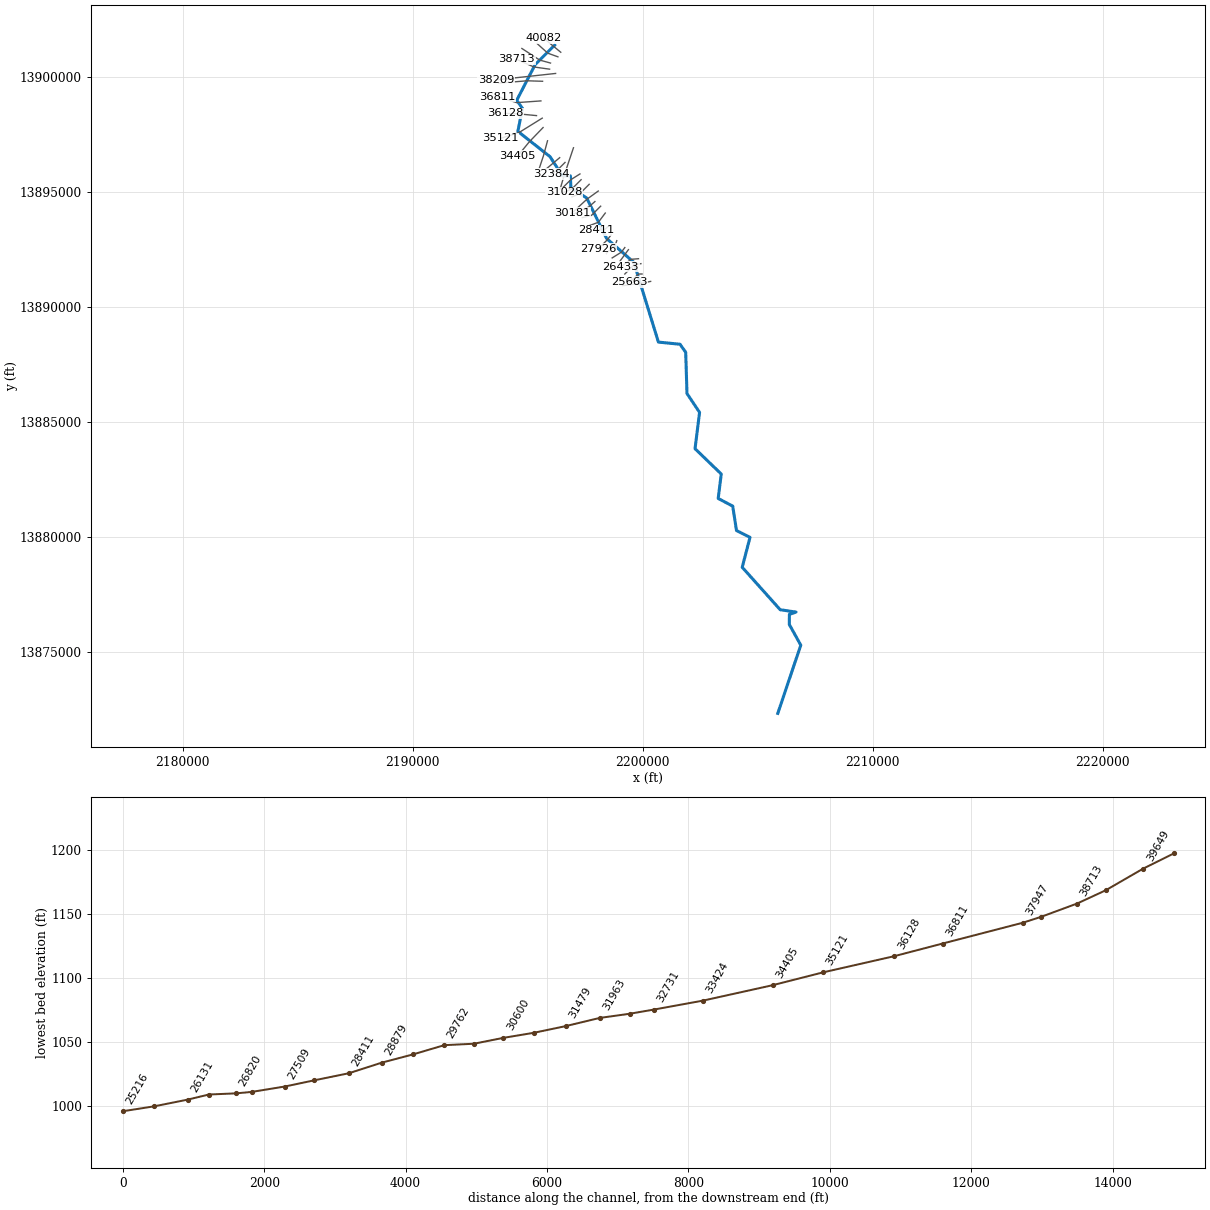
--- Potter Creek.prj (project) ---

Proj Title=Potter Creek Base Level Engineering
Current Plan=p01
Default Exp/Contr=0.3,0.1
English Units
Geom File=g01
Flow File=f01
Plan File=p01
BEGIN DESCRIPTION:
Potter Creek
END DESCRIPTION:

--- Potter Creek.p01 (plan) ---

Plan Title=Multiple Run
Short Identifier=Multiple
Geom File=g01
Flow File=f01
Subcritical Flow
K Sum by GR= 0
Std Step Tol= 0.01
Critical Tol= 0.01
Num of Std Step Trials= 20
Max Error Tol= 0.3
Flow Tol Ratio= 0.001
Split Flow NTrial= 30
Split Flow Tol= 0.02
Split Flow Ratio= 0.02
Log Output Level= 0
Friction Slope Method= 1
Unsteady Friction Slope Method= 2
Unsteady Bridges Friction Slope Method= 1
Parabolic Critical Depth
Global Vel Dist=  1 , 1 , 1
Global Log Level= 0
CheckData=True
Encroach Param= -1, 0, 0, 0
BEGIN DESCRIPTION:
Multiple Run
END DESCRIPTION:

--- Potter Creek.f01 (steady flow) ---

Flow Title=Multiple
Number of Profiles=7
Profile Names=10-year,25-year,50-year,1pct_min,100-year,1pct_plu,500-year
River Rch & RM= Potter Creek,Reach-1,40082
     527     856    1157     761    1519    3030    2581
River Rch & RM= Potter Creek,Reach-1,37947
    1422    2444    3429    2331    4651    9279    8461
River Rch & RM= Potter Creek,Reach-1,31479
    1764    3056    4312    2944    5873   11718   10781
River Rch & RM= Potter Creek,Reach-1,26433
    2772    4905    7016    4847    9670   19295   18192
River Rch & RM= Potter Creek,Reach-1,20207
    3980    7132   10290    7160   14285   28503   27269
River Rch & RM= Potter Creek,Reach-1,12869
    4032    7202   10365    7192   14350   28633   27242
Boundary for River Rch & Prof#=Potter Creek,Reach-1,1
Up Type=0
Dn Type=3
Dn Slope=0.005
Boundary for River Rch & Prof#=Potter Creek,Reach-1,2
Up Type=0
Dn Type=3
Dn Slope=0.005
Boundary for River Rch & Prof#=Potter Creek,Reach-1,3
Up Type=0
Dn Type=3
Dn Slope=0.005
Boundary for River Rch & Prof#=Potter Creek,Reach-1,4
Up Type=0
Dn Type=3
Dn Slope=0.005
Boundary for River Rch & Prof#=Potter Creek,Reach-1,5
Up Type=0
Dn Type=3
Dn Slope=0.005
Boundary for River Rch & Prof#=Potter Creek,Reach-1,6
Up Type=0
Dn Type=3
Dn Slope=0.005
Boundary for River Rch & Prof#=Potter Creek,Reach-1,7
Up Type=0
Dn Type=3
Dn Slope=0.005

--- Potter Creek.g01 (geometry) ---

Geom Title=Existing Conditions

River Reach=Potter Creek,Reach-1
Reach XY= 30
      2196175.00     13901375.00      2195325.00     13900525.00
      2194525.00     13898975.00      2194775.00     13898625.00
      2194575.00     13897625.00      2195975.00     13896525.00
      2196511.66     13895688.36      2196858.73     13895692.31
      2196880.40     13895172.57      2197566.87     13894731.07
      2198432.81     13892968.81      2199617.30     13891931.47
      2200685.47     13888465.18      2201623.54     13888371.48
      2201871.20     13888023.43      2201927.26     13886230.94
      2202474.51     13885409.78      2202277.14     13883830.97
      2203416.84     13882731.05      2203283.99     13881668.34
      2203914.94     13881335.01      2204079.95     13880272.43
      2204667.17     13879978.23      2204328.46     13878676.50
      2205980.08     13876830.04      2206667.62     13876728.41
      2206379.97     13876627.59      2206375.36     13876190.16
      2206874.72     13875289.64      2205875.00     13872325.00

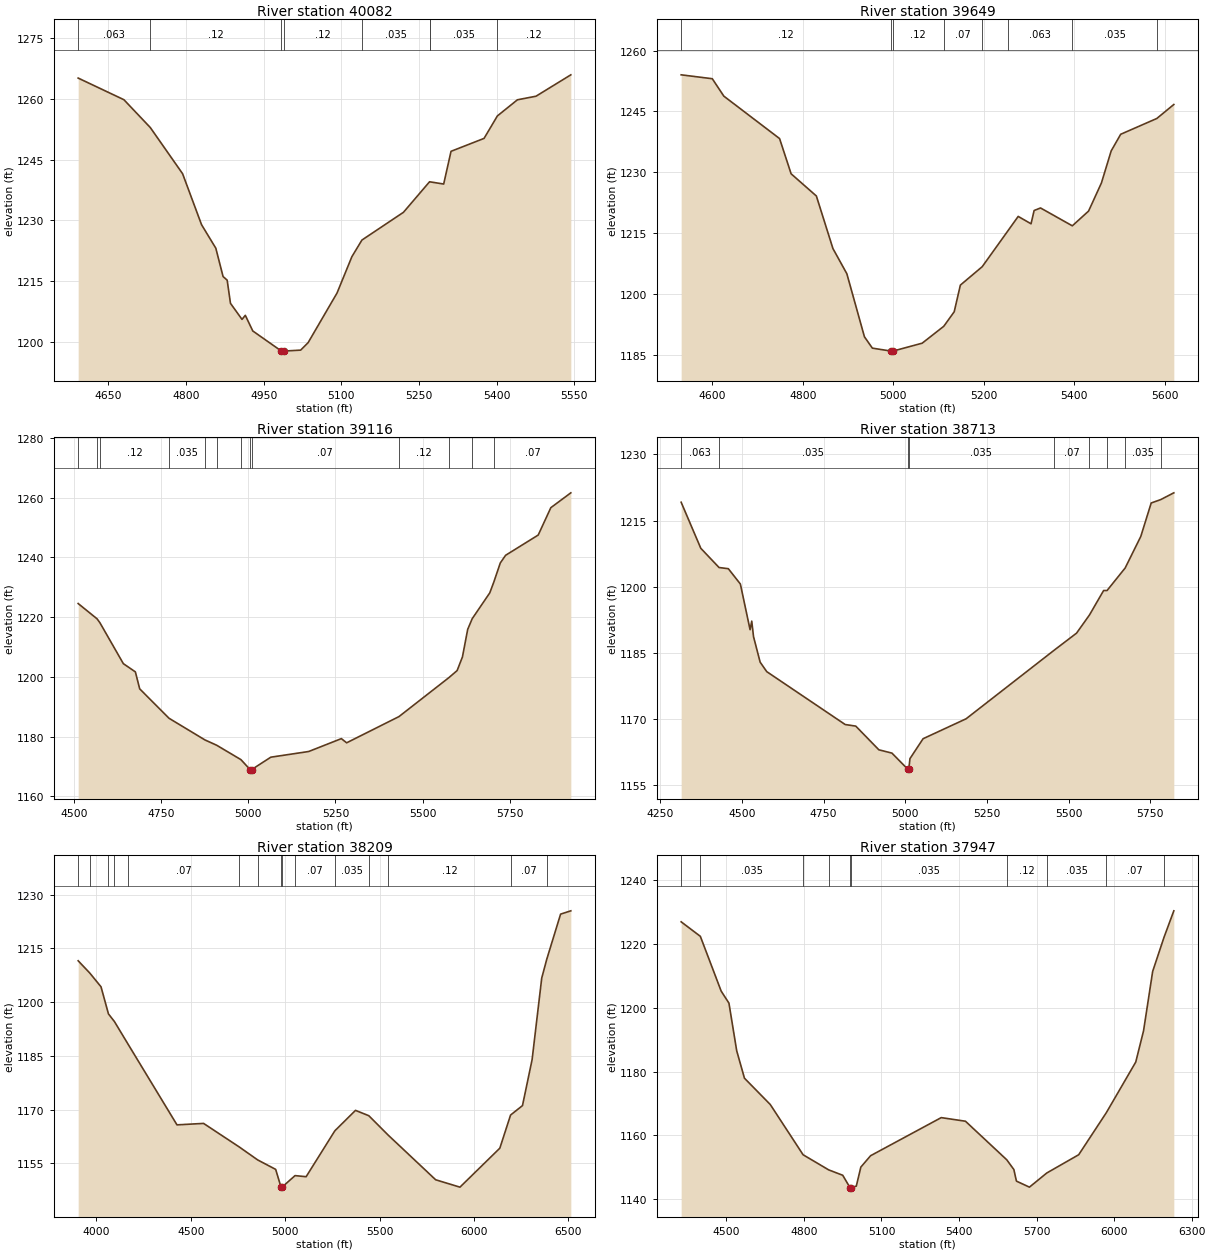
Type RM Length L Ch R = 1,40082,433,433,433
BEGIN DESCRIPTION:
Potter Creek 78.0
END DESCRIPTION:
XS GIS Cut Line= 3
      2196440.44     13901065.60      2196125.00     13901325.00
      2195705.35     13901670.54
#Sta/Elev= 30
  4591.6 1265.06  4680.0 1259.73  4731.0 1252.87  4793.4 1241.50  4830.0 1228.95
  4857.6 1223.15  4871.6 1216.17  4879.5 1215.29  4885.9 1209.58  4908.2 1205.62
  4914.6 1206.62  4929.0 1202.77  4984.4 1197.81  4984.6 1197.31  4988.4 1197.81
  5021.5 1198.05  5035.9 1199.88  5091.8 1212.11  5120.5 1221.06  5139.9 1225.16
  5220.2 1232.00  5270.6 1239.52  5270.8 1239.51  5297.9 1238.96  5312.1 1247.02
  5375.9 1250.20  5401.7 1255.74  5440.4 1259.71  5476.3 1260.59  5543.6 1265.86
#Mann=8,-1,0
  4591.6   0.063       0  4731.0    0.12       0  4984.4    0.05       0
  4988.4    0.12       0  5139.9   0.035       0  5270.6   0.063       0
  5270.8   0.035       0  5401.7    0.12       0
Bank Sta=4984.4,4988.4
Exp/Cntr=0.3,0.1

Type RM Length L Ch R = 1,39649,533,533,533
BEGIN DESCRIPTION:
Potter Creek 77.0
END DESCRIPTION:
XS GIS Cut Line= 3
      2196316.42     13900867.43      2195875.00     13901025.00
      2195414.88     13901440.56
#Sta/Elev= 30
  4531.3 1254.02  4600.1 1253.06  4625.6 1248.77  4748.8 1238.31  4774.3 1229.63
  4830.1 1224.16  4866.7 1211.21  4897.5 1204.99  4936.3 1189.47  4953.8 1186.67
  4995.3 1185.94  4995.6 1185.44  4999.3 1185.94  5063.9 1187.89  5111.6 1192.05
  5134.7 1195.63  5148.3 1202.20  5196.6 1206.74  5253.7 1215.63  5276.1 1219.13
  5304.5 1217.31  5311.3 1220.59  5325.5 1221.21  5395.7 1216.81  5431.6 1220.44
  5460.0 1227.37  5481.6 1235.28  5502.6 1239.37  5582.4 1243.26  5620.0 1246.71
#Mann=8,-1,0
  4531.3    0.12       0  4995.3    0.05       0  4999.3    0.12       0
  5111.6    0.07       0  5196.6   0.035       0  5253.7   0.063       0
  5395.7   0.035       0  5582.4    0.12       0
Bank Sta=4995.3,4999.3
Exp/Cntr=0.3,0.1

Type RM Length L Ch R = 1,39116,403,403,403
BEGIN DESCRIPTION:
Potter Creek 76.0
END DESCRIPTION:
XS GIS Cut Line= 3
      2195995.03     13900595.66      2195525.00     13900725.00
      2194749.99     13901229.95
#Sta/Elev= 30
  4512.5 1224.52  4566.7 1219.40  4575.2 1218.02  4642.0 1204.40  4676.5 1201.64
  4688.9 1195.96  4772.9 1186.12  4876.0 1178.86  4909.4 1177.10  4979.1 1172.27
  5005.6 1168.92  5005.8 1168.42  5009.6 1168.92  5064.9 1173.09  5173.5 1174.99
  5267.1 1179.30  5282.2 1177.90  5432.2 1186.67  5575.6 1199.74  5599.0 1202.08
  5614.2 1206.63  5629.3 1215.87  5642.2 1219.44  5692.6 1228.09  5704.3 1231.75
  5722.8 1238.11  5738.0 1240.67  5831.5 1247.45  5867.7 1256.61  5925.0 1261.58
#Mann=13,-1,0
  4512.5    0.12       0  4566.7   0.035       0  4575.2    0.12       0
  4772.9   0.035       0  4876.0    0.07       0  4909.4   0.035       0
  4979.1    0.07       0  5005.6    0.05       0  5009.6    0.07       0
  5432.2    0.12       0  5575.6    0.07       0  5642.2    0.12       0
  5704.3    0.07       0
Bank Sta=5005.6,5009.6
Exp/Cntr=0.3,0.1

Type RM Length L Ch R = 1,38713,504,504,504
BEGIN DESCRIPTION:
Potter Creek 75.0
END DESCRIPTION:
XS GIS Cut Line= 3
      2195954.52     13900330.23      2195275.00     13900425.00
      2194522.42     13900756.12
#Sta/Elev= 30
  4313.9 1219.15  4374.0 1208.70  4429.9 1204.33  4458.4 1204.06  4495.2 1200.58
  4524.9 1190.21  4530.0 1192.16  4535.5 1188.62  4555.7 1182.85  4575.9 1180.69
  4816.1 1168.68  4848.5 1168.32  4919.2 1162.94  4959.2 1162.19  5006.9 1158.60
  5007.2 1158.10  5010.9 1158.60  5014.4 1160.94  5054.6 1165.46  5186.2 1169.98
  5454.9 1185.50  5524.4 1189.43  5564.0 1193.56  5607.3 1199.11  5617.7 1199.10
  5673.2 1204.22  5721.1 1211.39  5752.9 1218.98  5782.3 1219.76  5822.2 1221.29
#Mann=9,-1,0
  4313.9   0.063       0  4429.9   0.035       0  5006.9   0.035       0
  5010.9   0.035       0  5454.9    0.07       0  5564.0    0.12       0
  5617.7    0.07       0  5673.2   0.035       0  5782.3   0.063       0
Bank Sta=5006.9,5010.9
Exp/Cntr=0.3,0.1

Type RM Length L Ch R = 1,38209,262,262,262
BEGIN DESCRIPTION:
Potter Creek 74.0
END DESCRIPTION:
XS GIS Cut Line= 3
      2196215.32     13900144.04      2195125.00     13900025.00
      2193621.10     13899863.03
#Sta/Elev= 30
  3903.2 1211.56  3964.7 1208.14  4024.2 1204.30  4063.6 1196.73  4095.3 1194.59
  4166.2 1188.39  4426.6 1165.75  4567.4 1166.16  4755.3 1159.62  4854.1 1155.96
  4949.3 1153.32  4977.9 1148.31  4978.1 1147.81  4981.9 1148.31  5051.8 1151.58
  5110.6 1151.28  5262.8 1164.10  5372.1 1169.80  5442.5 1168.31  5545.8 1162.86
  5796.7 1150.42  5925.3 1148.36  6136.5 1159.24  6193.4 1168.49  6256.5 1171.13
  6307.5 1183.98  6358.5 1206.75  6385.4 1212.04  6458.4 1224.59  6512.6 1225.51
#Mann=15,-1,0
  3903.2    0.12       0  3964.7   0.035       0  4063.6   0.063       0
  4095.3   0.035       0  4166.2    0.07       0  4755.3   0.035       0
  4854.1    0.12       0  4977.9    0.05       0  4981.9    0.12       0
  5051.8    0.07       0  5262.8   0.035       0  5442.5   0.063       0
  5545.8    0.12       0  6193.4    0.07       0  6385.4    0.12       0
Bank Sta=4977.9,4981.9
Exp/Cntr=0.3,0.1

Type RM Length L Ch R = 1,37947,1136,1136,1136
BEGIN DESCRIPTION:
Potter Creek 73.0
END DESCRIPTION:
XS GIS Cut Line= 3
      2195649.76     13899803.67      2194975.00     13899825.00
      2193748.21     13899723.25
#Sta/Elev= 30
  4324.9 1226.97  4399.1 1222.42  4479.7 1205.24  4509.8 1201.46  4539.8 1186.52
  4569.8 1177.92  4669.8 1169.65  4796.7 1153.90  4895.4 1149.17  4950.0 1147.47
  4978.0 1143.62  4978.2 1143.12  4982.0 1143.62  5002.5 1144.06  5020.1 1150.03
  5057.8 1153.60  5331.1 1165.55  5424.9 1164.42  5584.9 1152.30  5612.1 1149.27
  5622.1 1145.63  5672.3 1143.74  5739.5 1148.18  5863.0 1153.91  5969.9 1167.10
  6083.7 1182.98  6113.8 1192.75  6149.1 1211.39  6192.6 1222.01  6231.0 1230.42
#Mann=10,-1,0
  4324.9    0.12       0  4399.1   0.035       0  4796.7    0.07       0
  4895.4   0.035       0  4978.0   0.035       0  4982.0   0.035       0
  5584.9    0.12       0  5739.5   0.035       0  5969.9    0.07       0
  6192.6    0.12       0
Bank Sta=4978,4982
Exp/Cntr=0.3,0.1

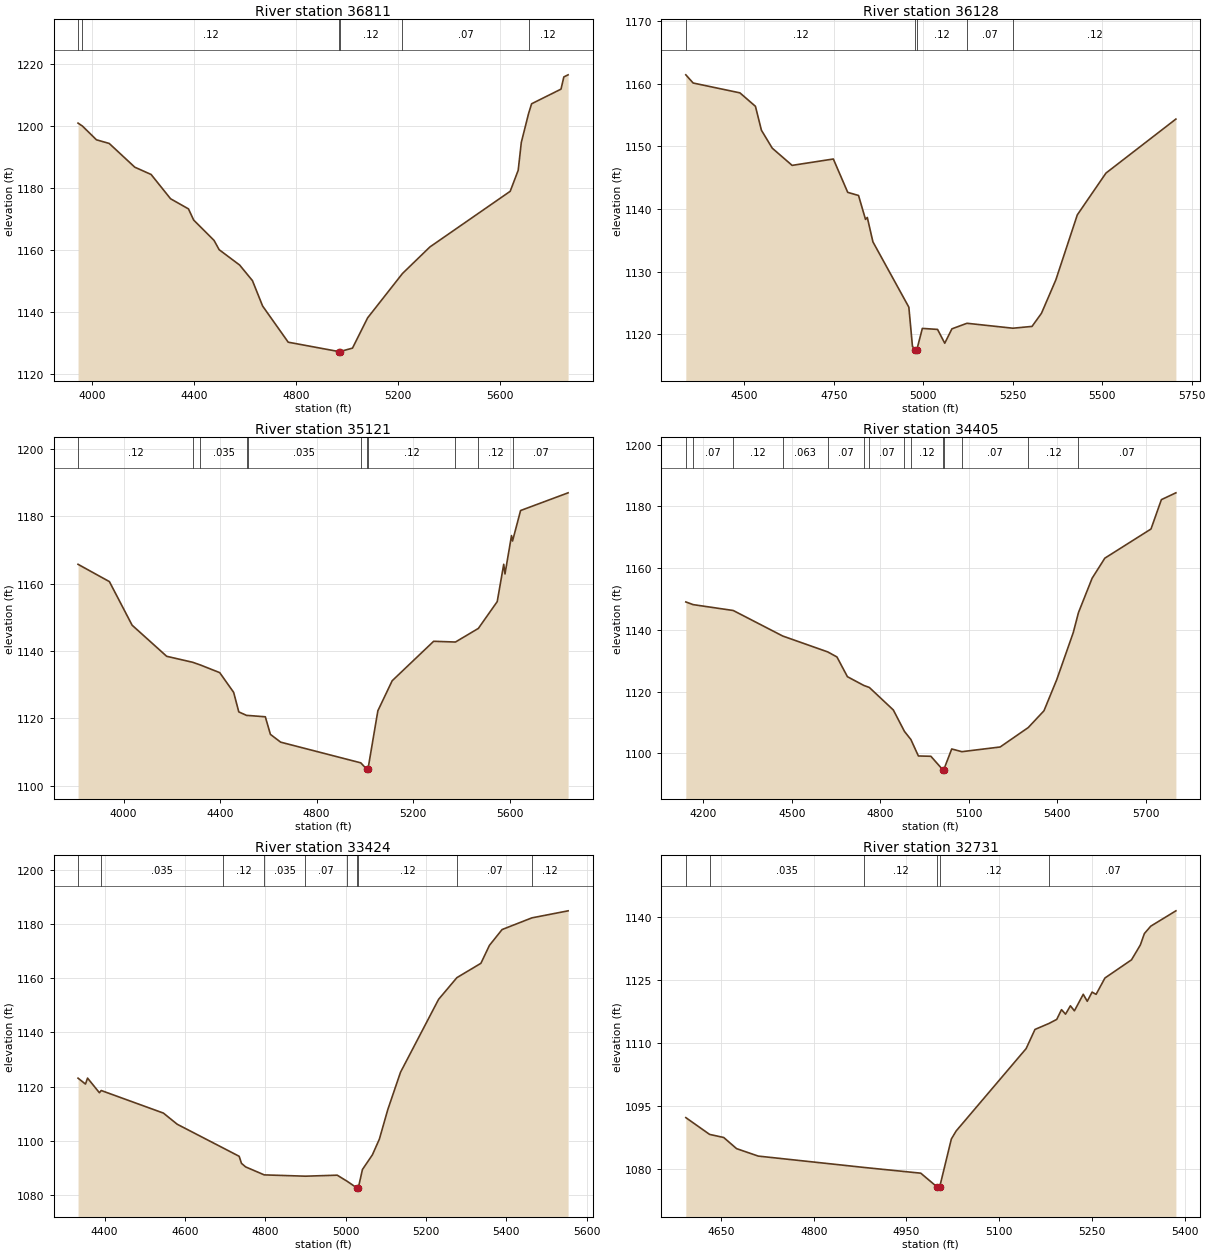
Type RM Length L Ch R = 1,36811,683,683,683
BEGIN DESCRIPTION:
Potter Creek 72.0
END DESCRIPTION:
XS GIS Cut Line= 3
      2195577.00     13898950.37      2194525.00     13898875.00
      2193698.45     13899136.40
#Sta/Elev= 30
  3945.3 1201.06  3962.6 1200.10  4017.5 1195.67  4067.6 1194.49  4167.9 1186.83
  4231.7 1184.49  4308.2 1176.64  4378.4 1173.37  4398.5 1169.79  4478.7 1163.20
  4498.7 1160.20  4578.9 1155.26  4629.1 1150.23  4669.2 1142.01  4769.4 1130.36
  4967.9 1127.33  4968.2 1126.83  4971.9 1127.33  5021.4 1128.44  5080.8 1138.21
  5217.5 1152.53  5325.1 1161.10  5639.8 1179.05  5671.2 1185.83  5683.4 1194.83
  5711.8 1204.12  5723.7 1207.29  5839.1 1212.03  5850.2 1215.96  5866.9 1216.64
#Mann=6,-1,0
  3945.3   0.035       0  3962.6    0.12       0  4967.9    0.05       0
  4971.9    0.12       0  5217.5    0.07       0  5711.8    0.12       0
Bank Sta=4967.9,4971.9
Exp/Cntr=0.3,0.1

Type RM Length L Ch R = 1,36128,1007,1007,1007
BEGIN DESCRIPTION:
Potter Creek 71.0
END DESCRIPTION:
XS GIS Cut Line= 3
      2195385.36     13898311.58      2194725.00     13898375.00
      2194019.87     13898409.99
#Sta/Elev= 30
  4336.6 1161.43  4357.1 1160.12  4487.7 1158.55  4531.1 1156.40  4547.9 1152.57
  4578.1 1149.71  4633.6 1146.96  4748.8 1147.98  4789.0 1142.65  4819.2 1142.15
  4838.7 1138.33  4843.7 1138.64  4859.4 1134.74  4959.8 1124.30  4969.9 1118.04
  4977.9 1117.46  4978.2 1116.96  4981.9 1117.46  4997.5 1120.91  5040.0 1120.75
  5060.1 1118.54  5080.1 1120.84  5122.2 1121.73  5250.6 1120.94  5304.0 1121.23
  5330.4 1123.33  5370.5 1128.66  5430.5 1139.05  5510.6 1145.73  5706.0 1154.36
#Mann=5,-1,0
  4336.6    0.12       0  4977.9    0.05       0  4981.9    0.12       0
  5122.2    0.07       0  5250.6    0.12       0
Bank Sta=4977.9,4981.9
Exp/Cntr=0.3,0.1

Type RM Length L Ch R = 1,35121,716,716,716
BEGIN DESCRIPTION:
Potter Creek 70.0
END DESCRIPTION:
XS GIS Cut Line= 3
      2195635.48     13898201.62      2194625.00     13897575.00
      2193822.18     13897320.47
#Sta/Elev= 30
  3811.0 1165.72  3941.0 1160.58  4035.1 1147.64  4178.4 1138.40  4286.5 1136.62
  4317.8 1135.83  4398.2 1133.55  4456.0 1127.69  4477.3 1121.89  4510.5 1120.82
  4514.0 1120.84  4587.2 1120.44  4608.4 1115.21  4650.9 1112.90  4982.9 1106.76
  5008.5 1104.80  5008.7 1104.30  5012.5 1104.80  5053.7 1122.22  5113.0 1131.14
  5284.9 1142.86  5375.3 1142.64  5470.2 1146.68  5548.4 1154.64  5575.4 1165.73
  5580.6 1162.87  5607.7 1174.26  5611.9 1172.64  5645.2 1181.69  5842.2 1186.95
#Mann=11,-1,0
  3811.0    0.12       0  4286.5    0.07       0  4317.8   0.035       0
  4510.5    0.07       0  4514.0   0.035       0  4982.9    0.12       0
  5008.5    0.05       0  5012.5    0.12       0  5375.3    0.07       0
  5470.2    0.12       0  5611.9    0.07       0
Bank Sta=5008.5,5012.5
Exp/Cntr=0.3,0.1

Type RM Length L Ch R = 1,34405,981,981,981
BEGIN DESCRIPTION:
Potter Creek 69.0
END DESCRIPTION:
XS GIS Cut Line= 3
      2195671.86     13897792.63      2195075.00     13897175.00
      2194567.33     13896553.75
#Sta/Elev= 30
  4141.1 1149.04  4165.9 1148.17  4301.8 1146.27  4469.5 1138.00  4622.2 1132.85
  4653.4 1131.21  4688.9 1124.82  4744.6 1121.98  4763.1 1121.34  4844.5 1114.04
  4882.1 1107.11  4904.0 1104.47  4929.4 1099.14  4971.8 1099.04  5011.6 1094.73
  5011.9 1094.23  5015.6 1094.73  5042.4 1101.41  5076.8 1100.53  5206.6 1102.05
  5301.9 1108.35  5355.1 1113.78  5398.4 1123.86  5454.4 1139.11  5472.1 1145.60
  5518.3 1156.71  5561.4 1163.22  5717.9 1172.67  5753.1 1182.18  5802.3 1184.39
#Mann=14,-1,0
  4141.1    0.12       0  4165.9    0.07       0  4301.8    0.12       0
  4469.5   0.063       0  4622.2    0.07       0  4744.6    0.12       0
  4763.1    0.07       0  4882.1   0.035       0  4904.0    0.12       0
  5011.6    0.05       0  5015.6    0.12       0  5076.8    0.07       0
  5301.9    0.12       0  5472.1    0.07       0
Bank Sta=5011.6,5015.6
Exp/Cntr=0.3,0.1

Type RM Length L Ch R = 1,33424,693,693,693
BEGIN DESCRIPTION:
Potter Creek 68.0
END DESCRIPTION:
XS GIS Cut Line= 3
      2195864.88     13897217.77      2195690.54     13896575.00
      2195516.31     13896048.90
#Sta/Elev= 30
  4334.0 1123.12  4352.5 1120.95  4357.7 1123.14  4387.2 1117.75  4391.7 1118.57
  4546.5 1110.25  4581.1 1106.12  4694.8 1097.42  4735.2 1094.32  4741.0 1091.71
  4751.3 1090.41  4797.6 1087.47  4900.3 1086.99  4979.3 1087.36  5003.2 1085.19
  5027.9 1082.72  5028.2 1082.22  5031.9 1082.72  5042.1 1089.45  5066.9 1094.86
  5084.3 1100.66  5105.3 1111.56  5136.9 1125.30  5231.7 1152.17  5277.3 1160.17
  5337.1 1165.46  5358.2 1172.04  5389.8 1177.90  5463.9 1182.20  5554.2 1184.80
#Mann=10,-1,0
  4334.0    0.12       0  4391.7   0.035       0  4694.8    0.12       0
  4797.6   0.035       0  4900.3    0.07       0  5003.2    0.12       0
  5027.9    0.05       0  5031.9    0.12       0  5277.3    0.07       0
  5463.9    0.12       0
Bank Sta=5027.9,5031.9
Exp/Cntr=0.3,0.1

Type RM Length L Ch R = 1,32731,347,347,347
BEGIN DESCRIPTION:
Potter Creek 67.0
END DESCRIPTION:
XS GIS Cut Line= 2
      2196393.38     13896482.32      2195784.94     13895973.90
#Sta/Elev= 30
  4593.0 1092.22  4631.5 1088.23  4654.3 1087.50  4675.1 1084.85  4710.2 1083.08
  4882.0 1080.37  4973.1 1079.02  4999.7 1075.73  5000.0 1075.23  5003.7 1075.73
  5022.6 1087.14  5030.4 1089.05  5143.6 1108.62  5157.9 1113.17  5180.4 1114.58
  5193.1 1115.55  5200.8 1117.87  5207.4 1116.80  5215.2 1118.79  5221.7 1117.59
  5236.0 1121.52  5242.5 1119.86  5250.3 1122.04  5256.8 1121.51  5271.1 1125.39
  5314.1 1129.71  5328.4 1133.24  5334.9 1135.94  5345.2 1137.70  5385.9 1141.35
#Mann=6,-1,0
  4593.0    0.07       0  4631.5   0.035       0  4882.0    0.12       0
  4999.7    0.05       0  5003.7    0.12       0  5180.4    0.07       0
Bank Sta=4999.7,5003.7
Exp/Cntr=0.3,0.1

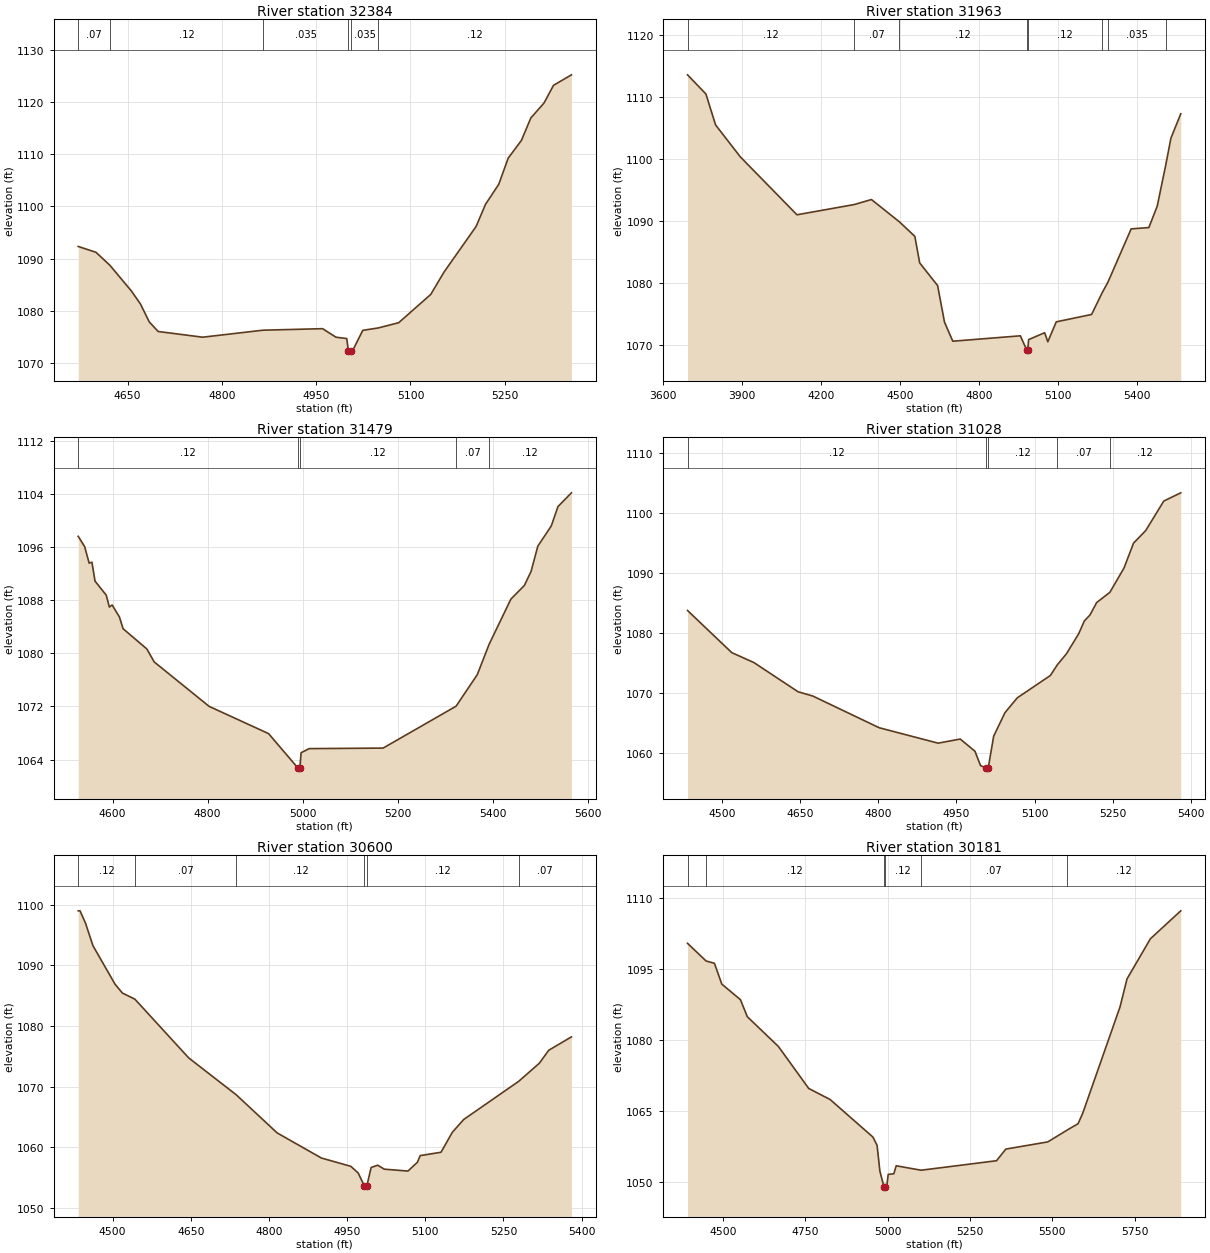
Type RM Length L Ch R = 1,32384,421,421,421
BEGIN DESCRIPTION:
Potter Creek 66.0
END DESCRIPTION:
XS GIS Cut Line= 3
      2196624.99     13896274.99      2196325.00     13895975.00
      2196025.01     13895775.00
#Sta/Elev= 30
  4571.3 1092.33  4599.6 1091.21  4621.7 1088.73  4656.1 1083.78  4670.3 1081.33
  4684.4 1077.88  4698.6 1076.05  4769.3 1074.96  4865.4 1076.30  4960.2 1076.59
  4981.4 1074.96  4998.6 1074.70  5001.1 1072.41  5001.3 1071.91  5005.1 1072.41
  5009.1 1072.66  5024.1 1076.27  5048.7 1076.73  5081.2 1077.73  5132.3 1083.15
  5153.3 1087.41  5204.4 1096.15  5219.4 1100.40  5240.4 1104.21  5255.5 1109.24
  5276.5 1112.62  5291.5 1116.92  5312.5 1119.79  5327.6 1123.17  5356.1 1125.18
#Mann=6,-1,0
  4571.3    0.07       0  4621.7    0.12       0  4865.4   0.035       0
  5001.1   0.035       0  5005.1   0.035       0  5048.7    0.12       0
Bank Sta=5001.1,5005.1
Exp/Cntr=0.3,0.1

Type RM Length L Ch R = 1,31963,484,484,484
BEGIN DESCRIPTION:
Potter Creek 65.0
END DESCRIPTION:
XS GIS Cut Line= 3
      2196993.05     13896914.24      2196575.00     13895675.00
      2196417.59     13895129.20
#Sta/Elev= 30
  3691.7 1113.52  3761.7 1110.43  3798.4 1105.45  3892.8 1100.29  4107.9 1090.97
  4326.0 1092.62  4391.1 1093.43  4497.4 1089.84  4556.3 1087.49  4574.7 1083.22
  4642.9 1079.56  4669.1 1073.67  4700.6 1070.60  4957.6 1071.47  4981.8 1069.18
  4982.1 1068.68  4985.8 1069.18  4989.1 1070.86  5050.0 1071.97  5062.0 1070.51
  5094.1 1073.72  5228.5 1074.91  5269.1 1078.44  5290.1 1080.06  5379.0 1088.70
  5446.3 1088.91  5478.3 1092.39  5510.1 1098.90  5530.3 1103.32  5567.6 1107.24
#Mann=8,-1,0
  3691.7    0.12       0  4326.0    0.07       0  4497.4    0.12       0
  4981.8    0.05       0  4985.8    0.12       0  5269.1    0.07       0
  5290.1   0.035       0  5510.1    0.12       0
Bank Sta=4981.8,4985.8
Exp/Cntr=0.3,0.1

Type RM Length L Ch R = 1,31479,451,451,451
BEGIN DESCRIPTION:
Potter Creek 64.0
END DESCRIPTION:
XS GIS Cut Line= 3
      2197275.03     13895775.02      2196875.00     13895525.00
      2196475.01     13895125.01
#Sta/Elev= 30
  4527.7 1097.61  4541.3 1096.06  4550.7 1093.58  4556.6 1093.71  4563.1 1090.86
  4586.7 1088.75  4593.2 1086.96  4599.1 1087.27  4614.4 1085.47  4622.1 1083.70
  4672.2 1080.64  4687.5 1078.70  4803.1 1072.00  4928.1 1067.90  4989.5 1062.75
  4989.8 1062.25  4994.0 1062.75  4996.5 1065.02  5013.6 1065.64  5169.1 1065.72
  5322.5 1072.03  5367.1 1076.78  5391.8 1081.32  5437.8 1088.16  5466.1 1090.21
  5480.3 1092.34  5494.4 1096.13  5522.7 1099.17  5536.8 1102.09  5565.1 1104.16
#Mann=5,-1,0
  4527.7    0.12       0  4989.5    0.05       0  4994.0    0.12       0
  5322.5    0.07       0  5391.8    0.12       0
Bank Sta=4989.5,4994
Exp/Cntr=0.3,0.1

Type RM Length L Ch R = 1,31028,428,428,428
BEGIN DESCRIPTION:
Potter Creek 63.0
END DESCRIPTION:
XS GIS Cut Line= 3
      2197325.02     13895525.02      2196925.00     13895125.00
      2196575.00     13894975.00
#Sta/Elev= 30
  4434.0 1083.75  4518.9 1076.74  4561.3 1075.09  4646.2 1070.23  4674.4 1069.52
  4801.7 1064.25  4914.9 1061.68  4957.3 1062.37  4985.6 1060.34  4996.2 1057.97
  5006.5 1057.53  5006.8 1057.03  5010.7 1057.03  5011.0 1057.53  5021.5 1062.84
  5043.2 1066.76  5066.8 1069.22  5130.3 1072.94  5143.8 1074.73  5161.1 1076.54
  5184.7 1079.89  5195.5 1082.01  5206.4 1083.01  5219.1 1085.07  5244.5 1086.77
  5271.7 1090.83  5289.8 1094.94  5313.4 1097.06  5347.9 1101.95  5380.5 1103.32
#Mann=5,-1,0
  4434.0    0.12       0  5006.5    0.05       0  5011.0    0.12       0
  5143.8    0.07       0  5244.5    0.12       0
Bank Sta=5006.5,5011
Exp/Cntr=0.3,0.1

Type RM Length L Ch R = 1,30600,419,419,419
BEGIN DESCRIPTION:
Potter Creek 62.0
END DESCRIPTION:
XS GIS Cut Line= 3
      2197674.99     13895324.99      2197275.00     13894925.00
      2196924.96     13894774.98
#Sta/Elev= 30
  4434.1 1098.99  4437.6 1098.99  4448.2 1096.94  4462.4 1093.24  4504.8 1086.89
  4518.9 1085.43  4542.9 1084.42  4646.2 1074.73  4737.6 1068.63  4815.9 1062.36
  4900.8 1058.22  4957.3 1056.85  4971.5 1055.74  4983.3 1053.59  4983.7 1053.09
  4987.6 1053.09  4987.9 1053.59  4996.2 1056.65  5008.8 1057.04  5021.5 1056.38
  5066.9 1056.07  5085.0 1057.52  5090.4 1058.62  5130.3 1059.17  5152.1 1062.47
  5173.8 1064.57  5279.1 1070.85  5318.9 1073.84  5337.0 1075.99  5380.6 1078.20
#Mann=6,-1,0
  4434.1    0.12       0  4542.9    0.07       0  4737.6    0.12       0
  4983.3    0.05       0  4987.9    0.12       0  5279.1    0.07       0
Bank Sta=4983.3,4987.9
Exp/Cntr=0.3,0.1

Type RM Length L Ch R = 1,30181,419,419,419
BEGIN DESCRIPTION:
Potter Creek 61.0
END DESCRIPTION:
XS GIS Cut Line= 3
      2198071.22     13895033.15      2197575.00     13894675.00
      2196924.97     13894074.97
#Sta/Elev= 30
  4392.8 1100.49  4449.1 1096.75  4474.5 1096.26  4496.8 1091.86  4553.3 1088.57
  4574.2 1084.96  4668.6 1078.66  4760.6 1069.78  4825.7 1067.43  4955.4 1059.49
  4968.0 1057.74  4976.5 1052.27  4988.9 1048.98  4989.2 1048.48  4993.5 1048.98
  4997.4 1049.08  5001.7 1051.59  5018.7 1051.73  5026.0 1053.42  5101.6 1052.48
  5330.5 1054.49  5358.6 1056.95  5485.9 1058.47  5544.6 1060.97  5577.8 1062.32
  5591.9 1064.52  5705.1 1087.02  5726.3 1092.95  5797.2 1101.44  5889.4 1107.36
#Mann=6,-1,0
  4392.8    0.07       0  4449.1    0.12       0  4988.9    0.05       0
  4993.5    0.12       0  5101.6    0.07       0  5544.6    0.12       0
Bank Sta=4988.9,4993.5
Exp/Cntr=0.3,0.1

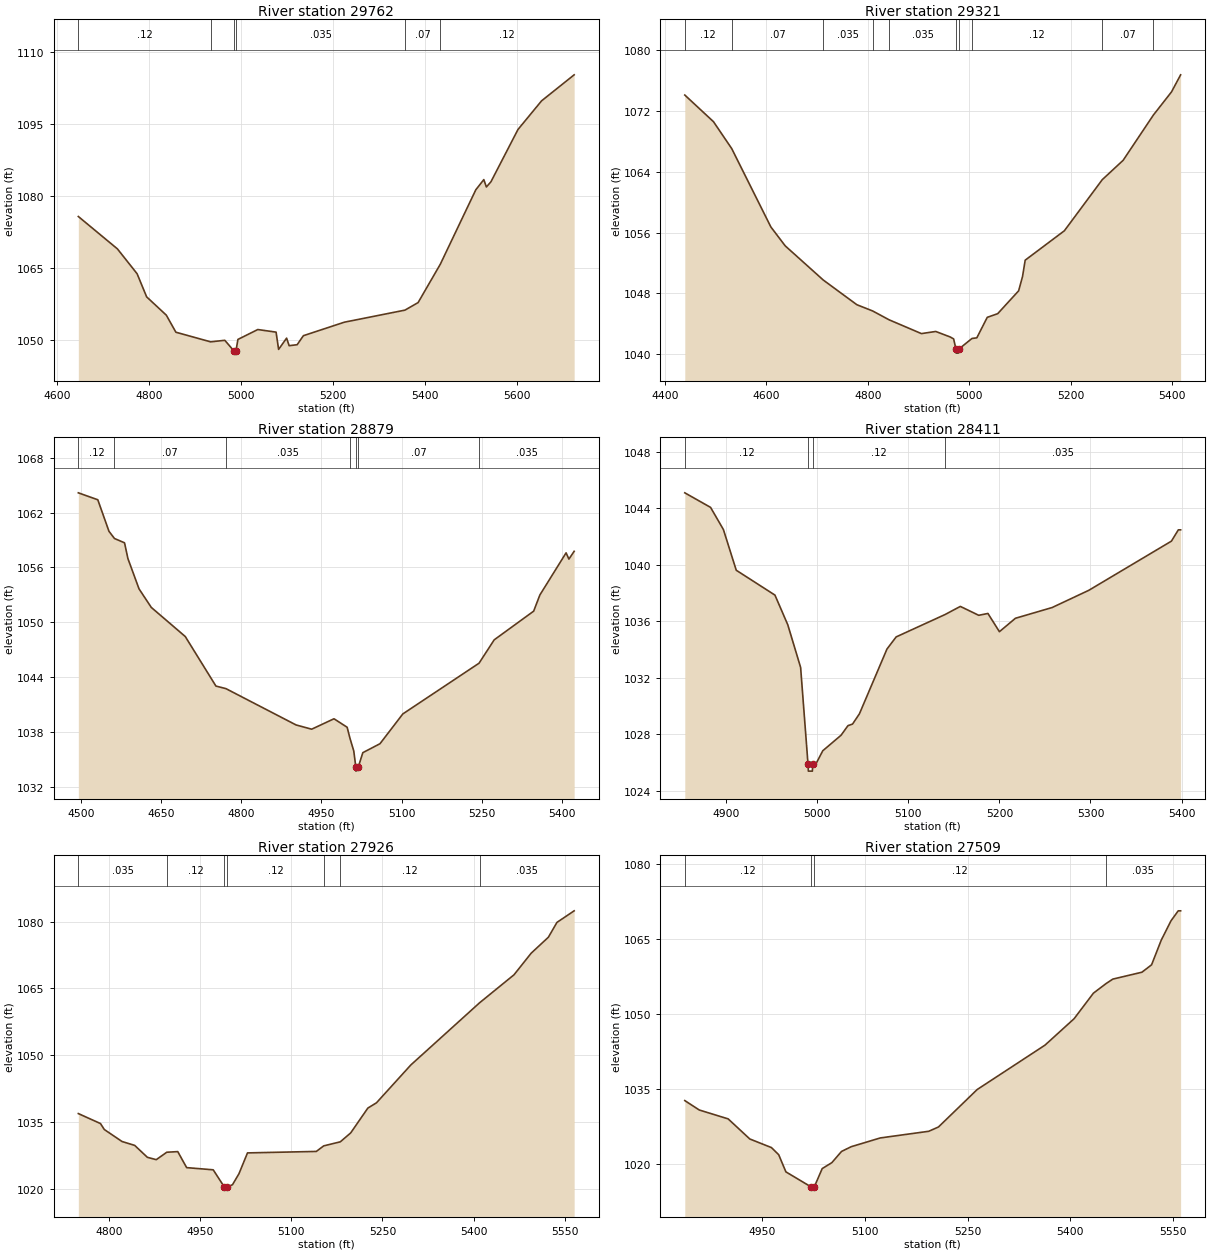
Type RM Length L Ch R = 1,29762,441,441,441
BEGIN DESCRIPTION:
Potter Creek 60.0
END DESCRIPTION:
XS GIS Cut Line= 3
      2197925.01     13894575.01      2197656.09     13894341.67
      2197000.73     13894037.86
#Sta/Elev= 30
  4646.2 1075.80  4731.2 1069.06  4774.0 1063.89  4794.8 1059.07  4837.6 1055.26
  4858.4 1051.71  4933.9 1049.71  4964.8 1050.03  4984.2 1047.86  4984.6 1047.36
  4989.1 1047.86  4993.3 1050.21  5036.5 1052.27  5076.3 1051.73  5081.8 1048.14
  5099.2 1050.48  5104.7 1048.91  5122.1 1049.11  5135.7 1050.99  5224.8 1053.80
  5356.6 1056.31  5385.2 1057.88  5433.5 1065.87  5510.7 1081.36  5528.1 1083.48
  5533.7 1081.95  5543.5 1083.01  5602.4 1093.91  5653.8 1099.88  5724.6 1105.29
#Mann=6,-1,0
  4646.2    0.12       0  4933.9   0.035       0  4984.2   0.035       0
  4989.1   0.035       0  5356.6    0.07       0  5433.5    0.12       0
Bank Sta=4984.2,4989.1
Exp/Cntr=0.3,0.1

Type RM Length L Ch R = 1,29321,442,442,442
BEGIN DESCRIPTION:
Potter Creek 59.0
END DESCRIPTION:
XS GIS Cut Line= 3
      2198175.01     13894375.01      2197775.00     13893975.00
      2197375.01     13893875.00
#Sta/Elev= 30
  4439.1 1074.10  4495.7 1070.59  4531.7 1067.05  4608.8 1056.75  4637.1 1054.26
  4712.2 1049.76  4778.5 1046.51  4809.6 1045.69  4842.2 1044.52  4905.8 1042.71
  4934.1 1042.99  4962.4 1042.27  4969.4 1042.01  4974.0 1040.64  4974.4 1040.14
  4978.6 1040.14  4979.0 1040.64  5005.6 1042.07  5015.1 1042.15  5035.7 1044.85
  5056.3 1045.33  5097.6 1048.34  5105.3 1050.23  5110.5 1052.37  5187.8 1056.24
  5262.6 1062.97  5303.7 1065.51  5363.5 1071.48  5399.1 1074.51  5417.1 1076.76
#Mann=10,-1,0
  4439.1    0.12       0  4531.7    0.07       0  4712.2   0.035       0
  4809.6    0.07       0  4842.2   0.035       0  4974.0   0.035       0
  4979.0   0.035       0  5005.6    0.12       0  5262.6    0.07       0
  5363.5    0.12       0
Bank Sta=4974,4979
Exp/Cntr=0.3,0.1

Type RM Length L Ch R = 1,28879,468,468,468
BEGIN DESCRIPTION:
Potter Creek 58.0
END DESCRIPTION:
XS GIS Cut Line= 3
      2198374.99     13894074.99      2198075.00     13893675.00
      2197674.99     13893524.99
#Sta/Elev= 30
  4495.5 1064.16  4531.9 1063.40  4552.8 1059.95  4563.1 1059.16  4581.9 1058.69
  4588.2 1056.97  4609.0 1053.65  4631.9 1051.62  4695.5 1048.43  4752.8 1043.01
  4771.5 1042.73  4902.8 1038.75  4931.9 1038.29  4973.6 1039.43  4998.2 1038.50
  5003.4 1037.31  5010.6 1035.90  5014.3 1034.20  5014.7 1033.70  5019.3 1034.20
  5027.5 1035.72  5059.6 1036.70  5102.3 1039.96  5244.8 1045.51  5273.2 1048.07
  5347.0 1051.21  5358.6 1052.98  5407.6 1057.59  5412.9 1056.91  5422.7 1057.76
#Mann=7,-1,0
  4495.5    0.12       0  4563.1    0.07       0  4771.5   0.035       0
  5003.4    0.07       0  5014.3   0.035       0  5019.3    0.07       0
  5244.8   0.035       0
Bank Sta=5014.3,5019.3
Exp/Cntr=0.3,0.1

Type RM Length L Ch R = 1,28411,485,485,485
BEGIN DESCRIPTION:
Potter Creek 57.0
END DESCRIPTION:
XS GIS Cut Line= 3
      2198474.98     13893474.98      2198375.00     13893375.00
      2197975.00     13893325.00
#Sta/Elev= 30
  4854.5 1045.08  4882.8 1044.05  4896.9 1042.48  4911.0 1039.60  4953.5 1037.84
  4967.6 1035.74  4981.7 1032.72  4989.8 1025.88  4990.2 1025.38  4994.6 1025.38
  4995.0 1025.88  4998.4 1025.88  5006.0 1026.82  5026.1 1027.92  5033.7 1028.60
  5038.7 1028.71  5046.3 1029.44  5076.5 1034.02  5086.6 1034.88  5140.5 1036.47
  5157.1 1037.04  5177.3 1036.41  5187.4 1036.54  5200.0 1035.25  5217.6 1036.20
  5257.9 1036.96  5298.2 1038.18  5388.9 1041.66  5396.5 1042.46  5399.0 1042.46
#Mann=4,-1,0
  4854.5    0.12       0  4989.8    0.05       0  4995.0    0.12       0
  5140.5   0.035       0
Bank Sta=4989.8,4995
Exp/Cntr=0.3,0.1

Type RM Length L Ch R = 1,27926,417,417,417
BEGIN DESCRIPTION:
Potter Creek 56.0
END DESCRIPTION:
XS GIS Cut Line= 3
      2198625.02     13893125.03      2198475.00     13892925.00
      2198075.02     13892525.02
#Sta/Elev= 30
  4749.7 1036.88  4786.2 1034.63  4792.4 1033.30  4821.6 1030.60  4842.4 1029.73
  4863.3 1027.05  4877.9 1026.52  4895.2 1028.19  4913.3 1028.33  4927.9 1024.73
  4971.6 1024.24  4989.8 1020.40  4990.2 1019.90  4995.0 1020.40  5003.3 1020.89
  5013.9 1023.34  5028.0 1028.04  5141.2 1028.37  5153.4 1029.62  5180.7 1030.53
  5197.7 1032.52  5226.0 1038.11  5240.2 1039.30  5296.7 1047.80  5409.7 1061.76
  5466.4 1068.06  5494.7 1072.92  5523.0 1076.51  5537.1 1079.84  5565.4 1082.44
#Mann=7,-1,0
  4749.7   0.035       0  4895.2    0.12       0  4989.8    0.05       0
  4995.0    0.12       0  5153.4    0.07       0  5180.7    0.12       0
  5409.7   0.035       0
Bank Sta=4989.8,4995
Exp/Cntr=0.3,0.1

Type RM Length L Ch R = 1,27509,472,472,472
BEGIN DESCRIPTION:
Potter Creek 55.0
END DESCRIPTION:
XS GIS Cut Line= 3
      2198875.01     13892875.02      2198825.00     13892725.00
      2198425.02     13892325.02
#Sta/Elev= 30
  4837.1 1032.75  4858.2 1030.87  4900.4 1029.09  4932.0 1025.07  4963.6 1023.35
  4974.2 1021.92  4984.7 1018.49  5020.8 1015.54  5021.2 1015.04  5025.8 1015.04
  5026.3 1015.54  5037.7 1019.15  5051.8 1020.34  5065.9 1022.58  5080.1 1023.53
  5122.5 1025.28  5193.2 1026.61  5207.4 1027.47  5263.9 1034.96  5362.9 1043.84
  5405.4 1049.13  5433.6 1054.24  5452.2 1056.17  5461.9 1057.05  5504.4 1058.43
  5518.5 1059.91  5532.6 1064.84  5546.8 1068.70  5557.4 1070.71  5560.9 1070.71
#Mann=4,-1,0
  4837.1    0.12       0  5020.8    0.05       0  5026.3    0.12       0
  5452.2   0.035       0
Bank Sta=5020.8,5026.3
Exp/Cntr=0.3,0.1

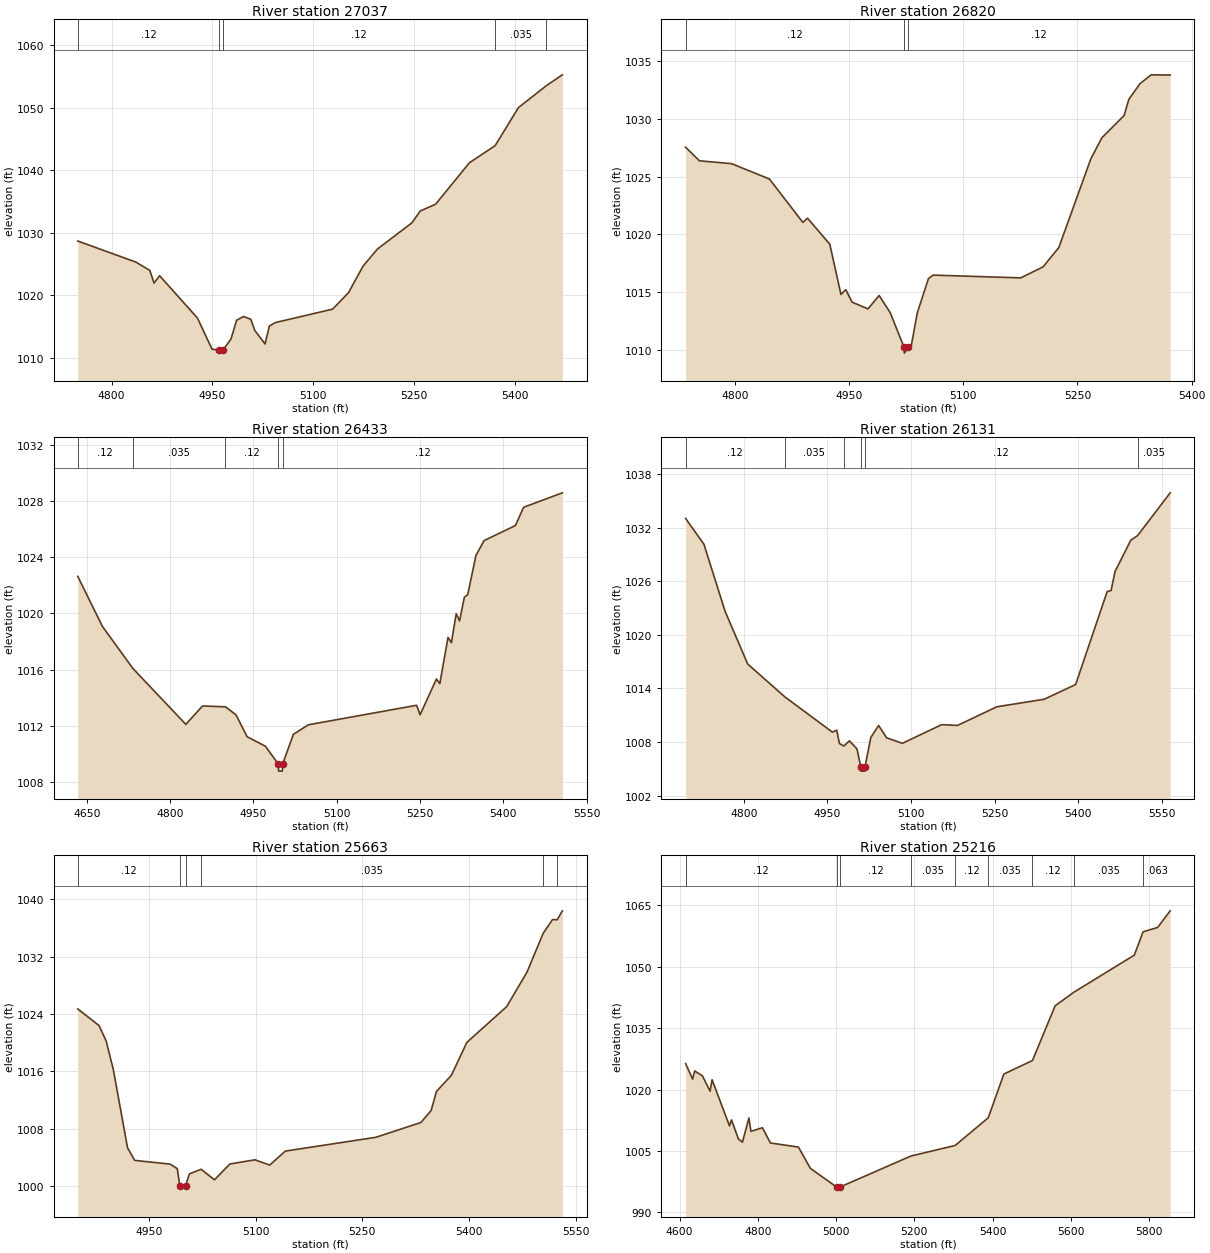
Type RM Length L Ch R = 1,27037,217,217,217
BEGIN DESCRIPTION:
Potter Creek 54.0
END DESCRIPTION:
XS GIS Cut Line= 3
      2199225.02     13892575.02      2199075.00     13892375.00
      2198675.02     13892125.01
#Sta/Elev= 30
  4749.5 1028.69  4836.0 1025.33  4856.8 1024.00  4863.1 1021.98  4871.4 1023.15
  4927.7 1016.40  4949.5 1011.41  4960.3 1011.29  4960.7 1010.79  4965.8 1011.29
  4977.7 1013.04  4986.0 1016.03  4996.4 1016.64  5007.2 1016.20  5013.1 1014.42
  5028.4 1012.26  5034.9 1015.12  5043.8 1015.67  5129.2 1017.82  5152.8 1020.46
  5174.6 1024.71  5195.9 1027.42  5247.2 1031.60  5259.6 1033.49  5282.5 1034.57
  5332.7 1041.18  5371.1 1043.92  5405.8 1050.00  5447.4 1053.50  5471.2 1055.23
#Mann=5,-1,0
  4749.5    0.12       0  4960.3    0.05       0  4965.8    0.12       0
  5371.1   0.035       0  5447.4    0.12       0
Bank Sta=4960.3,4965.8
Exp/Cntr=0.3,0.1

Type RM Length L Ch R = 1,26820,387,387,387
BEGIN DESCRIPTION:
Potter Creek 53.0
END DESCRIPTION:
XS GIS Cut Line= 2
      2199381.43     13892483.66      2199004.28     13891971.06
#Sta/Elev= 30
  4735.4 1027.56  4753.5 1026.38  4795.8 1026.13  4845.5 1024.80  4889.3 1021.04
  4895.5 1021.40  4924.8 1019.14  4939.4 1014.78  4945.7 1015.20  4954.1 1014.11
  4974.9 1013.53  4989.6 1014.69  5004.2 1013.19  5022.3 1010.19  5022.7 1009.69
  5027.9 1010.19  5031.7 1010.31  5039.7 1013.19  5054.4 1016.17  5060.6 1016.46
  5175.5 1016.22  5204.8 1017.17  5225.6 1018.86  5267.6 1026.55  5282.0 1028.37
  5311.3 1030.31  5317.5 1031.71  5332.1 1033.07  5346.8 1033.84  5371.8 1033.82
#Mann=3,-1,0
  4735.4    0.12       0  5022.3    0.05       0  5027.9    0.12       0
Bank Sta=5022.3,5027.9
Exp/Cntr=0.3,0.1

Type RM Length L Ch R = 1,26433,302,302,302
BEGIN DESCRIPTION:
Potter Creek 25.1
END DESCRIPTION:
XS GIS Cut Line= 3
      2199819.02     13892089.86      2199502.30     13892064.85
      2199052.38     13891739.91
#Sta/Elev= 30
  4633.7 1022.64  4677.9 1019.09  4732.8 1016.09  4828.3 1012.10  4858.4 1013.41
  4899.7 1013.35  4918.6 1012.78  4938.7 1011.22  4971.7 1010.54  4994.9 1009.27
  4995.4 1008.77  5002.1 1008.77  5002.6 1009.27  5022.0 1011.39  5049.0 1012.07
  5244.0 1013.46  5250.2 1012.78  5279.6 1015.33  5285.7 1015.00  5300.5 1018.29
  5306.6 1017.92  5315.2 1019.98  5321.3 1019.47  5329.9 1021.15  5336.0 1021.34
  5350.7 1024.12  5365.5 1025.19  5421.9 1026.26  5436.6 1027.56  5506.4 1028.59
#Mann=5,-1,0
  4633.7    0.12       0  4732.8   0.035       0  4899.7    0.12       0
  4994.9    0.05       0  5002.6    0.12       0
Bank Sta=4994.9,5002.6
Exp/Cntr=0.3,0.1

Type RM Length L Ch R = 1,26131,468,468,468
BEGIN DESCRIPTION:
Potter Creek 52.0
END DESCRIPTION:
XS GIS Cut Line= 3
      2199924.97     13891874.99      2199625.00     13891825.00
      2199224.99     13891424.99
#Sta/Elev= 30
  4695.4 1033.02  4728.3 1030.14  4766.3 1022.63  4806.9 1016.73  4873.7 1013.05
  4959.0 1009.11  4966.6 1009.34  4971.6 1007.83  4979.5 1007.56  4989.4 1008.14
  5003.0 1007.24  5009.8 1005.25  5010.3 1004.75  5017.0 1004.75  5017.5 1005.25
  5027.8 1008.51  5041.9 1009.86  5056.1 1008.48  5084.4 1007.86  5155.1 1009.95
  5183.4 1009.86  5254.1 1011.95  5338.9 1012.79  5395.5 1014.44  5452.1 1024.84
  5459.1 1024.96  5466.2 1027.08  5494.5 1030.59  5506.8 1031.11  5565.2 1035.89
#Mann=6,-1,0
  4695.4    0.12       0  4873.7   0.035       0  4979.5    0.12       0
  5009.8    0.05       0  5017.5    0.12       0  5506.8   0.035       0
Bank Sta=5009.8,5017.5
Exp/Cntr=0.3,0.1

Type RM Length L Ch R = 1,25663,447,447,447
BEGIN DESCRIPTION:
Potter Creek 51.0
END DESCRIPTION:
XS GIS Cut Line= 3
      2199974.98     13891425.00      2199825.00     13891425.00
      2199424.99     13891074.99
#Sta/Elev= 30
  4850.0 1024.72  4880.0 1022.39  4890.0 1020.22  4900.0 1016.25  4920.0 1005.34
  4930.0 1003.58  4980.0 1003.06  4990.0 1002.42  4993.4 1000.07  4993.9  999.57
  5001.6 1000.07  5007.1 1001.70  5023.5 1002.34  5042.2 1000.87  5064.0 1003.08
  5099.2 1003.66  5120.0 1002.93  5141.9 1004.88  5269.1 1006.80  5332.6 1008.87
  5346.9 1010.53  5354.5 1013.21  5375.4 1015.45  5397.2 1020.05  5453.2 1025.04
  5481.7 1029.84  5504.6 1035.29  5517.7 1037.19  5524.2 1037.16  5531.5 1038.41
#Mann=6,-1,0
  4850.0    0.12       0  4993.4    0.05       0  5001.6    0.12       0
  5023.5   0.035       0  5504.6    0.12       0  5524.2   0.035       0
Bank Sta=4993.4,5001.6
Exp/Cntr=0.3,0.1

Type RM Length L Ch R = 1,25216,446,446,446
BEGIN DESCRIPTION:
Potter Creek 50.0
END DESCRIPTION:
XS GIS Cut Line= 3
      2200347.10     13891103.83      2199975.00     13891025.00
      2199123.15     13890918.07
#Sta/Elev= 30
  4615.3 1026.37  4633.3 1022.56  4638.4 1024.57  4658.3 1023.37  4677.9 1019.62
  4683.0 1022.42  4727.5 1011.14  4732.6 1012.62  4750.3 1007.95  4760.6 1007.16
  4777.2 1013.08  4782.3 1009.80  4811.7 1010.70  4832.1 1006.97  4903.7 1005.97
  4934.3 1000.77  5001.6  996.20  5002.1  995.70  5009.8  996.20  5191.2 1003.78
  5304.6 1006.37  5389.1 1013.13  5429.0 1023.81  5502.1 1027.11  5560.1 1040.48
  5608.8 1043.84  5762.5 1052.85  5784.9 1058.55  5822.1 1059.61  5854.2 1063.67
#Mann=9,-1,0
  4615.3    0.12       0  5001.6    0.05       0  5009.8    0.12       0
  5191.2   0.035       0  5304.6    0.12       0  5389.1   0.035       0
  5502.1    0.12       0  5608.8   0.035       0  5784.9   0.063       0
Bank Sta=5001.6,5009.8
Exp/Cntr=0.3,0.1