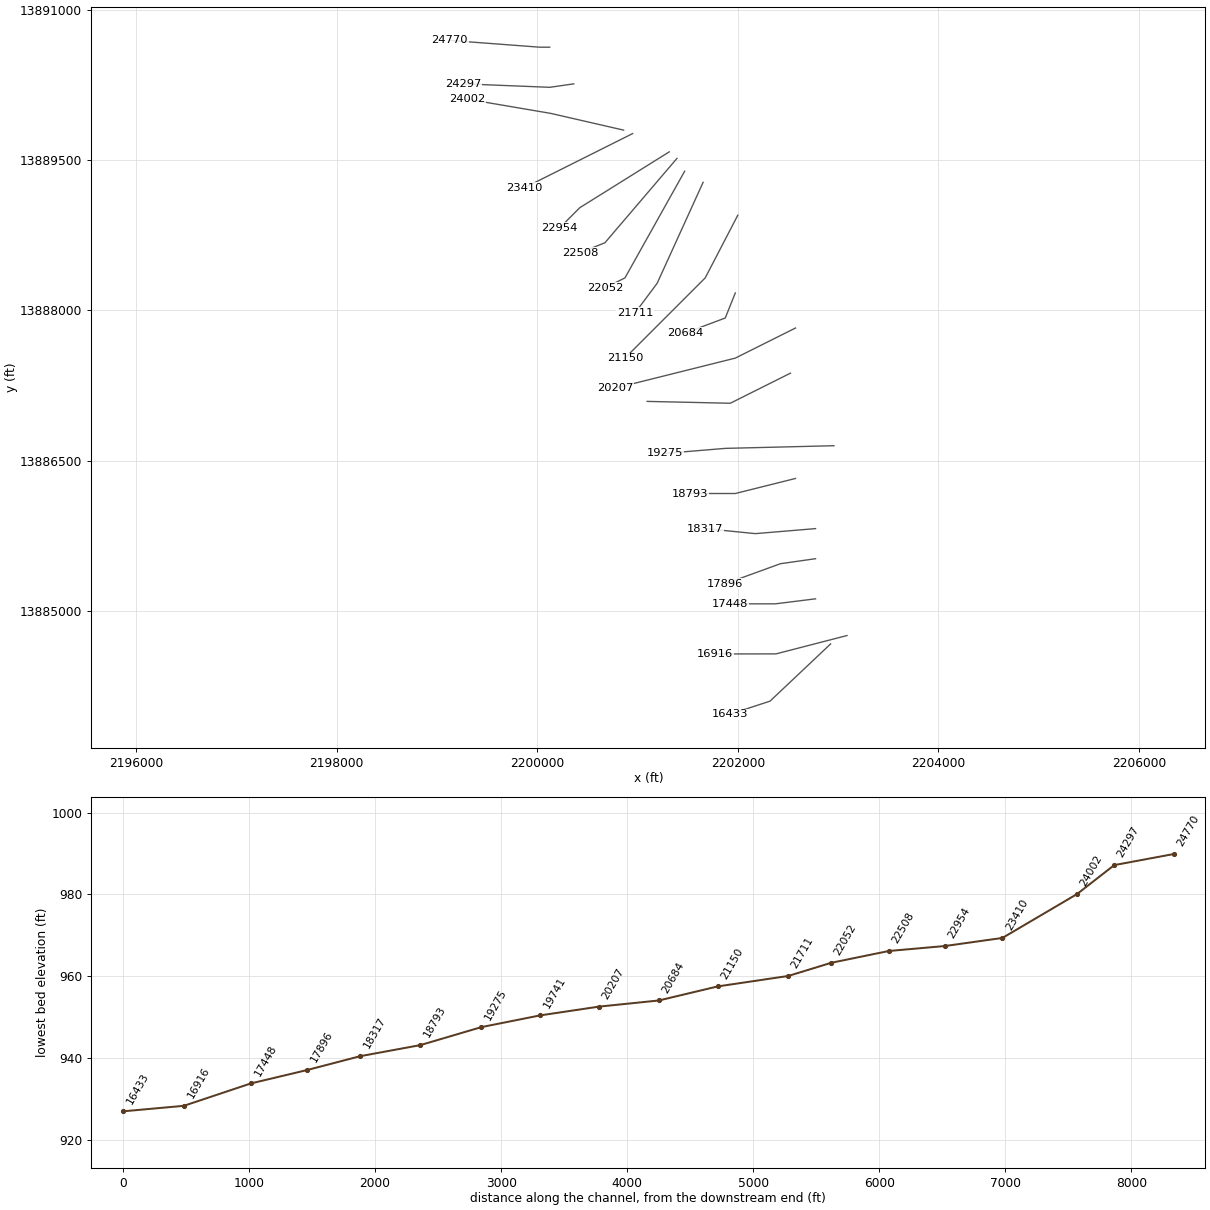
HEC-RAS study Potter Creek.prj: Potter Creek Base Level Engineering

--- Potter Creek.g01 (geometry) --- (continued)

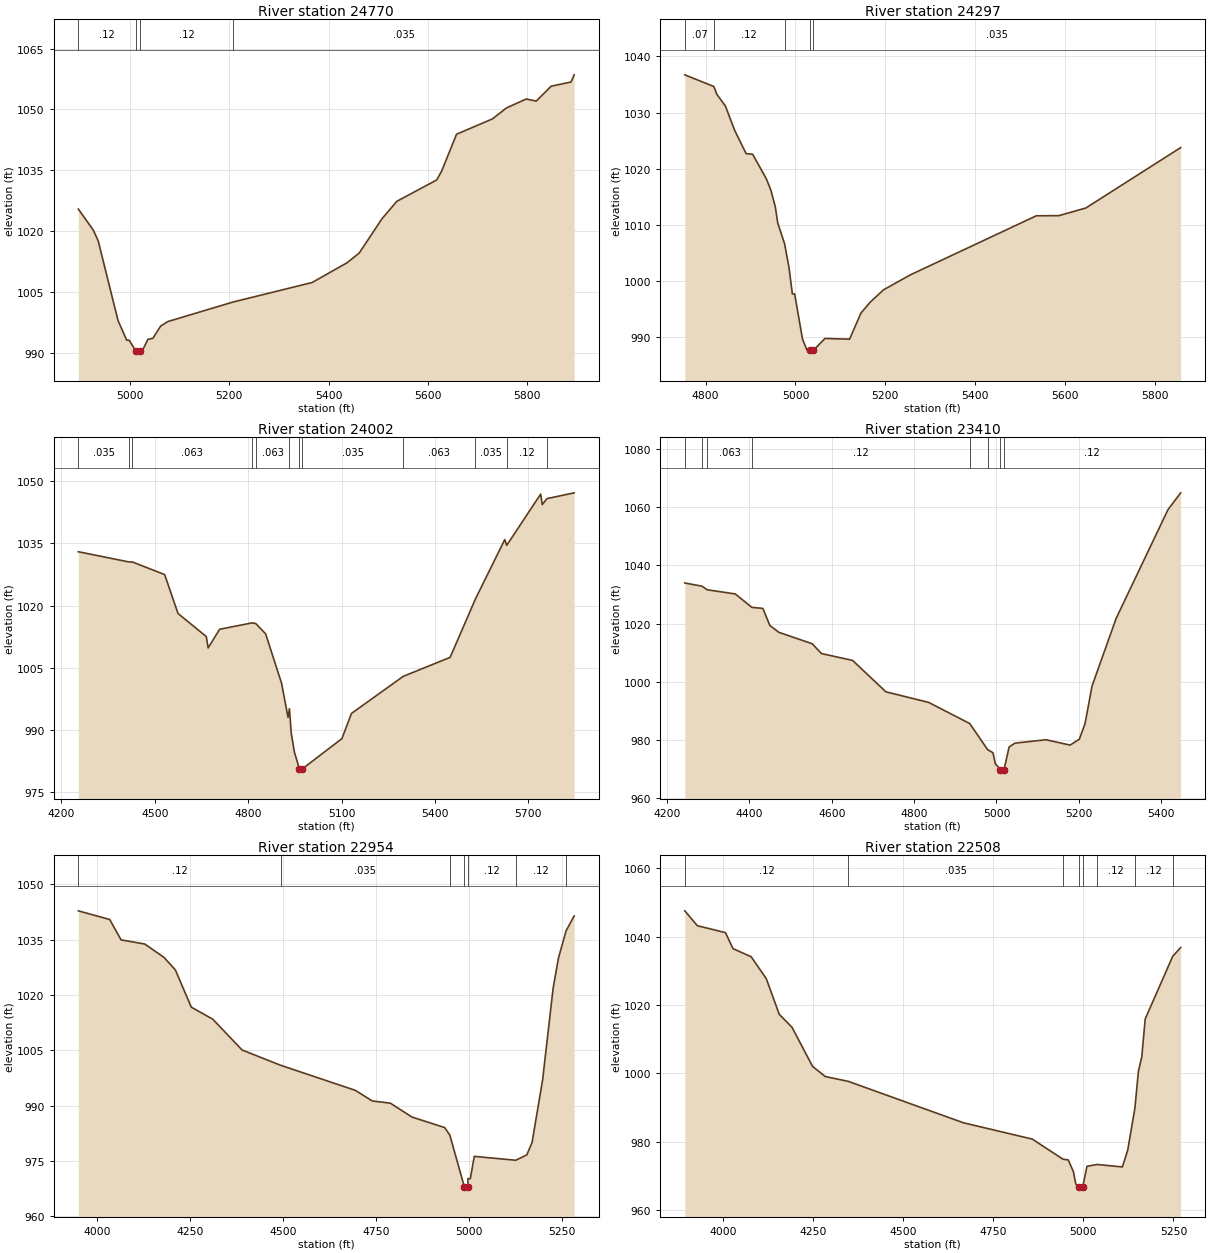
Type RM Length L Ch R = 1,24770,473,473,473
BEGIN DESCRIPTION:
Potter Creek 49.0
END DESCRIPTION:
XS GIS Cut Line= 3
      2200124.95     13890625.00      2200025.00     13890625.00
      2199128.80     13890692.61
#Sta/Elev= 30
  4895.9 1025.42  4925.9 1020.26  4935.9 1017.59  4975.9  997.91  4993.4  993.07
  4998.4  993.07  5011.7  990.39  5012.2  989.89  5020.2  990.39  5025.9  990.76
  5036.0  993.29  5046.0  993.54  5061.7  996.56  5076.1  997.67  5207.5 1002.49
  5366.9 1007.31  5437.1 1012.17  5461.7 1014.57  5507.3 1022.99  5537.4 1027.33
  5617.6 1032.58  5627.6 1034.74  5657.7 1043.87  5730.0 1047.65  5758.0 1050.34
  5798.1 1052.56  5818.2 1052.04  5848.3 1055.72  5888.4 1056.75  5894.6 1058.52
#Mann=4,-1,0
  4895.9    0.12       0  5011.7    0.05       0  5020.2    0.12       0
  5207.5   0.035       0
Bank Sta=5011.7,5020.2
Exp/Cntr=0.3,0.1

Type RM Length L Ch R = 1,24297,295,295,295
BEGIN DESCRIPTION:
Potter Creek 48.0
END DESCRIPTION:
XS GIS Cut Line= 3
      2200364.47     13890259.65      2200125.00     13890225.00
      2199264.16     13890259.64
#Sta/Elev= 30
  4753.7 1036.72  4818.4 1034.64  4825.0 1033.26  4844.1 1031.17  4864.3 1026.91
  4890.2 1022.69  4904.7 1022.58  4935.0 1018.24  4945.1 1016.23  4955.2 1013.21
  4960.5 1010.35  4975.7 1006.68  4985.6 1002.42  4993.1  997.72  4998.2  997.72
  5015.7  989.67  5025.7  987.71  5031.4  987.68  5031.9  987.18  5039.9  987.68
  5065.7  989.79  5120.4  989.66  5145.8  994.32  5165.8  996.21  5195.8  998.44
  5255.9 1001.12  5536.1 1011.63  5586.1 1011.65  5646.2 1013.01  5857.2 1023.76
#Mann=5,-1,0
  4753.7    0.07       0  4818.4    0.12       0  4975.7   0.035       0
  5031.4   0.035       0  5039.9   0.035       0
Bank Sta=5031.4,5039.9
Exp/Cntr=0.3,0.1

Type RM Length L Ch R = 1,24002,592,592,592
BEGIN DESCRIPTION:
Potter Creek 47.0
END DESCRIPTION:
XS GIS Cut Line= 3
      2200861.34     13889798.22      2200134.74     13889965.01
      2199299.89     13890107.40
#Sta/Elev= 30
  4254.5 1033.00  4416.7 1030.54  4427.5 1030.55  4531.8 1027.49  4574.6 1018.12
  4665.5 1012.55  4671.4 1009.82  4708.4 1014.31  4813.4 1015.86  4824.7 1015.67
  4856.1 1013.20  4907.4 1001.26  4927.9  993.07  4932.5  995.16  4938.2  989.32
  4948.4  984.71  4964.7  980.61  4965.2  980.11  4973.2  980.61  5101.2  987.96
  5131.6  994.01  5297.6 1002.94  5448.6 1007.54  5529.8 1021.60  5624.0 1035.93
  5630.3 1034.54  5739.3 1046.89  5744.4 1044.35  5759.5 1045.80  5846.9 1047.20
#Mann=12,-1,0
  4254.5   0.035       0  4416.7    0.12       0  4427.5   0.063       0
  4813.4   0.035       0  4824.7   0.063       0  4932.5   0.035       0
  4964.7   0.035       0  4973.2   0.035       0  5297.6   0.063       0
  5529.8   0.035       0  5630.3    0.12       0  5759.5   0.035       0
Bank Sta=4964.7,4973.2
Exp/Cntr=0.3,0.1

Type RM Length L Ch R = 1,23410,456,456,456
BEGIN DESCRIPTION:
Potter Creek 46.0
END DESCRIPTION:
XS GIS Cut Line= 3
      2200951.64     13889763.89      2200275.00     13889425.00
      2199874.97     13889224.99
#Sta/Elev= 30
  4243.2 1033.92  4284.9 1032.83  4297.4 1031.60  4365.8 1030.16  4406.0 1025.56
  4432.8 1025.20  4449.6 1019.37  4472.0 1016.97  4552.6 1013.08  4575.0 1009.72
  4650.7 1007.35  4731.5  996.59  4835.1  992.97  4935.2  985.70  4978.6  976.74
  4991.6  975.68  4997.2  971.95  5009.5  969.88  5010.0  969.38  5018.4  969.88
  5030.7  977.64  5044.7  978.97  5120.1  980.15  5178.8  978.31  5201.2  980.32
  5215.2  985.71  5232.0  998.52  5290.6 1021.76  5416.4 1059.05  5447.2 1064.85
#Mann=8,-1,0
  4243.2   0.063       0  4284.9   0.035       0  4297.4   0.063       0
  4406.0    0.12       0  4935.2   0.035       0  4978.6    0.12       0
  5009.5    0.05       0  5018.4    0.12       0
Bank Sta=5009.5,5018.4
Exp/Cntr=0.3,0.1

Type RM Length L Ch R = 1,22954,446,446,446
BEGIN DESCRIPTION:
Potter Creek 45.0
END DESCRIPTION:
XS GIS Cut Line= 3
      2201316.48     13889581.61      2200425.00     13889025.00
      2200225.01     13888825.01
#Sta/Elev= 30
  3949.0 1042.77  4033.4 1040.42  4064.0 1034.90  4127.7 1033.78  4179.6 1030.15
  4210.1 1026.77  4252.8 1016.69  4310.6 1013.43  4389.6 1005.08  4492.9 1000.96
  4693.9  994.17  4739.9  991.28  4788.3  990.69  4846.7  986.92  4934.5  984.08
  4948.4  982.03  4987.8  967.91  4988.3  967.41  4996.9  967.91  4997.0  970.24
  5003.5  970.24  5014.1  976.28  5125.7  975.23  5155.5  976.68  5169.7  980.09
  5198.0  997.03  5226.2 1021.79  5240.4 1029.90  5261.0 1037.33  5282.8 1041.37
#Mann=7,-1,0
  3949.0    0.12       0  4492.9   0.035       0  4948.4    0.12       0
  4987.8    0.05       0  4996.9    0.12       0  5125.7    0.12       0
  5261.0    0.12       0
Bank Sta=4987.8,4996.9
Exp/Cntr=0.3,0.1

Type RM Length L Ch R = 1,22508,456,456,456
BEGIN DESCRIPTION:
Potter Creek 44.0
END DESCRIPTION:
XS GIS Cut Line= 3
      2201393.03     13889516.05      2200675.00     13888675.00
      2200425.02     13888575.01
#Sta/Elev= 30
  3894.8 1047.52  3929.7 1043.17  4007.6 1041.15  4028.5 1036.47  4079.0 1034.09
  4120.7 1027.71  4156.9 1017.26  4192.1 1013.50  4249.2 1002.05  4284.3  999.10
  4348.6  997.67  4667.5  985.58  4858.5  980.81  4943.8  974.93  4958.4  974.72
  4972.7  971.24  4979.2  967.68  4989.0  966.69  4989.5  966.19  4998.1  966.69
  5010.1  972.85  5038.3  973.40  5108.4  972.67  5123.2  977.58  5143.2  989.92
  5152.8 1000.64  5162.2 1004.83  5171.6 1015.90  5248.0 1034.23  5269.9 1036.78
#Mann=8,-1,0
  3894.8    0.12       0  4348.6   0.035       0  4943.8    0.12       0
  4989.0    0.05       0  4998.1    0.12       0  5038.3    0.12       0
  5143.2    0.12       0  5248.0   0.035       0
Bank Sta=4989,4998.1
Exp/Cntr=0.3,0.1

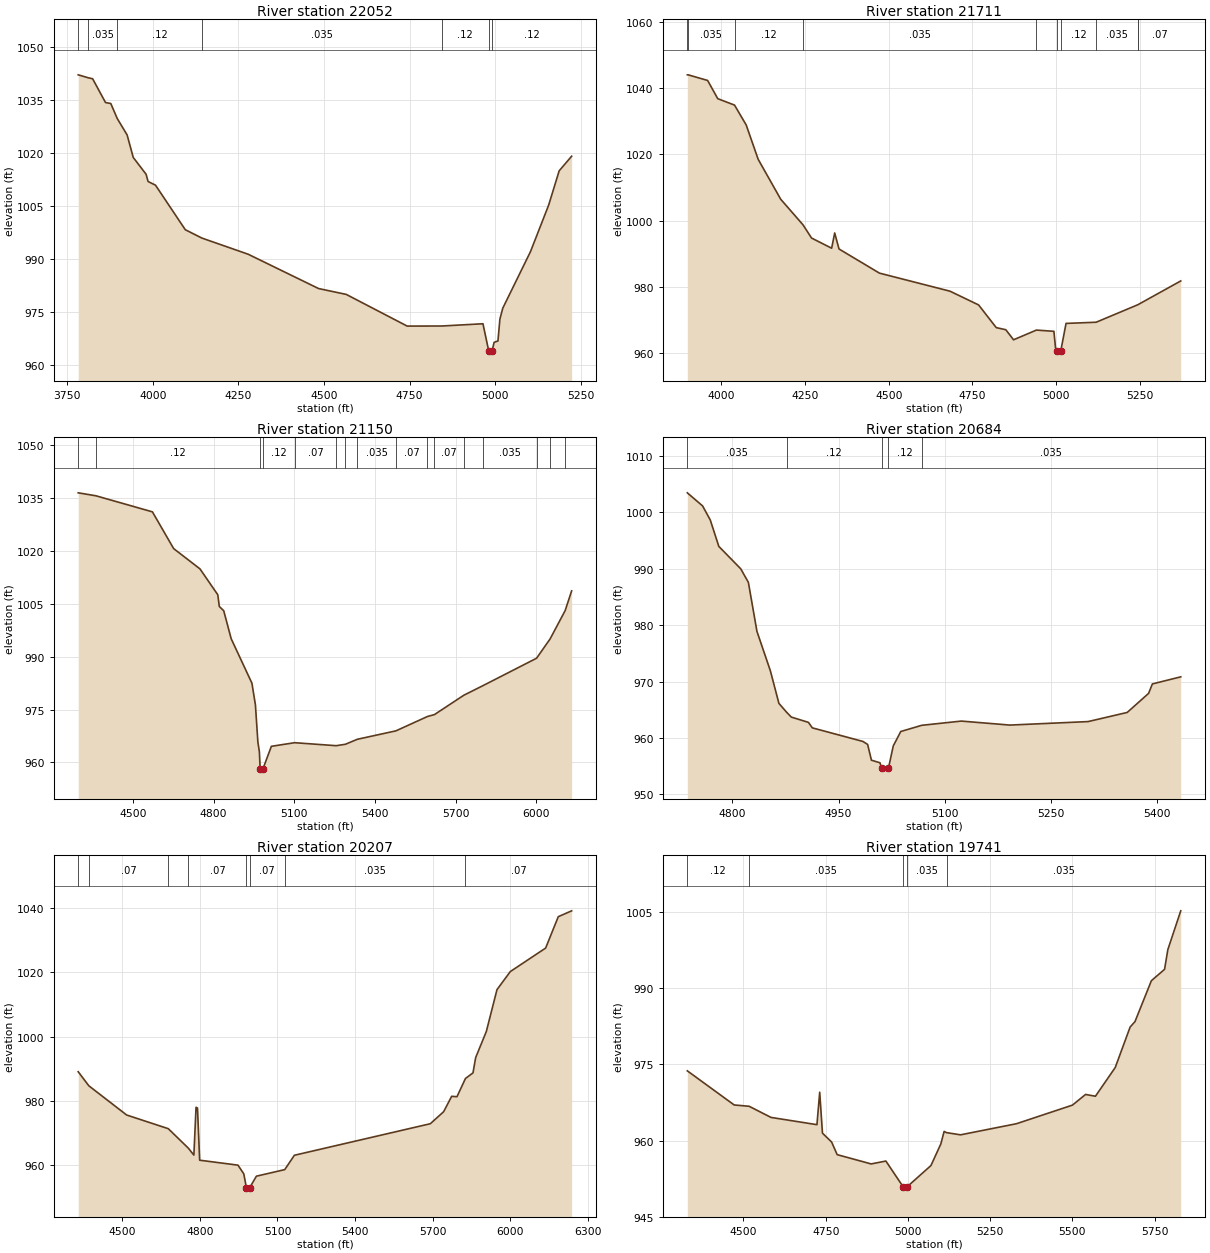
Type RM Length L Ch R = 1,22052,341,341,341
BEGIN DESCRIPTION:
Potter Creek 43.0
END DESCRIPTION:
XS GIS Cut Line= 3
      2201469.82     13889388.06      2200875.00     13888325.00
      2200674.97     13888224.98
#Sta/Elev= 30
  3781.8 1042.24  3811.7 1041.39  3823.9 1041.13  3861.6 1034.38  3877.0 1034.11
  3895.8 1029.86  3924.8 1025.18  3942.6 1018.81  3980.1 1014.05  3986.0 1011.99
  4007.7 1010.94  4094.7  998.31  4143.3  995.94  4278.4  991.36  4484.3  981.62
  4564.9  979.97  4743.0  970.98  4843.8  971.00  4964.5  971.64  4981.6  963.81
  4982.1  963.31  4990.8  963.81  4997.1  966.38  5008.3  966.75  5013.9  972.91
  5022.3  976.04  5103.4  992.10  5156.5 1005.30  5187.2 1015.02  5223.6 1019.15
#Mann=7,-1,0
  3781.8    0.12       0  3811.7   0.035       0  3895.8    0.12       0
  4143.3   0.035       0  4843.8    0.12       0  4981.6    0.05       0
  4990.8    0.12       0
Bank Sta=4981.6,4990.8
Exp/Cntr=0.3,0.1

Type RM Length L Ch R = 1,21711,561,561,561
BEGIN DESCRIPTION:
Potter Creek 42.0
END DESCRIPTION:
XS GIS Cut Line= 3
      2201654.03     13889277.84      2201196.02     13888271.36
      2200974.99     13887974.99
#Sta/Elev= 30
  3897.8 1044.02  3900.3 1044.02  3958.6 1042.32  3988.8 1036.83  4039.0 1034.89
  4073.9 1028.89  4109.7 1018.54  4177.1 1006.50  4243.7  998.79  4269.3  994.80
  4329.4  991.73  4338.5  996.33  4351.4  991.50  4472.2  984.22  4683.3  978.77
  4768.9  974.62  4821.6  967.78  4850.2  967.15  4873.3  964.11  4941.7  967.04
  4994.0  966.67  4998.8  961.74  5004.7  960.59  5005.2  960.09  5014.2  960.59
  5030.3  969.05  5120.4  969.41  5244.7  974.67  5246.2  974.75  5373.3  981.86
#Mann=10,-1,0
  3897.8    0.12       0  3900.3   0.035       0  4039.0    0.12       0
  4243.7   0.035       0  4941.7    0.12       0  5004.7    0.05       0
  5014.2    0.12       0  5120.4   0.035       0  5244.7    0.12       0
  5246.2    0.07       0
Bank Sta=5004.7,5014.2
Exp/Cntr=0.3,0.1

Type RM Length L Ch R = 1,21150,466,466,466
BEGIN DESCRIPTION:
Potter Creek 41.0
END DESCRIPTION:
XS GIS Cut Line= 3
      2201999.99     13888949.98      2201675.00     13888325.00
      2200875.00     13887525.00
#Sta/Elev= 30
  4296.1 1036.53  4361.9 1035.69  4572.2 1031.13  4651.1 1020.71  4749.1 1014.94
  4815.4 1007.60  4821.1 1004.27  4837.5 1003.06  4865.3  995.10  4942.4  982.49
  4955.4  976.35  4964.6  965.77  4970.2  963.01  4973.1  958.03  4973.6  957.53
  4982.8  958.03  5014.7  964.57  5101.3  965.60  5255.8  964.75  5290.0  965.15
  5334.7  966.57  5478.1  968.96  5595.6  973.04  5621.5  973.58  5730.9  979.08
  5803.4  981.85  6001.5  989.58  6051.8  995.06  6107.8 1003.10  6131.9 1008.69
#Mann=16,-1,0
  4296.1    0.07       0  4361.9    0.12       0  4973.1    0.05       0
  4982.8    0.12       0  5101.3    0.07       0  5255.8    0.12       0
  5290.0    0.07       0  5334.7   0.035       0  5478.1    0.07       0
  5595.6   0.035       0  5621.5    0.07       0  5730.9    0.12       0
  5803.4   0.035       0  6001.5    0.07       0  6051.8   0.035       0
  6107.8    0.07       0
Bank Sta=4973.1,4982.8
Exp/Cntr=0.3,0.1

Type RM Length L Ch R = 1,20684,477,477,477
BEGIN DESCRIPTION:
Potter Creek 40.0
END DESCRIPTION:
XS GIS Cut Line= 3
      2201975.02     13888175.04      2201875.00     13887925.00
      2201475.00     13887775.00
#Sta/Elev= 30
  4736.5 1003.48  4758.1 1001.15  4768.9  998.66  4781.0  993.97  4811.9  990.00
  4822.7  987.59  4834.8  978.89  4853.7  971.92  4865.8  966.12  4876.6  964.56
  4883.3  963.69  4907.5  962.75  4912.9  961.78  4984.3  959.37  4991.0  958.84
  4996.4  956.04  5008.5  955.58  5010.7  954.60  5011.2  954.10  5020.4  954.60
  5027.2  958.57  5037.8  961.13  5067.4  962.23  5123.3  962.98  5191.8  962.27
  5302.2  962.89  5357.4  964.51  5387.6  967.89  5393.0  969.57  5433.0  970.83
#Mann=5,-1,0
  4736.5   0.035       0  4876.6    0.12       0  5010.7    0.05       0
  5020.4    0.12       0  5067.4   0.035       0
Bank Sta=5010.7,5020.4
Exp/Cntr=0.3,0.1

Type RM Length L Ch R = 1,20207,466,466,466
BEGIN DESCRIPTION:
Potter Creek 39.0
END DESCRIPTION:
XS GIS Cut Line= 3
      2202575.01     13887825.00      2201975.00     13887525.00
      2200774.96     13887224.99
#Sta/Elev= 30
  4329.6  989.07  4370.6  984.70  4516.9  975.62  4677.9  971.37  4755.3  965.33
  4776.8  963.17  4785.2  978.02  4790.8  977.78  4799.2  961.58  4947.3  960.04
  4969.7  957.35  4979.9  953.09  4980.4  952.59  4993.0  953.09  5018.5  956.61
  5128.1  958.65  5165.4  963.11  5691.0  972.91  5742.6  976.65  5773.5  981.43
  5794.1  981.31  5826.9  986.97  5856.0  988.70  5866.3  993.45  5907.5 1001.55
  5948.7 1014.56  6000.3 1020.19  6136.9 1027.49  6185.8 1037.24  6237.4 1039.06
#Mann=8,-1,0
  4329.6    0.12       0  4370.6    0.07       0  4677.9   0.035       0
  4755.3    0.07       0  4979.9    0.05       0  4993.0    0.07       0
  5128.1   0.035       0  5826.9    0.07       0
Bank Sta=4979.9,4993
Exp/Cntr=0.3,0.1

Type RM Length L Ch R = 1,19741,466,466,466
BEGIN DESCRIPTION:
Potter Creek 38.0
END DESCRIPTION:
XS GIS Cut Line= 3
      2202524.98     13887374.99      2201925.00     13887075.00
      2201095.81     13887093.40
#Sta/Elev= 30
  4329.3  973.74  4471.8  967.02  4517.3  966.76  4583.6  964.57  4723.4  963.14
  4731.8  969.53  4740.2  961.47  4768.1  959.72  4784.9  957.24  4888.3  955.41
  4933.0  955.98  4985.1  950.95  4985.6  950.45  4998.3  950.95  5070.1  955.10
  5100.1  959.35  5110.1  961.81  5117.4  961.57  5160.1  961.14  5330.2  963.33
  5500.2  966.99  5540.2  969.09  5570.2  968.74  5630.3  974.39  5675.7  982.37
  5690.3  983.42  5740.3  991.49  5780.3  993.72  5790.3  997.61  5829.5 1005.24
#Mann=5,-1,0
  4329.3    0.12       0  4517.3   0.035       0  4985.1    0.05       0
  4998.3   0.035       0  5117.4   0.035       0
Bank Sta=4985.1,4998.3
Exp/Cntr=0.3,0.1

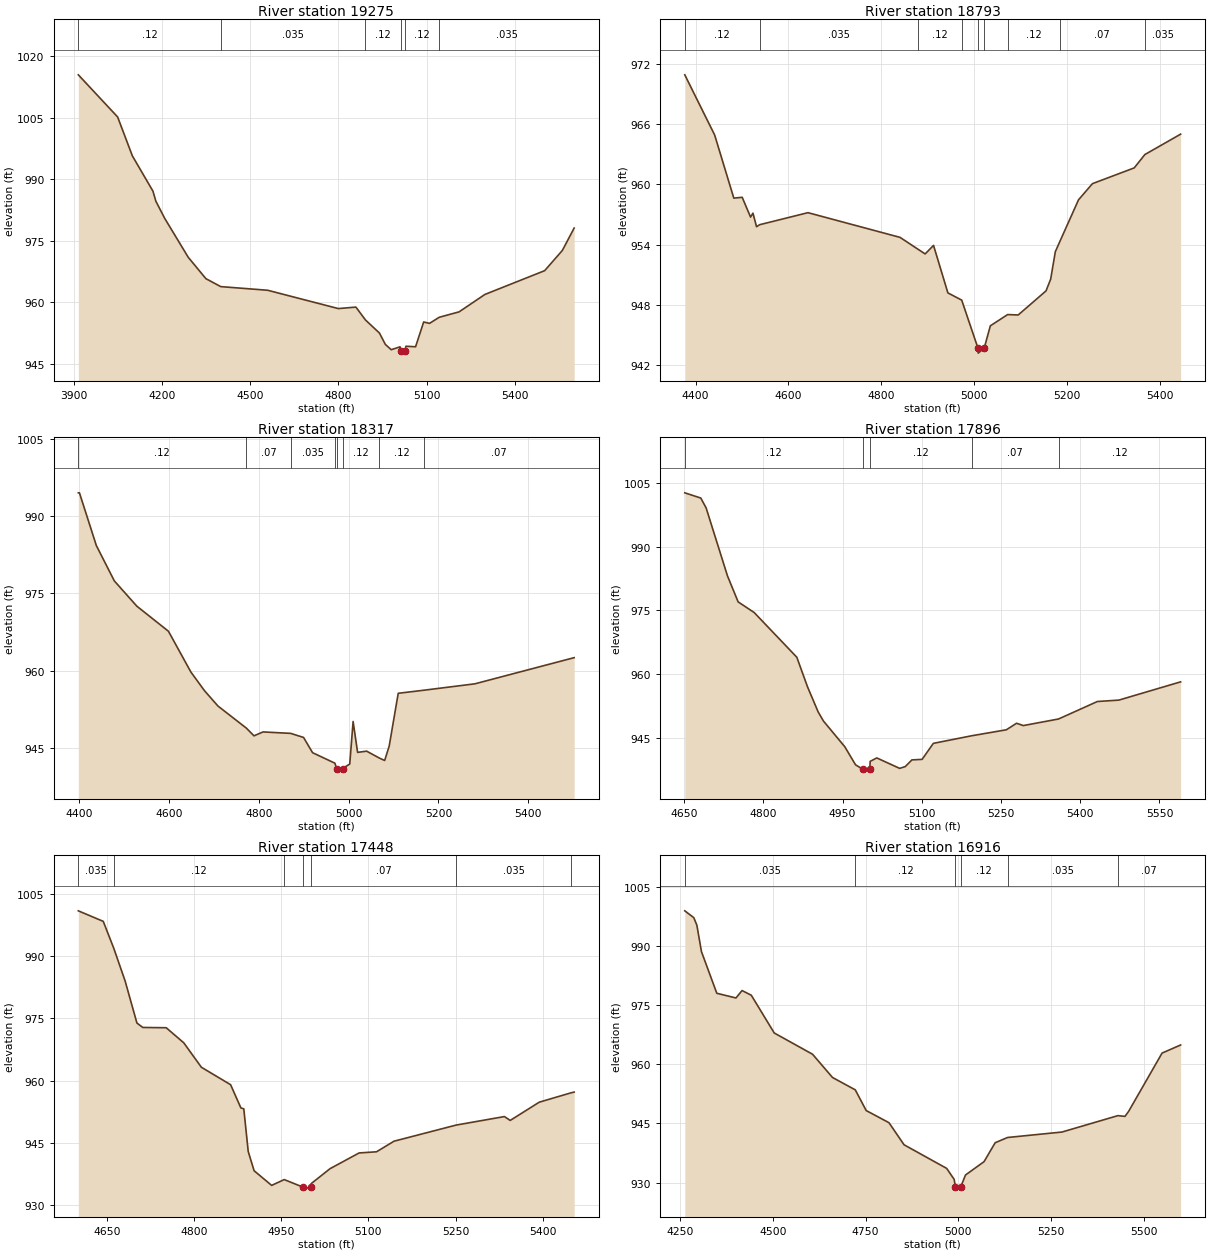
Type RM Length L Ch R = 1,19275,482,482,482
BEGIN DESCRIPTION:
Potter Creek 37.0
END DESCRIPTION:
XS GIS Cut Line= 3
      2202958.64     13886651.50      2201875.00     13886625.00
      2201275.05     13886575.00
#Sta/Elev= 30
  3916.0 1015.49  4049.7 1005.20  4099.7  995.72  4169.7  987.11  4179.7  984.65
  4209.7  980.47  4289.8  970.96  4349.8  965.75  4400.3  963.81  4559.8  962.92
  4800.2  958.45  4859.9  958.81  4892.3  955.68  4939.9  952.48  4960.0  949.71
  4980.0  948.41  5010.0  949.12  5013.4  948.08  5013.9  947.58  5026.7  948.08
  5030.1  949.26  5062.7  949.13  5090.3  955.18  5110.3  954.84  5142.9  956.32
  5210.7  957.65  5298.5  961.90  5501.7  967.70  5561.9  972.64  5602.0  978.10
#Mann=6,-1,0
  3916.0    0.12       0  4400.3   0.035       0  4892.3    0.12       0
  5013.4    0.05       0  5026.7    0.12       0  5142.9   0.035       0
Bank Sta=5013.4,5026.7
Exp/Cntr=0.3,0.1

Type RM Length L Ch R = 1,18793,476,476,476
BEGIN DESCRIPTION:
Potter Creek 36.0
END DESCRIPTION:
XS GIS Cut Line= 3
      2202574.98     13886324.99      2201975.00     13886175.00
      2201525.04     13886175.00
#Sta/Elev= 30
  4376.9  970.92  4441.3  964.92  4482.5  958.64  4500.6  958.72  4518.6  956.75
  4523.8  957.14  4531.5  955.79  4538.1  955.99  4642.3  957.19  4840.7  954.73
  4879.0  953.56  4894.8  953.08  4912.9  953.93  4943.8  949.20  4973.6  948.48
  5008.6  943.70  5009.1  943.20  5022.1  943.70  5035.3  945.92  5072.6  947.04
  5095.3  947.00  5155.3  949.40  5165.3  950.57  5175.3  953.30  5184.7  954.28
  5225.3  958.47  5255.3  960.08  5345.3  961.65  5368.3  962.98  5445.3  965.01
#Mann=9,-1,0
  4376.9    0.12       0  4538.1   0.035       0  4879.0    0.12       0
  4973.6    0.12       0  5008.6    0.05       0  5022.1    0.12       0
  5072.6    0.12       0  5184.7    0.07       0  5368.3   0.035       0
Bank Sta=5008.6,5022.1
Exp/Cntr=0.3,0.1

Type RM Length L Ch R = 1,18317,421,421,421
BEGIN DESCRIPTION:
Potter Creek 35.0
END DESCRIPTION:
XS GIS Cut Line= 3
      2202774.97     13885825.00      2202175.00     13885775.00
      2201675.04     13885825.00
#Sta/Elev= 30
  4397.9  994.53  4400.4  994.53  4438.0  984.30  4478.1  977.43  4528.3  972.52
  4598.6  967.66  4648.7  959.73  4678.8  956.13  4708.9  953.14  4772.2  948.85
  4789.2  947.35  4809.3  948.11  4870.8  947.83  4899.6  947.04  4919.7  944.08
  4969.5  942.04  4973.1  941.00  4973.6  940.50  4986.6  941.00  5002.5  941.88
  5010.0  950.14  5020.0  944.14  5040.1  944.38  5068.6  943.03  5080.3  942.57
  5090.4  945.37  5110.5  955.61  5167.9  956.21  5281.3  957.45  5502.4  962.53
#Mann=8,-1,0
  4397.9    0.12       0  4772.2    0.07       0  4870.8   0.035       0
  4969.5    0.12       0  4973.1    0.05       0  4986.6    0.12       0
  5068.6    0.12       0  5167.9    0.07       0
Bank Sta=4973.1,4986.6
Exp/Cntr=0.3,0.1

Type RM Length L Ch R = 1,17896,448,448,448
BEGIN DESCRIPTION:
Potter Creek 34.0
END DESCRIPTION:
XS GIS Cut Line= 3
      2202775.01     13885525.00      2202425.00     13885475.00
      2201875.00     13885275.00
#Sta/Elev= 30
  4651.2 1002.68  4681.5 1001.45  4691.6  999.12  4732.0  983.12  4752.2  976.99
  4782.5  974.49  4863.3  963.95  4883.5  957.00  4903.7  951.07  4913.8  948.91
  4954.3  942.84  4974.5  938.60  4987.8  937.62  4988.3  937.12  5001.5  937.62
  5002.2  939.42  5014.7  940.23  5058.0  937.77  5068.6  938.19  5081.2  939.76
  5100.5  939.89  5121.8  943.66  5194.4  945.45  5260.1  946.86  5279.4  948.40
  5292.1  947.85  5358.8  949.40  5432.4  953.52  5473.0  953.85  5590.0  958.15
#Mann=5,-1,0
  4651.2    0.12       0  4987.8    0.05       0  5001.5    0.12       0
  5194.4    0.07       0  5358.8    0.12       0
Bank Sta=4987.8,5001.5
Exp/Cntr=0.3,0.1

Type RM Length L Ch R = 1,17448,532,532,532
BEGIN DESCRIPTION:
Potter Creek 33.0
END DESCRIPTION:
XS GIS Cut Line= 3
      2202775.02     13885125.00      2202375.00     13885075.00
      2201925.03     13885075.00
#Sta/Elev= 30
  4600.9 1000.91  4643.8  998.37  4662.0  991.84  4681.5  983.96  4701.7  973.87
  4711.8  972.80  4752.1  972.73  4782.3  969.10  4812.6  963.21  4862.9  959.00
  4880.6  953.40  4885.6  953.18  4893.2  942.92  4903.3  938.27  4933.5  934.73
  4955.2  936.13  4987.1  934.33  4987.6  933.83  5000.9  934.33  5001.5  935.15
  5034.0  938.76  5084.0  942.55  5114.0  942.83  5144.0  945.38  5251.0  949.27
  5334.0  951.32  5344.0  950.39  5394.0  954.79  5448.1  957.02  5454.0  957.22
#Mann=7,-1,0
  4600.9   0.035       0  4662.0    0.12       0  4955.2    0.07       0
  4987.1    0.05       0  5000.9    0.07       0  5251.0   0.035       0
  5448.1    0.07       0
Bank Sta=4987.1,5000.9
Exp/Cntr=0.3,0.1

Type RM Length L Ch R = 1,16916,483,483,483
BEGIN DESCRIPTION:
Potter Creek 32.0
END DESCRIPTION:
XS GIS Cut Line= 3
      2203088.56     13884758.87      2202380.91     13884576.04
      2201774.99     13884575.00
#Sta/Elev= 30
  4262.8  998.91  4287.1  997.17  4295.3  995.28  4307.8  988.55  4349.1  978.01
  4400.7  976.82  4417.2  978.70  4442.1  977.51  4504.0  967.94  4607.3  962.55
  4661.1  956.66  4722.4  953.53  4751.9  948.28  4813.3  945.20  4854.0  939.60
  4968.8  933.62  4989.0  930.84  4992.6  928.86  4993.1  928.36  5006.5  928.86
  5019.6  931.94  5069.6  935.32  5099.6  940.12  5133.0  941.45  5279.6  942.83
  5430.5  946.99  5449.6  946.80  5459.6  948.10  5549.6  962.85  5599.6  964.90
#Mann=6,-1,0
  4262.8   0.035       0  4722.4    0.12       0  4992.6    0.05       0
  5006.5    0.12       0  5133.0   0.035       0  5430.5    0.07       0
Bank Sta=4992.6,5006.5
Exp/Cntr=0.3,0.1

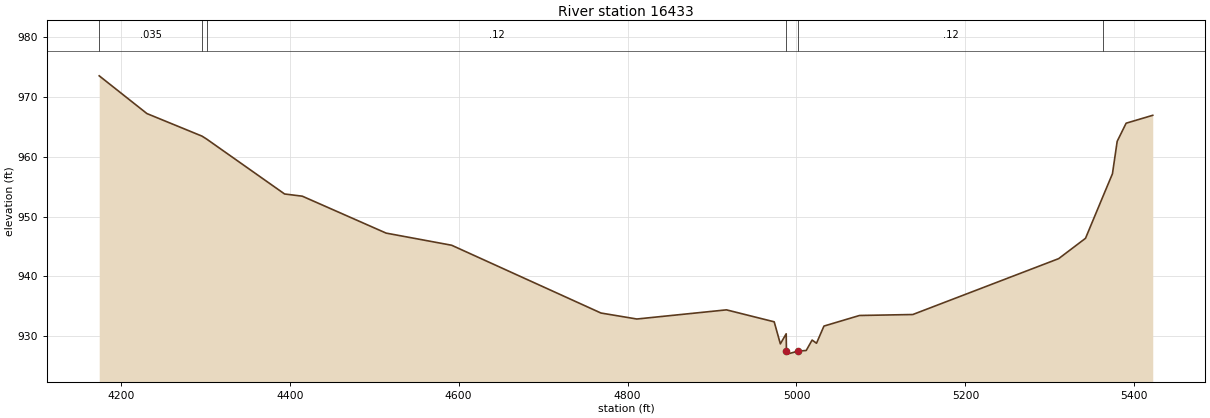
Type RM Length L Ch R = 1,16433,413,413,413
BEGIN DESCRIPTION:
Potter Creek 31.0
END DESCRIPTION:
XS GIS Cut Line= 3
      2202925.02     13884675.02      2202321.02     13884104.69
      2201925.03     13883975.01
#Sta/Elev= 30
  4174.4  973.53  4230.9  967.22  4296.1  963.45  4301.6  962.96  4393.9  953.78
  4414.9  953.41  4514.1  947.24  4591.7  945.21  4768.5  933.88  4811.0  932.88
  4917.1  934.41  4973.6  932.41  4980.9  928.72  4987.8  930.41  4988.1  927.51
  4988.6  927.01  5002.1  927.51  5011.5  927.62  5018.5  929.36  5023.7  928.83
  5032.5  931.70  5074.6  933.47  5137.7  933.63  5310.4  942.97  5342.2  946.37
  5363.0  953.42  5374.1  957.16  5379.7  962.58  5390.3  965.61  5421.8  966.93
#Mann=6,-1,0
  4174.4   0.035       0  4296.1   0.063       0  4301.6    0.12       0
  4988.1    0.05       0  5002.1    0.12       0  5363.0   0.035       0
Bank Sta=4988.1,5002.1
Exp/Cntr=0.3,0.1