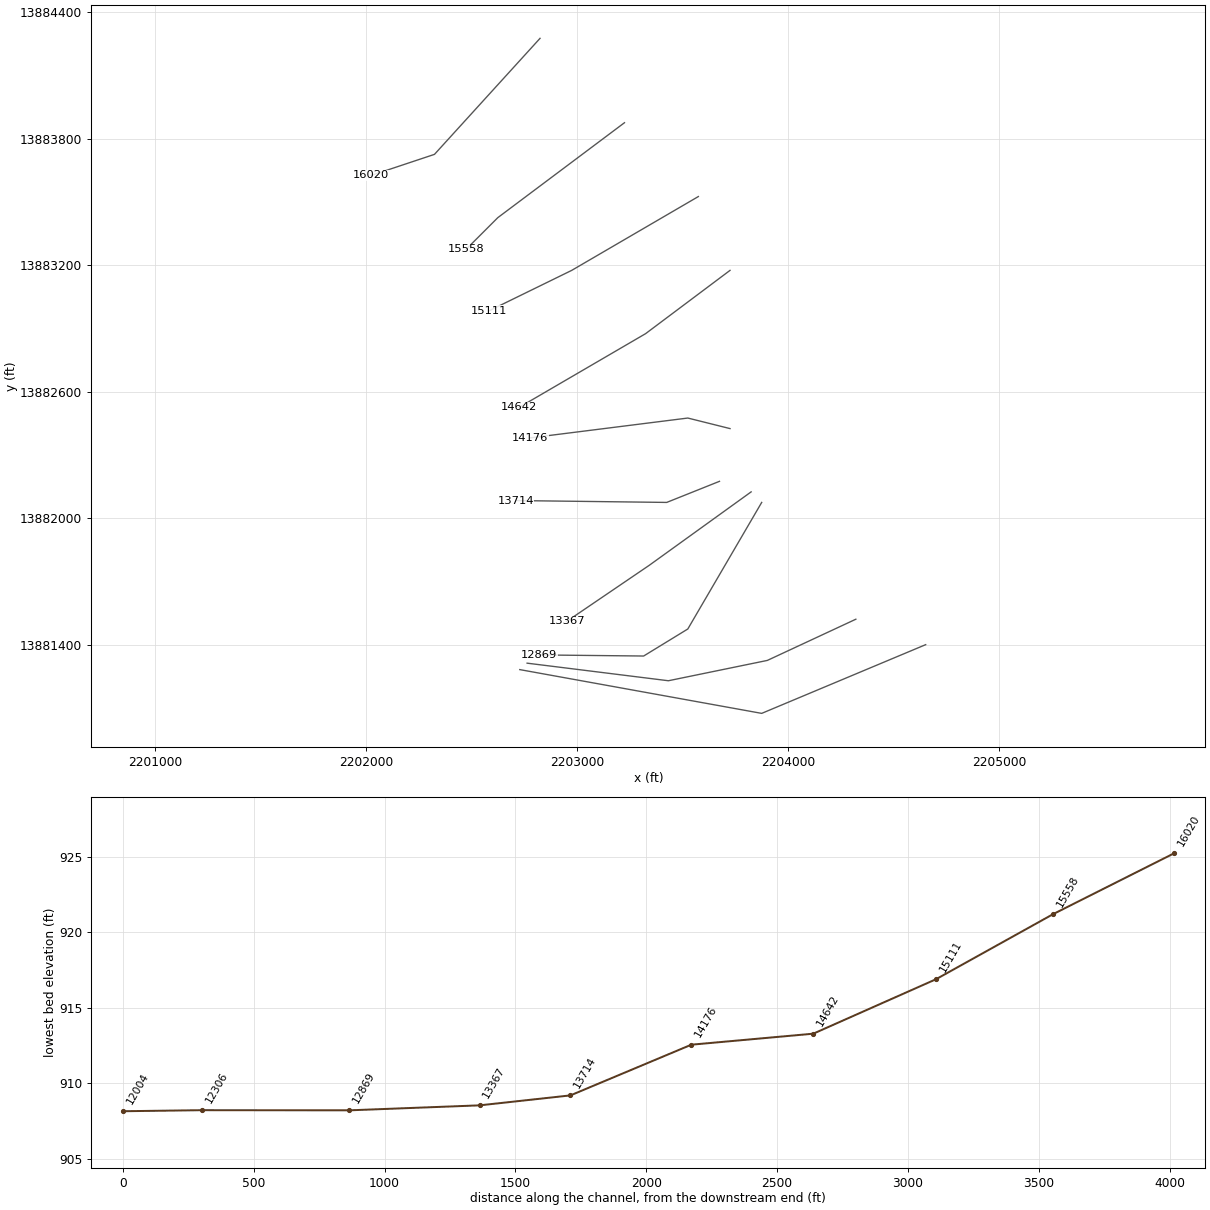
HEC-RAS study Potter Creek.prj: Potter Creek Base Level Engineering

--- Potter Creek.g01 (geometry) --- (continued)

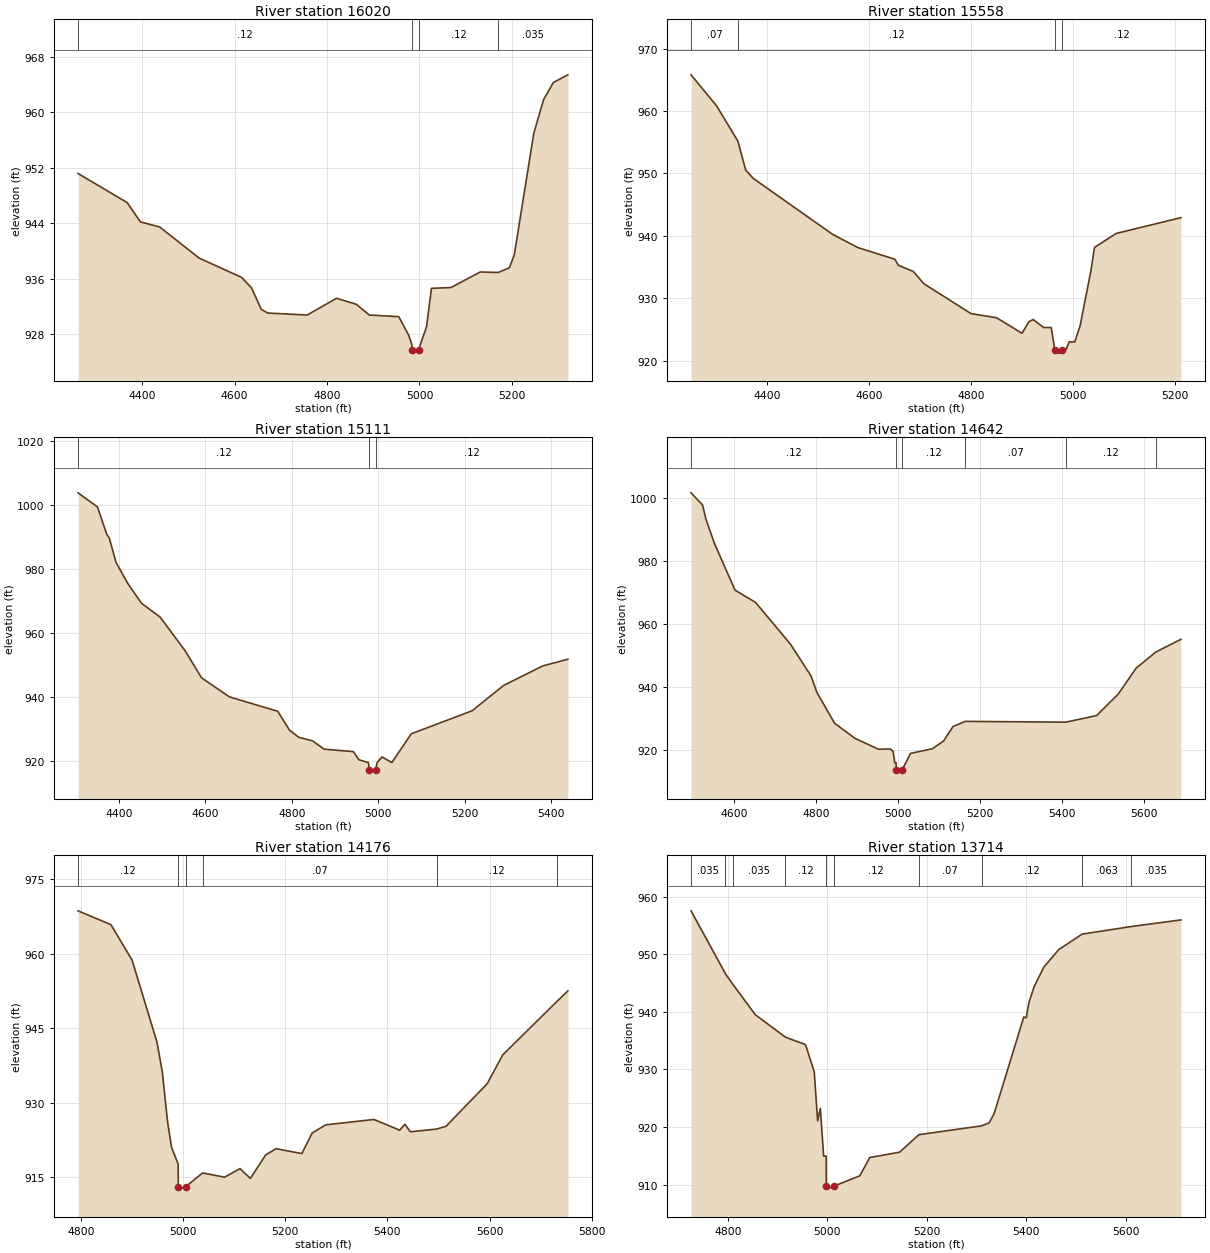
Type RM Length L Ch R = 1,16020,462,462,462
BEGIN DESCRIPTION:
Potter Creek 30.0
END DESCRIPTION:
XS GIS Cut Line= 3
      2202824.98     13884274.98      2202325.00     13883725.00
      2202025.00     13883625.00
#Sta/Elev= 30
  4261.6  951.19  4368.0  946.98  4396.4  944.20  4438.3  943.46  4523.4  938.97
  4615.3  936.18  4636.9  934.66  4657.9  931.56  4672.1  931.03  4757.2  930.74
  4820.7  933.16  4863.3  932.30  4891.7  930.74  4955.2  930.51  4976.8  927.82
  4983.6  926.49  4983.9  925.74  4984.4  925.24  4998.1  925.74  5015.4  929.07
  5026.0  934.60  5068.1  934.71  5131.4  936.96  5170.3  936.89  5194.6  937.58
  5205.1  939.43  5247.3  956.99  5268.4  961.85  5289.5  964.33  5321.1  965.44
#Mann=4,-1,0
  4261.6    0.12       0  4983.9    0.05       0  4998.1    0.12       0
  5170.3   0.035       0
Bank Sta=4983.9,4998.1
Exp/Cntr=0.3,0.1

Type RM Length L Ch R = 1,15558,447,447,447
BEGIN DESCRIPTION:
Potter Creek 29.0
END DESCRIPTION:
XS GIS Cut Line= 3
      2203225.00     13883875.00      2202625.00     13883425.00
      2202475.02     13883275.02
#Sta/Elev= 30
  4250.0  965.81  4300.0  960.86  4342.0  955.20  4357.3  950.56  4371.9  949.23
  4528.1  940.24  4578.1  938.11  4650.0  936.27  4657.3  935.28  4686.5  934.30
  4707.3  932.33  4800.0  927.54  4850.0  926.88  4900.0  924.39  4913.5  926.25
  4921.9  926.59  4942.7  925.31  4957.3  925.31  4964.6  921.71  4965.1  921.21
  4978.6  921.21  4979.1  921.71  4986.5  921.76  4992.7  923.03  5003.5  922.98
  5014.1  925.58  5035.4  934.45  5042.4  938.15  5084.9  940.39  5212.1  942.92
#Mann=4,-1,0
  4250.0    0.07       0  4342.0    0.12       0  4964.6    0.05       0
  4979.1    0.12       0
Bank Sta=4964.6,4979.1
Exp/Cntr=0.3,0.1

Type RM Length L Ch R = 1,15111,469,469,469
BEGIN DESCRIPTION:
Potter Creek 28.0
END DESCRIPTION:
XS GIS Cut Line= 3
      2203574.98     13883524.99      2202975.00     13883175.00
      2202581.45     13882982.30
#Sta/Elev= 30
  4305.4 1003.79  4350.4  999.39  4371.9  990.81  4377.7  989.67  4393.4  982.03
  4421.2  975.32  4452.2  969.31  4495.2  965.00  4553.5  954.39  4591.1  946.02
  4655.6  940.08  4767.2  935.58  4794.5  929.68  4816.0  927.45  4847.4  926.36
  4874.7  923.75  4942.1  922.99  4954.9  920.44  4976.8  919.56  4979.1  917.40
  4979.6  916.90  4993.7  917.40  4997.1  919.62  5008.5  921.34  5031.0  919.57
  5076.0  928.56  5216.6  935.74  5289.7  943.67  5379.7  949.73  5438.2  951.84
#Mann=3,-1,0
  4305.4    0.12       0  4979.1    0.05       0  4993.7    0.12       0
Bank Sta=4979.1,4993.7
Exp/Cntr=0.3,0.1

Type RM Length L Ch R = 1,14642,466,466,466
BEGIN DESCRIPTION:
Potter Creek 27.0
END DESCRIPTION:
XS GIS Cut Line= 3
      2203725.01     13883175.01      2203325.00     13882875.00
      2202725.03     13882525.02
#Sta/Elev= 30
  4495.6 1001.50  4523.7  997.65  4532.1  993.07  4552.9  985.38  4602.9  970.66
  4652.9  966.76  4738.3  953.50  4788.3  943.44  4802.9  938.14  4845.6  928.47
  4895.6  923.68  4952.9  920.23  4982.1  920.30  4988.3  919.53  4992.5  915.94
  4995.6  915.94  4996.2  913.79  4996.7  913.29  5010.8  913.79  5030.8  918.90
  5083.7  920.38  5111.4  922.83  5134.5  927.43  5164.6  929.06  5409.7  928.81
  5484.7  930.92  5537.7  937.77  5580.7  945.89  5628.6  951.01  5690.2  955.07
#Mann=6,-1,0
  4495.6    0.12       0  4996.2    0.05       0  5010.8    0.12       0
  5164.6    0.07       0  5409.7    0.12       0  5628.6   0.035       0
Bank Sta=4996.2,5010.8
Exp/Cntr=0.3,0.1

Type RM Length L Ch R = 1,14176,462,462,462
BEGIN DESCRIPTION:
Potter Creek 26.0
END DESCRIPTION:
XS GIS Cut Line= 3
      2203725.00     13882425.00      2203525.00     13882475.00
      2202778.36     13882380.94
#Sta/Elev= 30
  4794.7  968.64  4859.1  965.85  4900.4  958.73  4949.3  942.15  4959.6  936.19
  4969.9  926.14  4977.7  920.99  4990.6  917.62  4990.9  913.06  4991.4  912.56
  5005.6  913.06  5038.4  915.82  5081.5  914.97  5111.7  916.69  5131.9  914.72
  5162.1  919.47  5182.3  920.71  5232.7  919.72  5252.8  923.86  5279.4  925.51
  5373.8  926.60  5424.2  924.44  5434.3  925.63  5445.1  924.11  5496.7  924.67
  5514.9  925.23  5595.5  933.81  5625.8  939.61  5731.1  950.30  5753.4  952.52
#Mann=6,-1,0
  4794.7    0.12       0  4990.9    0.05       0  5005.6    0.12       0
  5038.4    0.07       0  5496.7    0.12       0  5731.1   0.035       0
Bank Sta=4990.9,5005.6
Exp/Cntr=0.3,0.1

Type RM Length L Ch R = 1,13714,347,347,347
BEGIN DESCRIPTION:
Potter Creek 25.0
END DESCRIPTION:
XS GIS Cut Line= 3
      2203675.03     13882175.01      2203425.00     13882075.00
      2202709.54     13882083.85
#Sta/Elev= 30
  4726.2  957.55  4795.4  946.62  4811.2  944.68  4855.5  939.49  4916.0  935.60
  4956.4  934.31  4973.9  929.57  4980.7  921.06  4986.1  923.24  4992.8  914.93
  4998.0  914.93  4998.1  909.70  4998.6  909.20  5012.9  909.70  5065.5  911.52
  5085.5  914.69  5145.5  915.62  5184.3  918.66  5310.2  920.19  5325.5  920.71
  5335.5  922.32  5395.1  939.09  5400.1  938.97  5405.5  941.62  5415.5  944.28
  5435.5  947.78  5465.5  950.82  5512.4  953.50  5611.0  954.82  5711.0  955.97
#Mann=10,-1,0
  4726.2   0.035       0  4795.4    0.12       0  4811.2   0.035       0
  4916.0    0.12       0  4998.1    0.05       0  5012.9    0.12       0
  5184.3    0.07       0  5310.2    0.12       0  5512.4   0.063       0
  5611.0   0.035       0
Bank Sta=4998.1,5012.9
Exp/Cntr=0.3,0.1

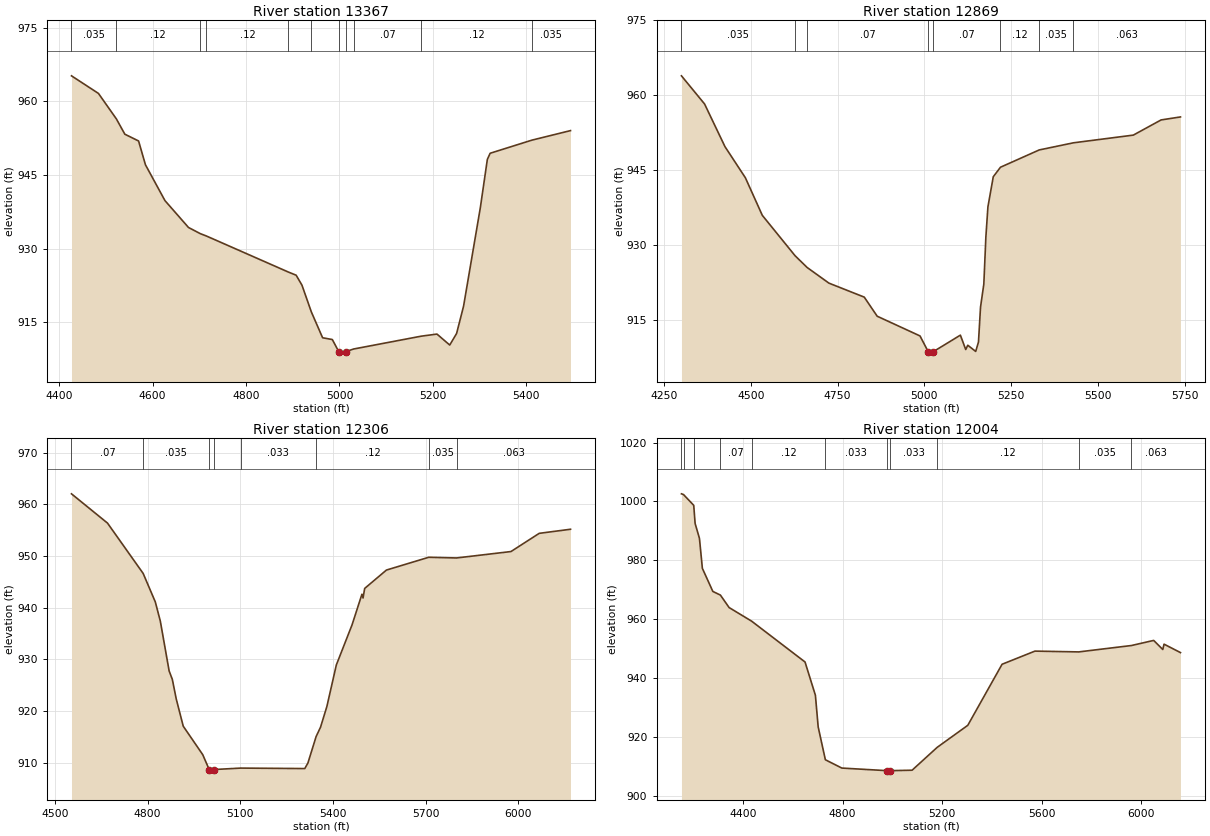
Type RM Length L Ch R = 1,13367,498,498,498
BEGIN DESCRIPTION:
Potter Creek 24.0
END DESCRIPTION:
XS GIS Cut Line= 3
      2203825.03     13882125.02      2203341.85     13881776.57
      2202951.23     13881510.94
#Sta/Elev= 30
  4426.4  965.18  4484.1  961.60  4522.5  956.41  4540.6  953.30  4570.0  951.92
  4584.7  947.08  4626.5  939.78  4676.8  934.32  4701.9  933.07  4715.2  932.58
  4890.7  925.24  4907.3  924.60  4919.7  922.58  4939.8  917.13  4963.9  911.87
  4984.7  911.51  4998.5  909.04  4999.0  908.54  5013.3  909.04  5030.2  909.58
  5174.8  912.19  5208.7  912.62  5236.0  910.39  5250.7  912.74  5265.6  918.29
  5301.5  938.33  5316.5  948.16  5322.5  949.42  5411.9  952.09  5494.5  954.03
#Mann=11,-1,0
  4426.4   0.035       0  4522.5    0.12       0  4701.9   0.035       0
  4715.2    0.12       0  4890.7    0.07       0  4939.8    0.12       0
  4998.5    0.05       0  5013.3    0.12       0  5030.2    0.07       0
  5174.8    0.12       0  5411.9   0.035       0
Bank Sta=4998.5,5013.3
Exp/Cntr=0.3,0.1

Type RM Length L Ch R = 1,12869,563,563,563
BEGIN DESCRIPTION:
Potter Creek 23.0
END DESCRIPTION:
XS GIS Cut Line= 4
      2203875.00     13882074.99      2203525.00     13881475.00
      2203315.81     13881346.88      2202819.16     13881352.08
#Sta/Elev= 30
  4300.5  963.92  4367.1  958.28  4425.8  949.74  4484.5  943.52  4533.3  935.99
  4627.7  927.90  4662.4  925.55  4725.1  922.42  4826.8  919.62  4864.0  915.80
  4987.3  911.85  5010.8  908.71  5011.3  908.21  5025.7  908.71  5103.5  912.01
  5118.9  909.13  5124.8  909.99  5147.6  908.75  5155.6  910.63  5161.5  917.62
  5171.0  922.24  5176.9  931.68  5182.8  937.70  5198.2  943.72  5218.9  945.62
  5330.3  949.08  5428.9  950.51  5601.3  952.05  5681.3  955.09  5737.1  955.69
#Mann=8,-1,0
  4300.5   0.035       0  4627.7    0.12       0  4662.4    0.07       0
  5010.8    0.05       0  5025.7    0.07       0  5218.9    0.12       0
  5330.3   0.035       0  5428.9   0.063       0
Bank Sta=5010.8,5025.7
Exp/Cntr=0.3,0.1

Type RM Length L Ch R = 1,12306,302,302,302
BEGIN DESCRIPTION:
Potter Creek 22.0
END DESCRIPTION:
XS GIS Cut Line= 4
      2204321.04     13881521.37      2203901.75     13881326.04
      2203433.00     13881229.69      2202763.77     13881313.02
#Sta/Elev= 30
  4553.7  962.03  4670.3  956.37  4785.8  946.63  4825.1  941.12  4841.4  937.39
  4869.8  927.79  4880.3  926.13  4892.7  922.40  4915.5  917.10  4978.6  911.60
  4999.5  908.72  5000.0  908.22  5014.5  908.72  5101.3  909.00  5309.0  908.91
  5319.2  910.00  5345.6  915.09  5360.0  916.92  5380.5  920.91  5411.1  928.94
  5462.1  936.71  5494.0  942.62  5497.6  941.89  5502.9  943.74  5573.3  947.29
  5710.2  949.76  5800.3  949.63  5976.5  950.87  6068.0  954.39  6169.2  955.18
#Mann=8,-1,0
  4553.7    0.07       0  4785.8   0.035       0  4999.5   0.035       0
  5014.5   0.035       0  5101.3   0.033       0  5345.6    0.12       0
  5710.2   0.035       0  5800.3   0.063       0
Bank Sta=4999.5,5014.5
Exp/Cntr=0.3,0.1

Type RM Length L Ch R = 1,12004,0,0,0
BEGIN DESCRIPTION:
Potter Creek 21.0
END DESCRIPTION:
XS GIS Cut Line= 3
      2204651.78     13881400.71      2203875.00     13881075.00
      2202729.04     13881282.48
#Sta/Elev= 30
  4151.8 1002.60  4160.1 1002.35  4201.2  998.69  4202.9  996.80  4206.7  992.56
  4224.2  987.47  4235.9  977.31  4278.0  969.48  4308.5  968.23  4343.5  964.00
  4434.1  959.38  4648.8  945.53  4690.5  934.24  4701.7  923.48  4730.6  912.35
  4796.8  909.53  4977.4  908.65  4977.9  908.15  4992.4  908.65  5079.4  908.80
  5180.3  916.56  5303.4  924.04  5441.3  944.76  5573.4  949.22  5749.6  948.95
  5961.7  951.12  6051.0  952.85  6087.6  949.77  6092.7  951.58  6158.7  948.72
#Mann=11,-1,0
  4151.8   0.035       0  4160.1    0.07       0  4202.9    0.12       0
  4308.5    0.07       0  4434.1    0.12       0  4730.6   0.033       0
  4977.4   0.033       0  4992.4   0.033       0  5180.3    0.12       0
  5749.6   0.035       0  5961.7   0.063       0
Bank Sta=4977.4,4992.4
Exp/Cntr=0.3,0.1

Chan Stop Cuts=-1