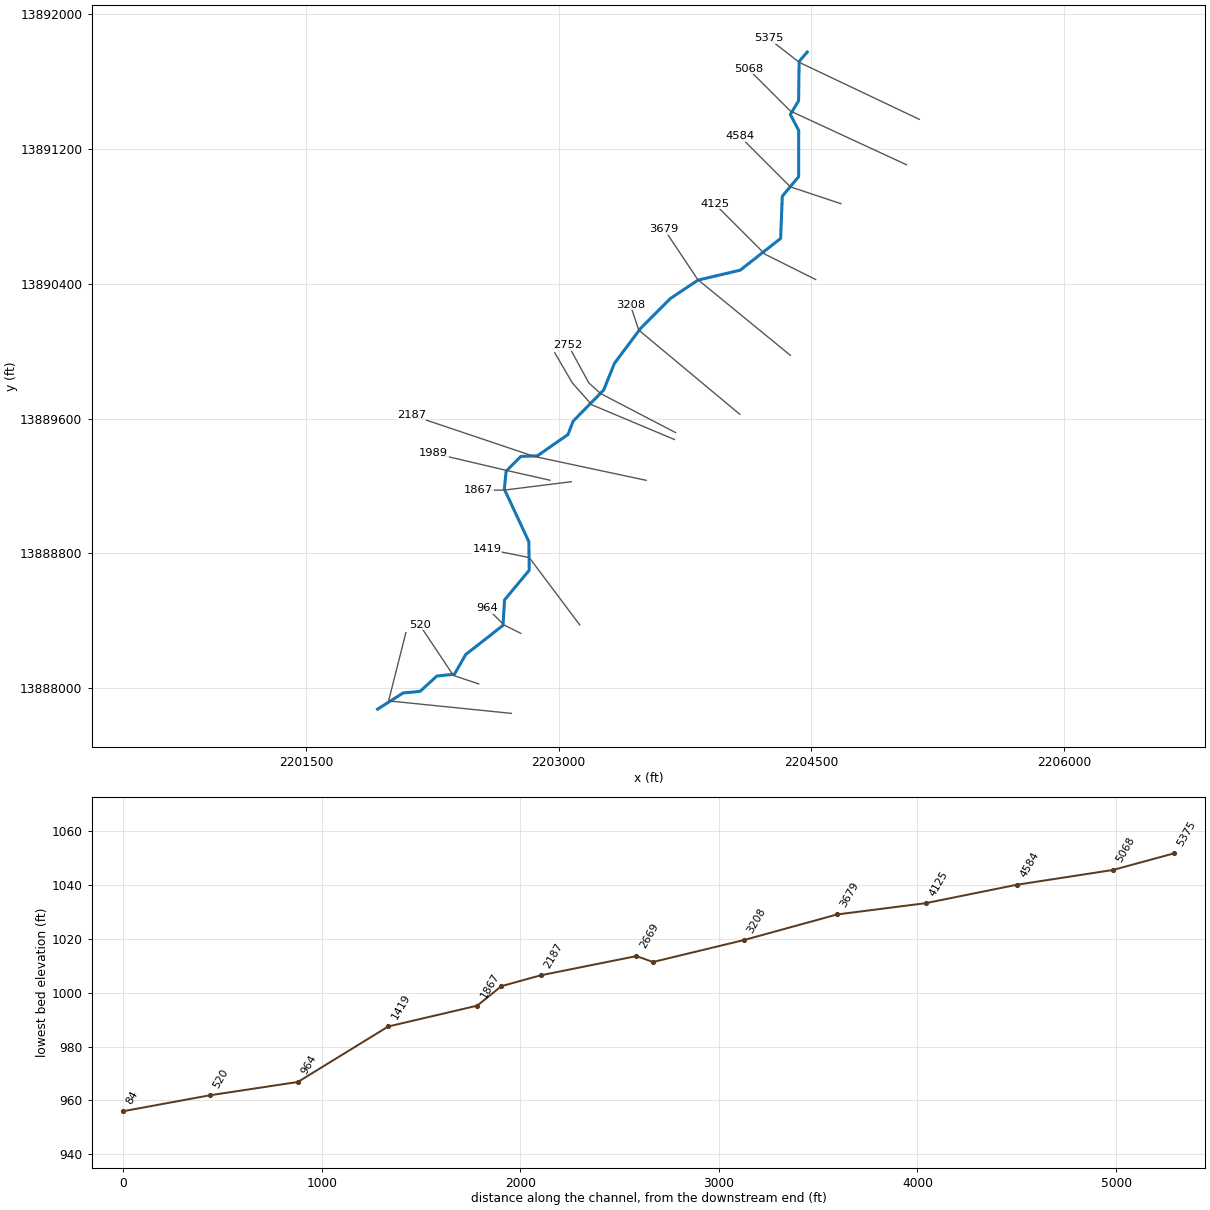
--- Potter Tributary 1.prj (project) ---

Proj Title=Potter Tributary 1 Base Level Engineering
Current Plan=p01
Default Exp/Contr=0.3,0.1
English Units
Geom File=g01
Flow File=f01
Plan File=p01
BEGIN DESCRIPTION:
Potter Tributary 1
END DESCRIPTION:

--- Potter Tributary 1.p01 (plan) ---

Plan Title=Multiple Run
Short Identifier=Multiple
Geom File=g01
Flow File=f01
Subcritical Flow
K Sum by GR= 0
Std Step Tol= 0.01
Critical Tol= 0.01
Num of Std Step Trials= 20
Max Error Tol= 0.3
Flow Tol Ratio= 0.001
Split Flow NTrial= 30
Split Flow Tol= 0.02
Split Flow Ratio= 0.02
Log Output Level= 0
Friction Slope Method= 1
Unsteady Friction Slope Method= 2
Unsteady Bridges Friction Slope Method= 1
Parabolic Critical Depth
Global Vel Dist=  1 , 1 , 1
Global Log Level= 0
CheckData=True
Encroach Param= -1, 0, 0, 0
BEGIN DESCRIPTION:
Multiple Run
END DESCRIPTION:

--- Potter Tributary 1.f01 (steady flow) ---

Flow Title=Multiple
Number of Profiles=7
Profile Names=10-year,25-year,50-year,1pct_min,100-year,1pct_plu,500-year
River Rch & RM= Potter Tributary,Reach-1,5375
     854    1425    1962    1311    2616    5219    4593
River Rch & RM= Potter Tributary,Reach-1,5068
    1127    1909    2653    1787    3565    7113    6366
River Rch & RM= Potter Tributary,Reach-1,1989
    1833    3194    4525    3103    6191   12352   11465
Boundary for River Rch & Prof#=Potter Tributary,Reach-1,1
Up Type=0
Dn Type=3
Dn Slope=0.005
Boundary for River Rch & Prof#=Potter Tributary,Reach-1,2
Up Type=0
Dn Type=3
Dn Slope=0.005
Boundary for River Rch & Prof#=Potter Tributary,Reach-1,3
Up Type=0
Dn Type=3
Dn Slope=0.005
Boundary for River Rch & Prof#=Potter Tributary,Reach-1,4
Up Type=0
Dn Type=3
Dn Slope=0.005
Boundary for River Rch & Prof#=Potter Tributary,Reach-1,5
Up Type=0
Dn Type=3
Dn Slope=0.005
Boundary for River Rch & Prof#=Potter Tributary,Reach-1,6
Up Type=0
Dn Type=3
Dn Slope=0.005
Boundary for River Rch & Prof#=Potter Tributary,Reach-1,7
Up Type=0
Dn Type=3
Dn Slope=0.005

--- Potter Tributary 1.g01 (geometry) ---

Geom Title=Existing Conditions

River Reach=Potter Tributary,Reach-1
Reach XY= 30
      2204475.00     13891775.00      2204426.89     13891719.22
      2204423.76     13891485.50      2204374.72     13891404.82
      2204424.46     13891309.79      2204423.94     13891035.44
      2204327.07     13890919.14      2204317.20     13890668.79
      2204077.42     13890480.54      2203826.50     13890421.38
      2203661.79     13890311.37      2203485.78     13890134.68
      2203330.83     13889927.30      2203266.86     13889768.94
      2203085.78     13889584.68      2203055.23     13889504.87
      2202873.50     13889378.63      2202775.00     13889375.00
      2202688.24     13889288.34      2202677.16     13889180.98
      2202822.76     13888869.07      2202825.30     13888699.88
      2202678.54     13888523.53      2202669.53     13888372.55
      2202447.86     13888198.83      2202381.45     13888082.75
      2202276.50     13888071.37      2202177.42     13887980.54
      2202076.58     13887971.18      2201925.00     13887875.00

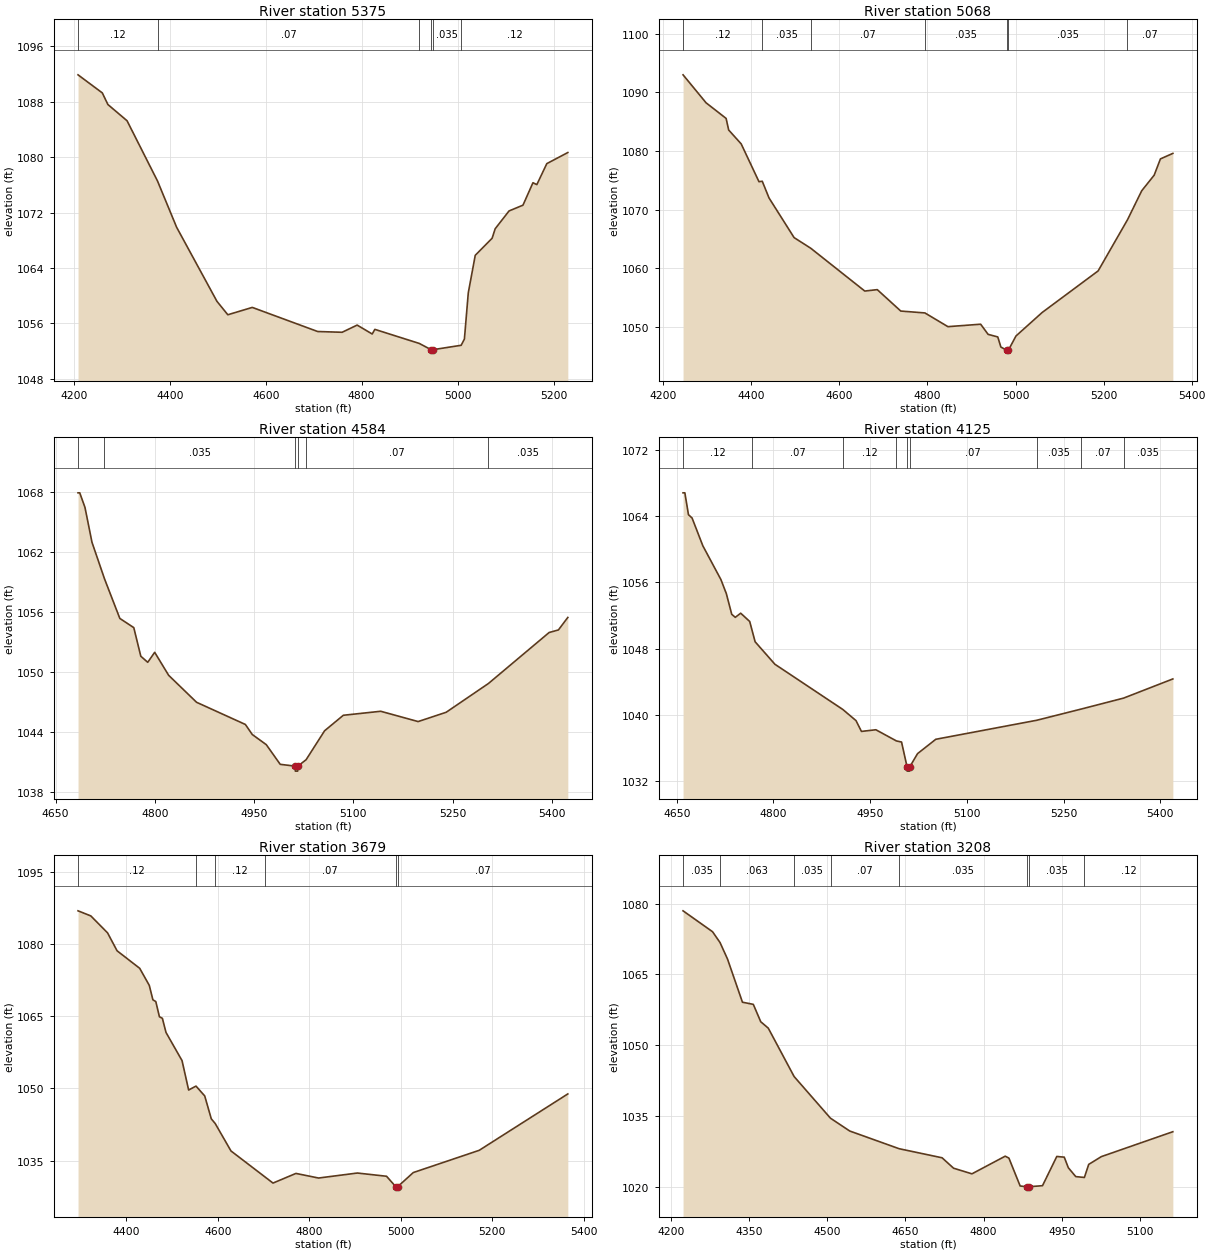
Type RM Length L Ch R = 1,5375,307,307,307
BEGIN DESCRIPTION:
Potter Tributary 1 12.0
END DESCRIPTION:
XS GIS Cut Line= 3
      2205140.68     13891375.40      2204427.67     13891713.88
      2204244.87     13891856.46
#Sta/Elev= 30
  4208.7 1091.89  4259.3 1089.28  4271.0 1087.60  4310.9 1085.26  4374.4 1076.56
  4414.2 1069.89  4498.3 1059.19  4521.0 1057.25  4572.0 1058.31  4708.3 1054.83
  4759.3 1054.72  4790.6 1055.76  4822.0 1054.47  4827.5 1055.14  4920.1 1053.11
  4944.7 1052.21  4945.0 1051.71  4948.7 1052.21  5007.4 1052.84  5014.2 1053.74
  5022.3 1060.42  5036.8 1065.83  5072.0 1068.30  5078.4 1069.67  5107.3 1072.24
  5136.3 1073.07  5157.1 1076.31  5165.2 1076.04  5186.0 1079.07  5229.8 1080.67
#Mann=6,-1,0
  4208.7    0.12       0  4374.4    0.07       0  4920.1   0.035       0
  4944.7   0.035       0  4948.7   0.035       0  5007.4    0.12       0
Bank Sta=4944.7,4948.7
Exp/Cntr=0.3,0.1

Type RM Length L Ch R = 1,5068,484,484,484
BEGIN DESCRIPTION:
Potter Tributary 1 11.0
END DESCRIPTION:
XS GIS Cut Line= 3
      2205063.76     13891106.36      2204375.00     13891425.00
      2204125.03     13891674.97
#Sta/Elev= 30
  4244.9 1092.99  4297.2 1088.22  4342.7 1085.56  4348.5 1083.59  4377.0 1081.21
  4417.3 1074.78  4424.8 1074.85  4440.2 1072.00  4497.1 1065.25  4535.0 1063.43
  4657.6 1056.14  4686.0 1056.38  4739.4 1052.73  4794.2 1052.41  4846.5 1050.07
  4920.8 1050.49  4937.7 1048.76  4959.7 1048.32  4966.7 1046.60  4979.8 1046.06
  4980.0 1045.56  4983.8 1046.06  5001.0 1048.48  5060.4 1052.48  5187.6 1059.57
  5254.3 1068.29  5286.6 1073.23  5314.9 1075.89  5329.1 1078.66  5357.3 1079.60
#Mann=7,-1,0
  4244.9    0.12       0  4424.8   0.035       0  4535.0    0.07       0
  4794.2   0.035       0  4979.8   0.035       0  4983.8   0.035       0
  5254.3    0.07       0
Bank Sta=4979.8,4983.8
Exp/Cntr=0.3,0.1

Type RM Length L Ch R = 1,4584,459,459,459
BEGIN DESCRIPTION:
Potter Tributary 1 10.0
END DESCRIPTION:
XS GIS Cut Line= 3
      2204674.99     13890875.00      2204375.00     13890975.00
      2204074.99     13891275.01
#Sta/Elev= 30
  4683.8 1067.92  4686.4 1067.92  4694.3 1066.46  4704.9 1062.97  4723.8 1059.32
  4747.0 1055.35  4768.1 1054.43  4778.7 1051.57  4789.2 1050.96  4799.7 1051.96
  4820.8 1049.66  4863.0 1046.96  4936.8 1044.74  4947.3 1043.73  4968.4 1042.72
  4989.5 1040.75  5012.2 1040.57  5012.4 1040.07  5015.9 1040.07  5016.2 1040.57
  5028.6 1041.21  5056.6 1044.11  5084.9 1045.66  5141.4 1046.06  5198.0 1045.03
  5240.4 1045.96  5304.3 1048.84  5396.0 1053.94  5410.1 1054.20  5424.3 1055.45
#Mann=6,-1,0
  4683.8    0.12       0  4723.8   0.035       0  5012.2   0.035       0
  5016.2   0.035       0  5028.6    0.07       0  5304.3   0.035       0
Bank Sta=5012.2,5016.2
Exp/Cntr=0.3,0.1

Type RM Length L Ch R = 1,4125,446,446,446
BEGIN DESCRIPTION:
Potter Tributary 1 9.0
END DESCRIPTION:
XS GIS Cut Line= 3
      2204524.99     13890425.00      2204225.00     13890575.00
      2203924.97     13890875.03
#Sta/Elev= 30
  4659.8 1066.80  4662.6 1066.80  4668.2 1064.16  4673.8 1063.76  4690.5 1060.41
  4718.5 1056.34  4726.9 1054.65  4735.3 1052.15  4740.8 1051.78  4749.2 1052.28
  4763.2 1051.28  4767.1 1050.14  4771.6 1048.83  4802.3 1046.12  4907.4 1040.68
  4928.1 1039.32  4936.5 1038.02  4958.9 1038.22  4990.8 1036.87  4998.7 1036.74
  5007.3 1033.73  5007.6 1033.23  5011.1 1033.23  5011.3 1033.73  5023.5 1035.34
  5051.8 1037.07  5208.1 1039.36  5277.0 1040.71  5343.2 1042.04  5419.5 1044.35
#Mann=9,-1,0
  4659.8    0.12       0  4767.1    0.07       0  4907.4    0.12       0
  4990.8    0.07       0  5007.3    0.05       0  5011.3    0.07       0
  5208.1   0.035       0  5277.0    0.07       0  5343.2   0.035       0
Bank Sta=5007.3,5011.3
Exp/Cntr=0.3,0.1

Type RM Length L Ch R = 1,3679,471,471,471
BEGIN DESCRIPTION:
Potter Tributary 1 8.0
END DESCRIPTION:
XS GIS Cut Line= 3
      2204374.99     13889975.00      2203825.00     13890425.00
      2203624.99     13890725.02
#Sta/Elev= 30
  4294.0 1086.98  4322.0 1085.92  4358.6 1082.39  4379.4 1078.66  4428.9 1075.01
  4449.8 1071.47  4457.7 1068.46  4464.1 1068.09  4472.0 1064.93  4478.5 1064.60
  4486.4 1061.66  4521.5 1055.79  4535.9 1049.67  4552.0 1050.49  4571.1 1048.44
  4585.4 1043.69  4594.2 1042.67  4628.5 1036.99  4701.9 1031.65  4720.4 1030.30
  4770.6 1032.31  4820.1 1031.35  4904.9 1032.39  4968.7 1031.72  4989.0 1029.54
  4989.2 1029.04  4993.0 1029.54  5027.2 1032.49  5171.4 1037.12  5365.2 1048.86
#Mann=6,-1,0
  4294.0    0.12       0  4552.0   0.035       0  4594.2    0.12       0
  4701.9    0.07       0  4989.0    0.05       0  4993.0    0.07       0
Bank Sta=4989,4993
Exp/Cntr=0.3,0.1

Type RM Length L Ch R = 1,3208,456,456,456
BEGIN DESCRIPTION:
Potter Tributary 1 7.0
END DESCRIPTION:
XS GIS Cut Line= 3
      2204074.99     13889625.00      2203475.00     13890125.00
      2203425.01     13890274.97
#Sta/Elev= 30
  4223.6 1078.45  4280.2 1074.02  4294.5 1071.73  4308.9 1068.22  4337.5 1059.09
  4358.3 1058.64  4372.6 1054.95  4387.0 1053.60  4436.6 1043.34  4506.3 1034.52
  4543.2 1031.81  4637.9 1028.06  4720.2 1026.14  4742.3 1023.93  4777.5 1022.74
  4841.3 1026.48  4848.4 1026.07  4869.9 1020.17  4882.2 1020.00  4882.5 1019.50
  4886.2 1020.00  4912.8 1020.23  4940.2 1026.42  4954.5 1026.27  4962.3 1024.03
  4976.6 1022.15  4993.1 1021.97  5001.4 1024.74  5025.7 1026.39  5162.7 1031.66
#Mann=8,-1,0
  4223.6   0.035       0  4294.5   0.063       0  4436.6   0.035       0
  4506.3    0.07       0  4637.9   0.035       0  4882.2    0.05       0
  4886.2   0.035       0  4993.1    0.12       0
Bank Sta=4882.2,4886.2
Exp/Cntr=0.3,0.1

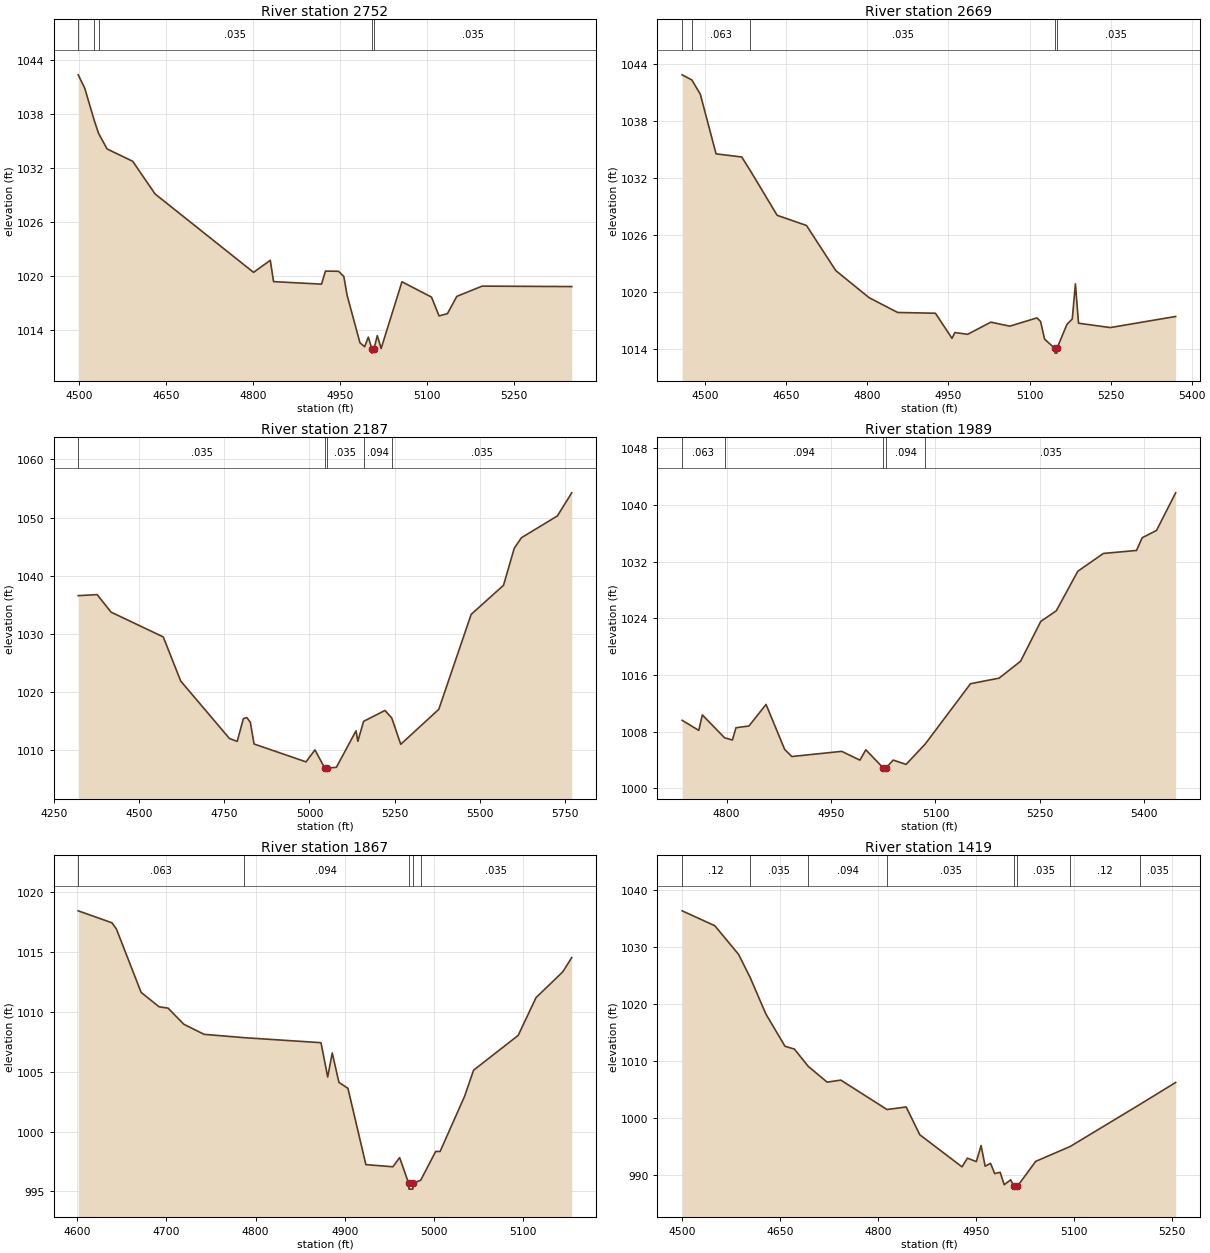
Type RM Length L Ch R = 1,2752,83,83,83
BEGIN DESCRIPTION:
Potter Tributary 1 6.0
END DESCRIPTION:
XS GIS Cut Line= 4
      2203693.40     13889516.55      2203248.71     13889748.18
      2203178.61     13889811.36      2203056.36     13890036.21
#Sta/Elev= 30
  4498.6 1042.33  4509.9 1040.84  4526.0 1037.32  4533.7 1035.83  4548.4 1034.09
  4592.6 1032.72  4631.2 1029.09  4801.2 1020.37  4830.1 1021.71  4835.7 1019.34
  4918.5 1019.06  4925.3 1020.51  4947.8 1020.49  4957.0 1019.91  4962.7 1017.81
  4984.8 1012.55  4992.9 1012.10  4999.3 1013.17  5005.2 1011.89  5005.5 1011.39
  5009.2 1011.89  5014.7 1013.34  5021.4 1011.91  5057.3 1019.32  5108.3 1017.62
  5121.3 1015.53  5135.8 1015.78  5152.0 1017.70  5195.7 1018.84  5350.3 1018.79
#Mann=5,-1,0
  4498.6   0.035       0  4526.0   0.063       0  4533.7   0.035       0
  5005.2   0.035       0  5009.2   0.035       0
Bank Sta=5005.2,5009.2
Exp/Cntr=0.3,0.1

Type RM Length L Ch R = 1,2669,482,482,482
BEGIN DESCRIPTION:
Potter Tributary 1 5.5
END DESCRIPTION:
XS GIS Cut Line= 4
      2203687.11     13889475.33      2203196.47     13889681.40
      2203081.09     13889810.96      2202976.46     13889990.21
#Sta/Elev= 30
  4457.2 1042.89  4475.2 1042.35  4490.8 1040.85  4520.0 1034.57  4567.5 1034.24
  4583.5 1032.79  4633.0 1028.10  4687.3 1027.03  4741.5 1022.28  4803.1 1019.43
  4856.0 1017.87  4925.9 1017.79  4956.5 1015.15  4961.9 1015.76  4985.5 1015.57
  5028.4 1016.85  5063.5 1016.43  5113.7 1017.30  5120.4 1016.93  5127.9 1015.06
  5146.8 1014.09  5147.1 1013.59  5150.6 1013.59  5150.8 1014.09  5169.2 1016.61
  5179.1 1017.19  5184.9 1020.88  5190.7 1016.74  5249.4 1016.28  5370.4 1017.45
#Mann=5,-1,0
  4457.2   0.035       0  4475.2   0.063       0  4583.5   0.035       0
  5146.8   0.035       0  5150.8   0.035       0
Bank Sta=5146.8,5150.8
Exp/Cntr=0.3,0.1

Type RM Length L Ch R = 1,2187,198,198,198
BEGIN DESCRIPTION:
Potter Tributary 1 5.0
END DESCRIPTION:
XS GIS Cut Line= 3
      2203519.35     13889233.18      2202855.08     13889374.80
      2202125.04     13889620.56
#Sta/Elev= 30
  4320.8 1036.59  4376.4 1036.77  4417.3 1033.76  4570.6 1029.50  4621.8 1021.93
  4764.9 1012.06  4787.8 1011.56  4805.8 1015.46  4816.0 1015.65  4826.3 1014.85
  4837.3 1011.11  4989.9 1008.04  5016.1 1010.10  5045.1 1006.95  5045.4 1006.45
  5050.1 1006.95  5079.1 1007.11  5136.8 1013.37  5142.1 1011.58  5159.0 1015.00
  5221.7 1016.87  5241.7 1015.58  5268.1 1011.06  5379.9 1017.07  5474.9 1033.37
  5569.9 1038.37  5601.5 1044.73  5622.6 1046.54  5728.1 1050.28  5770.3 1054.25
#Mann=5,-1,0
  4320.8   0.035       0  5045.1   0.035       0  5050.1   0.035       0
  5159.0   0.094       0  5241.7   0.035       0
Bank Sta=5045.1,5050.1
Exp/Cntr=0.3,0.1

Type RM Length L Ch R = 1,1989,122,122,122
BEGIN DESCRIPTION:
Potter Tributary 1 4.5
END DESCRIPTION:
XS GIS Cut Line= 3
      2202948.62     13889233.69      2202691.30     13889291.80
      2202258.18     13889393.52
#Sta/Elev= 30
  4736.2 1009.60  4760.1 1008.18  4765.2 1010.36  4797.2 1007.13  4808.4 1006.82
  4813.5 1008.55  4832.2 1008.80  4856.7 1011.84  4883.4 1005.50  4893.7 1004.49
  4965.4 1005.22  4991.5 1003.98  5000.0 1005.44  5024.5 1002.93  5024.9 1002.43
  5029.5 1002.93  5039.2 1003.99  5057.8 1003.38  5085.4 1006.27  5150.3 1014.76
  5191.4 1015.55  5222.2 1017.93  5251.2 1023.55  5273.5 1025.05  5304.4 1030.63
  5341.2 1033.14  5388.7 1033.56  5396.8 1035.35  5417.4 1036.38  5444.9 1041.69
#Mann=5,-1,0
  4736.2   0.063       0  4797.2   0.094       0  5024.5    0.05       0
  5029.5   0.094       0  5085.4   0.035       0
Bank Sta=5024.5,5029.5
Exp/Cntr=0.3,0.1

Type RM Length L Ch R = 1,1867,448,448,448
BEGIN DESCRIPTION:
Potter Tributary 1 4.0
END DESCRIPTION:
XS GIS Cut Line= 3
      2203074.96     13889224.99      2202675.00     13889175.00
      2202524.97     13889175.00
#Sta/Elev= 30
  4601.2 1018.46  4639.0 1017.46  4644.0 1016.94  4671.7 1011.64  4691.9 1010.43
  4701.9 1010.32  4719.6 1008.97  4742.2 1008.13  4787.1 1007.85  4873.3 1007.43
  4880.8 1004.56  4885.9 1006.57  4893.4 1004.11  4903.5 1003.61  4923.6  997.23
  4953.9  997.05  4961.4  997.82  4971.5  995.68  4971.9  995.18  4976.2  995.18
  4976.5  995.68  4985.0  995.92  5001.8  998.33  5006.8  998.33  5034.3 1002.96
  5044.3 1005.13  5094.3 1008.04  5114.3 1011.20  5144.3 1013.36  5154.3 1014.55
#Mann=5,-1,0
  4601.2   0.063       0  4787.1   0.094       0  4971.5   0.035       0
  4976.5   0.094       0  4985.0   0.035       0
Bank Sta=4971.5,4976.5
Exp/Cntr=0.3,0.1

Type RM Length L Ch R = 1,1419,455,455,455
BEGIN DESCRIPTION:
Potter Tributary 1 3.0
END DESCRIPTION:
XS GIS Cut Line= 3
      2203124.98     13888375.03      2202825.00     13888775.00
      2202575.01     13888825.00
#Sta/Elev= 30
  4500.3 1036.41  4550.3 1033.79  4586.7 1028.74  4604.2 1024.72  4628.4 1018.26
  4657.6 1012.59  4672.1 1012.08  4693.0 1009.07  4722.1 1006.27  4743.0 1006.63
  4813.6 1001.46  4843.0 1001.90  4863.8  997.02  4928.4  991.37  4936.7  992.90
  4950.3  992.29  4957.6  995.12  4963.8  991.48  4972.1  991.98  4978.4  990.18
  4986.7  990.42  4993.0  988.22  5002.8  989.09  5007.8  987.95  5008.2  987.45
  5013.1  987.95  5041.1  992.33  5094.0  994.96  5199.9 1002.31  5255.2 1006.22
#Mann=8,-1,0
  4500.3    0.12       0  4604.2   0.035       0  4693.0   0.094       0
  4813.6   0.035       0  5007.8   0.035       0  5013.1   0.035       0
  5094.0    0.12       0  5199.9   0.035       0
Bank Sta=5007.8,5013.1
Exp/Cntr=0.3,0.1

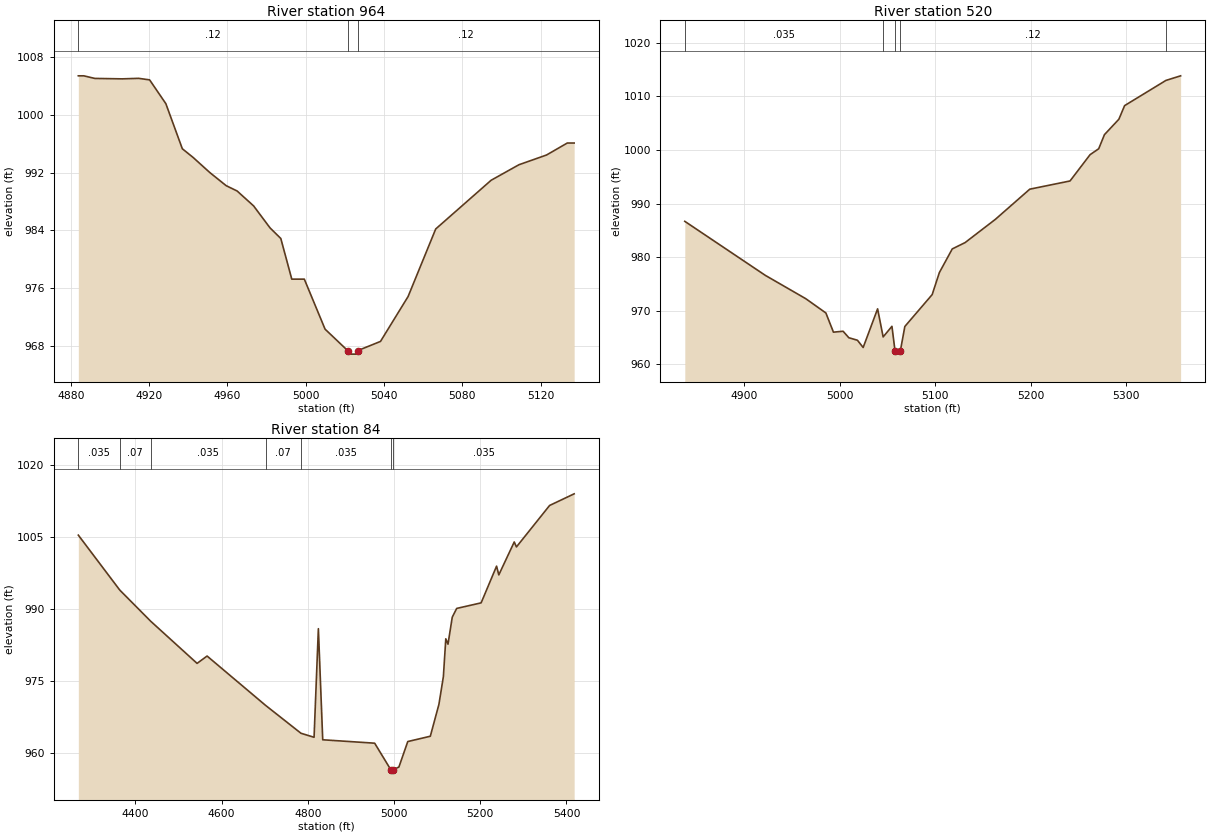
Type RM Length L Ch R = 1,964,444,444,444
BEGIN DESCRIPTION:
Potter Tributary 1 2.0
END DESCRIPTION:
XS GIS Cut Line= 3
      2202775.02     13888324.99      2202675.00     13888375.00
      2202575.04     13888474.96
#Sta/Elev= 30
  4883.9 1005.41  4886.7 1005.41  4892.3 1005.05  4906.3 1004.99  4914.7 1005.06
  4920.3 1004.85  4928.6 1001.55  4937.0  995.31  4942.6  994.08  4951.0  992.02
  4959.4  990.19  4965.0  989.45  4973.4  987.39  4981.8  984.34  4987.3  982.87
  4992.9  977.24  4999.3  977.24  5009.9  970.31  5021.4  967.35  5021.8  966.85
  5026.3  966.85  5026.7  967.35  5038.2  968.61  5052.3  974.83  5066.4  984.19
  5094.7  990.94  5108.9  993.09  5123.0  994.44  5133.6  996.10  5137.1  996.10
#Mann=3,-1,0
  4883.9    0.12       0  5021.4    0.05       0  5026.7    0.12       0
Bank Sta=5021.4,5026.7
Exp/Cntr=0.3,0.1

Type RM Length L Ch R = 1,520,436,436,436
BEGIN DESCRIPTION:
Potter Tributary 1 1.0
END DESCRIPTION:
XS GIS Cut Line= 3
      2202524.99     13888025.00      2202375.00     13888075.00
      2202174.98     13888375.03
#Sta/Elev= 30
  4838.0  986.68  4922.3  976.59  4964.5  972.25  4985.6  969.58  4993.5  966.00
  5003.6  966.17  5009.6  964.96  5018.6  964.49  5024.6  963.14  5039.7  970.35
  5045.5  965.11  5054.7  967.09  5058.0  962.40  5058.5  961.90  5063.4  962.40
  5068.2  967.06  5096.8  973.01  5104.3  977.11  5117.8  981.53  5131.3  982.72
  5162.9  987.05  5198.9  992.68  5241.0  994.21  5262.0  999.12  5271.0 1000.22
  5277.0 1002.85  5292.1 1005.73  5298.1 1008.27  5341.3 1012.97  5356.7 1013.83
#Mann=5,-1,0
  4838.0   0.035       0  5045.5    0.12       0  5058.0   0.035       0
  5063.4    0.12       0  5341.3   0.035       0
Bank Sta=5058,5063.4
Exp/Cntr=0.3,0.1

Type RM Length L Ch R = 1,84,0,0,0
BEGIN DESCRIPTION:
Potter Tributary 1 0.1
END DESCRIPTION:
XS GIS Cut Line= 3
      2202719.05     13887850.00      2201990.40     13887924.03
      2202093.03     13888329.13
#Sta/Elev= 30
  4267.6 1005.37  4363.7  993.93  4435.4  987.44  4543.1  978.65  4566.3  980.18
  4702.0  969.90  4784.1  964.09  4814.5  963.25  4824.5  985.88  4834.6  962.73
  4955.1  962.02  4992.5  956.49  4992.9  955.99  4997.9  956.49  5011.3  957.05
  5031.9  962.36  5084.2  963.47  5104.2  970.13  5114.5  975.89  5120.1  983.77
  5125.2  982.65  5135.1  988.28  5145.4  990.10  5202.1  991.26  5237.9  998.91
  5243.1  997.09  5278.9 1003.95  5284.0 1002.91  5360.9 1011.55  5417.9 1013.98
#Mann=7,-1,0
  4267.6   0.035       0  4363.7    0.07       0  4435.4   0.035       0
  4702.0    0.07       0  4784.1   0.035       0  4992.5   0.035       0
  4997.9   0.035       0
Bank Sta=4992.5,4997.9
Exp/Cntr=0.3,0.1

Chan Stop Cuts=-1