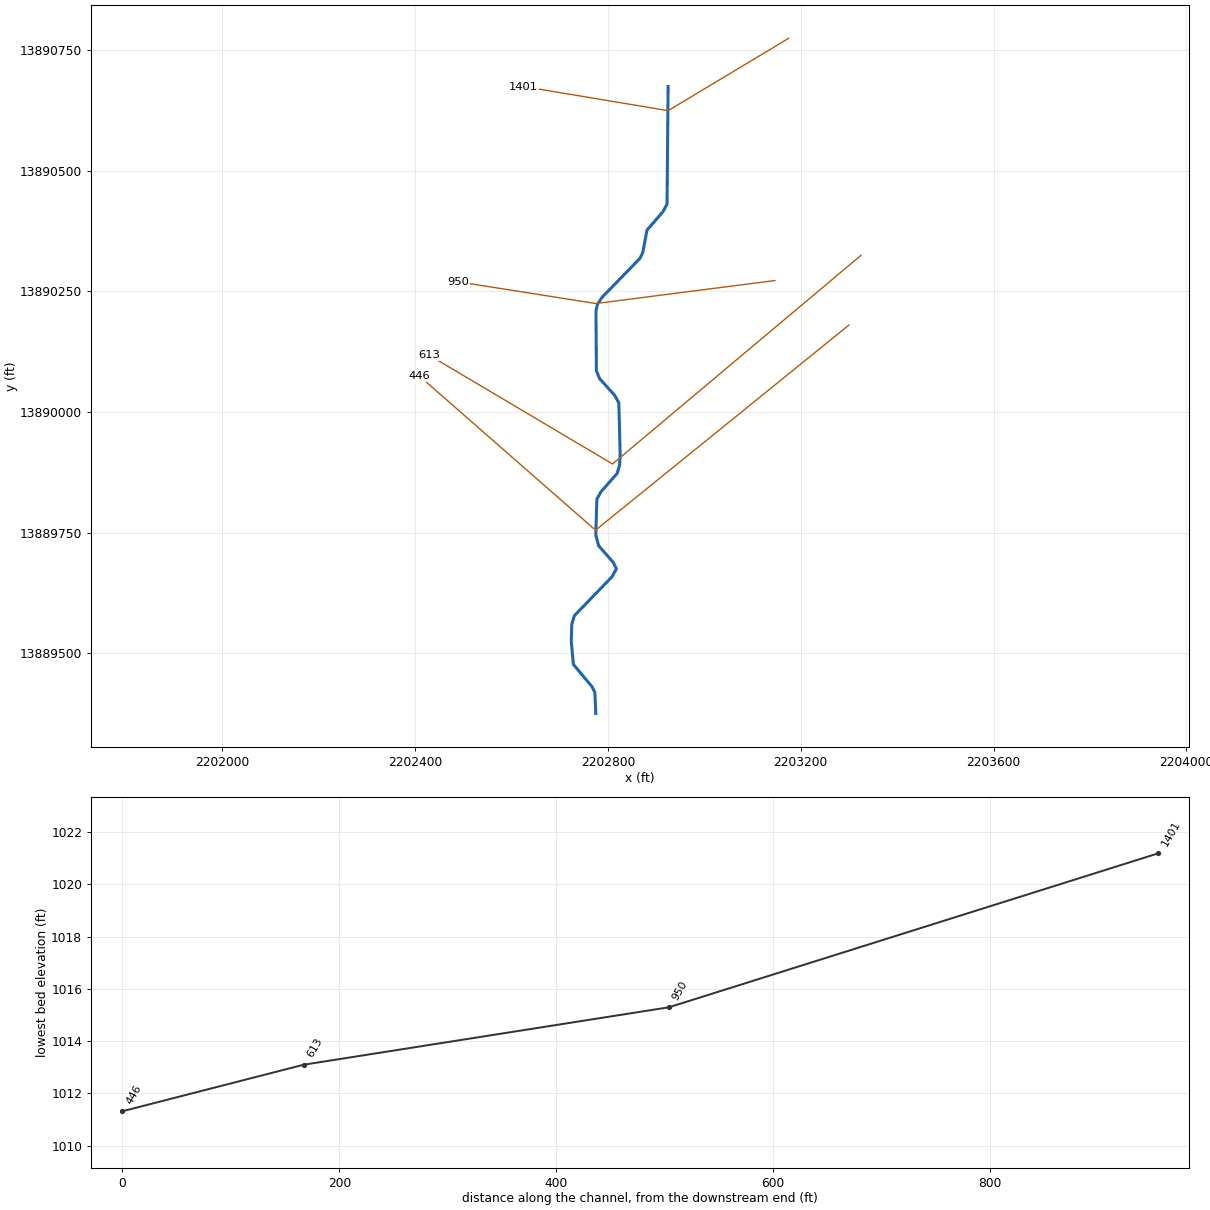
--- Potter Tributary 2.prj (project) ---

Proj Title=Potter Tributary 2 Base Level Engineering
Current Plan=p01
Default Exp/Contr=0.3,0.1
English Units
Geom File=g01
Flow File=f01
Plan File=p01
BEGIN DESCRIPTION:
Potter Tributary 2
END DESCRIPTION:

--- Potter Tributary 2.p01 (plan) ---

Plan Title=Multiple Run
Short Identifier=Multiple
Geom File=g01
Flow File=f01
Subcritical Flow
K Sum by GR= 0
Std Step Tol= 0.01
Critical Tol= 0.01
Num of Std Step Trials= 20
Max Error Tol= 0.3
Flow Tol Ratio= 0.001
Split Flow NTrial= 30
Split Flow Tol= 0.02
Split Flow Ratio= 0.02
Log Output Level= 0
Friction Slope Method= 1
Unsteady Friction Slope Method= 2
Unsteady Bridges Friction Slope Method= 1
Parabolic Critical Depth
Global Vel Dist=  1 , 1 , 1
Global Log Level= 0
CheckData=True
Encroach Param= -1, 0, 0, 0
BEGIN DESCRIPTION:
Multiple Run
END DESCRIPTION:

--- Potter Tributary 2.f01 (steady flow) ---

Flow Title=Multiple
Number of Profiles=7
Profile Names=10-year,25-year,50-year,1pct_min,100-year,1pct_plu,500-year
River Rch & RM= Potter Tributary,Reach-1,1401
     764    1260    1721    1141    2276    4541    3933
Boundary for River Rch & Prof#=Potter Tributary,Reach-1,1
Up Type=0
Dn Type=3
Dn Slope=0.005
Boundary for River Rch & Prof#=Potter Tributary,Reach-1,2
Up Type=0
Dn Type=3
Dn Slope=0.005
Boundary for River Rch & Prof#=Potter Tributary,Reach-1,3
Up Type=0
Dn Type=3
Dn Slope=0.005
Boundary for River Rch & Prof#=Potter Tributary,Reach-1,4
Up Type=0
Dn Type=3
Dn Slope=0.005
Boundary for River Rch & Prof#=Potter Tributary,Reach-1,5
Up Type=0
Dn Type=3
Dn Slope=0.005
Boundary for River Rch & Prof#=Potter Tributary,Reach-1,6
Up Type=0
Dn Type=3
Dn Slope=0.005
Boundary for River Rch & Prof#=Potter Tributary,Reach-1,7
Up Type=0
Dn Type=3
Dn Slope=0.005

--- Potter Tributary 2.g01 (geometry) ---

Geom Title=Existing Conditions

River Reach=Potter Tributary,Reach-1
Reach XY= 30
      2202925.00     13890675.00      2202922.76     13890430.93
      2202914.21     13890415.33      2202881.14     13890377.17
      2202872.50     13890331.04      2202866.84     13890318.95
      2202788.39     13890238.31      2202778.54     13890223.53
      2202775.37     13890209.83      2202776.21     13890085.51
      2202783.14     13890068.95      2202814.15     13890034.65
      2202822.75     13890019.06      2202825.50     13889914.83
      2202824.49     13889890.22      2202819.26     13889872.67
      2202785.81     13889834.63      2202777.17     13889819.02
      2202775.02     13889745.05      2202780.97     13889722.57
      2202811.16     13889688.16      2202817.67     13889674.90
      2202808.67     13889658.31      2202730.43     13889577.43
      2202725.25     13889559.79      2202724.14     13889525.02
      2202728.52     13889476.53      2202766.74     13889431.01
      2202773.01     13889418.73      2202775.00     13889375.00

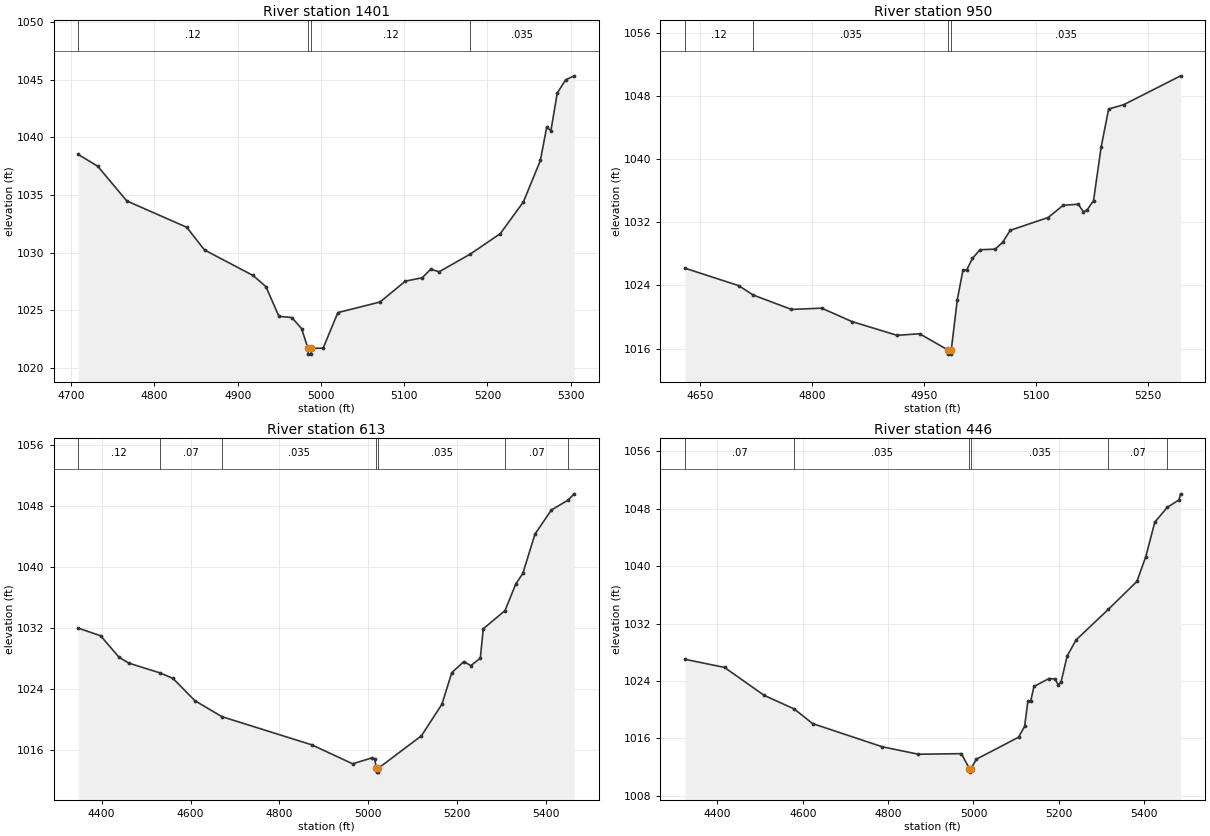
Type RM Length L Ch R = 1,1401,451,451,451
BEGIN DESCRIPTION:
Potter Tributary 2 3.0
END DESCRIPTION:
XS GIS Cut Line= 3
      2203174.98     13890774.99      2202925.00     13890625.00
      2202624.96     13890675.01
#Sta/Elev= 30
  4708.5 1038.50  4731.8 1037.48  4766.8 1034.47  4838.7 1032.19  4860.1 1030.22
  4918.4 1028.01  4933.9 1027.04  4949.5 1024.47  4965.0 1024.36  4976.7 1023.41
  4984.4 1021.69  4984.7 1021.19  4988.2 1021.19  4988.4 1021.69  5002.6 1021.71
  5020.3 1024.79  5071.0 1025.71  5101.4 1027.52  5121.7 1027.81  5131.8 1028.55
  5142.0 1028.33  5179.3 1029.86  5215.5 1031.64  5243.3 1034.40  5263.6 1037.98
  5271.2 1040.86  5276.3 1040.57  5283.9 1043.83  5294.0 1044.97  5304.2 1045.32
#Mann=4,-1,0
  4708.5    0.12       0  4984.4    0.05       0  4988.4    0.12       0
  5179.3   0.035       0
Bank Sta=4984.4,4988.4
Exp/Cntr=0.3,0.1

Type RM Length L Ch R = 1,950,337,337,337
BEGIN DESCRIPTION:
Potter Tributary 2 2.0
END DESCRIPTION:
XS GIS Cut Line= 3
      2203146.54     13890272.66      2202775.00     13890225.00
      2202489.92     13890270.00
#Sta/Elev= 30
  4630.0 1026.19  4702.1 1023.97  4721.6 1022.78  4772.7 1020.96  4813.1 1021.12
  4853.4 1019.43  4913.9 1017.68  4944.1 1017.88  4982.4 1015.80  4982.7 1015.30
  4986.2 1015.30  4986.4 1015.80  4994.5 1022.19  5002.1 1025.96  5007.1 1025.96
  5014.7 1027.41  5024.8 1028.52  5045.1 1028.59  5055.2 1029.47  5065.3 1030.98
  5116.0 1032.60  5136.2 1034.15  5156.4 1034.28  5163.2 1033.31  5168.3 1033.59
  5176.7 1034.73  5186.8 1041.48  5196.9 1046.33  5217.2 1046.89  5293.2 1050.54
#Mann=4,-1,0
  4630.0    0.12       0  4721.6   0.035       0  4982.4   0.035       0
  4986.4   0.035       0
Bank Sta=4982.4,4986.4
Exp/Cntr=0.3,0.1

Type RM Length L Ch R = 1,613,167,167,167
BEGIN DESCRIPTION:
Potter Tributary 2 1.0
END DESCRIPTION:
XS GIS Cut Line= 3
      2203324.99     13890324.99      2202809.72     13889892.27
      2202429.11     13890118.05
#Sta/Elev= 30
  4347.6 1031.96  4397.7 1030.96  4439.3 1028.14  4461.4 1027.37  4531.1 1026.10
  4560.3 1025.39  4609.7 1022.46  4670.8 1020.36  4872.5 1016.68  4964.8 1014.19
  5007.7 1014.96  5014.3 1014.80  5018.3 1013.60  5018.5 1013.10  5022.0 1013.10
  5022.3 1013.60  5119.4 1017.86  5165.5 1021.99  5187.7 1026.13  5214.9 1027.58
  5230.5 1027.05  5251.9 1028.02  5258.5 1031.87  5307.5 1034.26  5331.8 1037.76
  5347.5 1039.12  5374.8 1044.27  5411.7 1047.43  5449.7 1048.74  5463.0 1049.55
#Mann=7,-1,0
  4347.6    0.12       0  4531.1    0.07       0  4670.8   0.035       0
  5018.3   0.035       0  5022.3   0.035       0  5307.5    0.07       0
  5449.7    0.12       0
Bank Sta=5018.3,5022.3
Exp/Cntr=0.3,0.1

Type RM Length L Ch R = 1,446,0,0,0
BEGIN DESCRIPTION:
Potter Tributary 2 0.1
END DESCRIPTION:
XS GIS Cut Line= 3
      2203299.98     13890180.32      2202774.48     13889754.92
      2202409.45     13890074.41
#Sta/Elev= 30
  4323.9 1027.03  4416.9 1025.89  4509.6 1022.01  4580.5 1020.10  4623.1 1018.08
  4786.2 1014.85  4870.9 1013.81  4971.6 1013.89  4990.4 1011.82  4990.7 1011.32
  4994.4 1011.82  5006.8 1013.12  5105.6 1016.18  5119.8 1017.71  5127.4 1021.21
  5134.0 1021.20  5141.6 1023.24  5176.7 1024.34  5191.0 1024.29  5198.6 1023.45
  5205.2 1023.90  5219.4 1027.49  5240.3 1029.72  5315.7 1033.97  5382.7 1037.86
  5403.6 1041.32  5424.6 1046.11  5453.9 1048.17  5481.4 1049.21  5485.1 1050.05
#Mann=6,-1,0
  4323.9    0.07       0  4580.5   0.035       0  4990.4   0.035       0
  4994.4   0.035       0  5315.7    0.07       0  5453.9    0.12       0
Bank Sta=4990.4,4994.4
Exp/Cntr=0.3,0.1

Chan Stop Cuts=-1