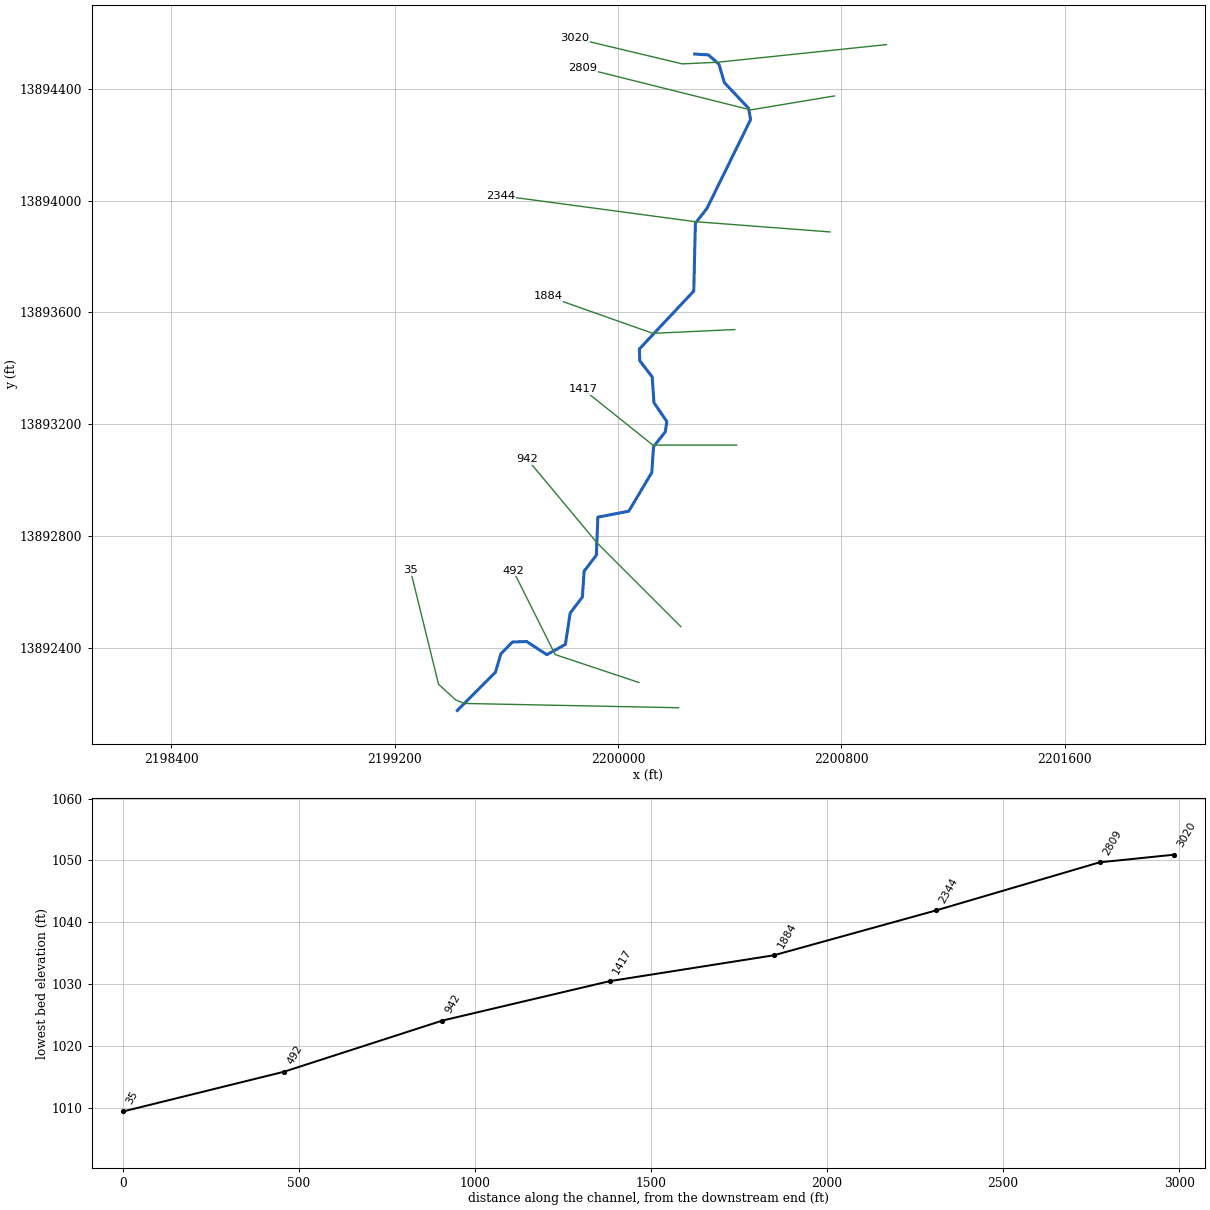
--- Potter Tributary 3.prj (project) ---

Proj Title=Potter Tributary 3 Base Level Engineering
Current Plan=p01
Default Exp/Contr=0.3,0.1
English Units
Geom File=g01
Flow File=f01
Plan File=p01
BEGIN DESCRIPTION:
Potter Tributary 3
END DESCRIPTION:

--- Potter Tributary 3.p01 (plan) ---

Plan Title=Multiple Run
Short Identifier=Multiple
Geom File=g01
Flow File=f01
Subcritical Flow
K Sum by GR= 0
Std Step Tol= 0.01
Critical Tol= 0.01
Num of Std Step Trials= 20
Max Error Tol= 0.3
Flow Tol Ratio= 0.001
Split Flow NTrial= 30
Split Flow Tol= 0.02
Split Flow Ratio= 0.02
Log Output Level= 0
Friction Slope Method= 1
Unsteady Friction Slope Method= 2
Unsteady Bridges Friction Slope Method= 1
Parabolic Critical Depth
Global Vel Dist=  1 , 1 , 1
Global Log Level= 0
CheckData=True
Encroach Param= -1, 0, 0, 0
BEGIN DESCRIPTION:
Multiple Run
END DESCRIPTION:

--- Potter Tributary 3.f01 (steady flow) ---

Flow Title=Multiple
Number of Profiles=7
Profile Names=10-year,25-year,50-year,1pct_min,100-year,1pct_plu,500-year
River Rch & RM= Potter Tributary,Reach-1,3020
    1134    1924    2676    1805    3601    7185    6447
River Rch & RM= Potter Tributary,Reach-1,35
    2772    4905    7016    4847    9670   19295   18192
Boundary for River Rch & Prof#=Potter Tributary,Reach-1,1
Up Type=0
Dn Type=3
Dn Slope=0.005
Boundary for River Rch & Prof#=Potter Tributary,Reach-1,2
Up Type=0
Dn Type=3
Dn Slope=0.005
Boundary for River Rch & Prof#=Potter Tributary,Reach-1,3
Up Type=0
Dn Type=3
Dn Slope=0.005
Boundary for River Rch & Prof#=Potter Tributary,Reach-1,4
Up Type=0
Dn Type=3
Dn Slope=0.005
Boundary for River Rch & Prof#=Potter Tributary,Reach-1,5
Up Type=0
Dn Type=3
Dn Slope=0.005
Boundary for River Rch & Prof#=Potter Tributary,Reach-1,6
Up Type=0
Dn Type=3
Dn Slope=0.005
Boundary for River Rch & Prof#=Potter Tributary,Reach-1,7
Up Type=0
Dn Type=3
Dn Slope=0.005

--- Potter Tributary 3.g01 (geometry) ---

Geom Title=Existing Conditions

River Reach=Potter Tributary,Reach-1
Reach XY= 30
      2200275.00     13894525.00      2200323.97     13894521.86
      2200361.61     13894488.54      2200380.86     13894422.73
      2200467.50     13894331.05      2200474.98     13894290.41
      2200318.88     13893972.82      2200277.24     13893919.07
      2200271.46     13893676.46      2200076.62     13893468.97
      2200078.34     13893426.75      2200122.62     13893369.03
      2200128.89     13893276.58      2200174.91     13893209.61
      2200169.63     13893172.82      2200127.38     13893119.03
      2200121.18     13893026.58      2200038.62     13892888.27
      2199927.95     13892867.02      2199922.73     13892730.95
      2199878.86     13892673.40      2199872.65     13892580.97
      2199828.86     13892523.40      2199811.74     13892411.20
      2199745.28     13892374.62      2199673.24     13892421.64
      2199622.45     13892420.01      2199580.75     13892377.61
      2199561.37     13892311.80      2199425.00     13892175.00

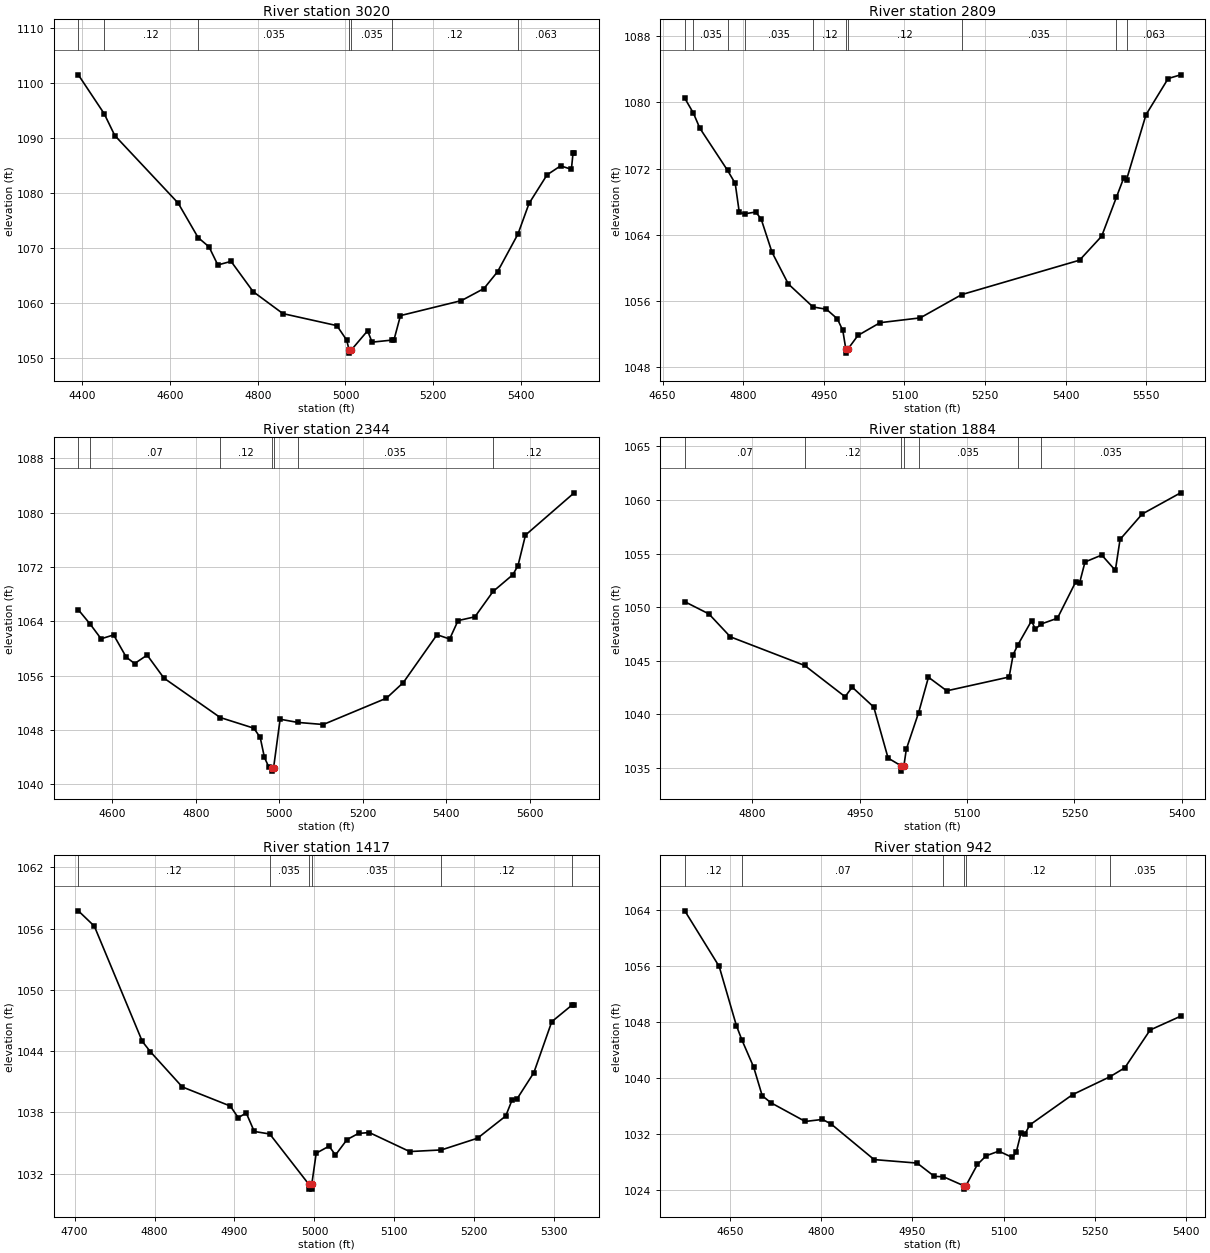
Type RM Length L Ch R = 1,3020,211,211,211
BEGIN DESCRIPTION:
Potter Tributary 3 7.0
END DESCRIPTION:
XS GIS Cut Line= 4
      2200961.39     13894558.76      2200355.49     13894495.47
      2200230.23     13894489.80      2199844.93     13894581.72
#Sta/Elev= 30
  4390.8 1101.43  4449.8 1094.37  4473.9 1090.42  4618.4 1078.16  4663.9 1071.90
  4688.8 1070.22  4708.9 1066.93  4739.1 1067.58  4789.4 1062.09  4857.4 1058.10
  4980.4 1055.92  5002.7 1053.30  5008.5 1051.43  5008.8 1050.93  5012.5 1051.43
  5050.5 1054.99  5060.6 1052.92  5106.5 1053.30  5110.6 1053.33  5125.4 1057.74
  5264.4 1060.46  5315.8 1062.65  5346.8 1065.70  5393.4 1072.55  5418.6 1078.09
  5459.7 1083.28  5490.6 1084.91  5515.2 1084.29  5518.9 1087.21  5521.5 1087.21
#Mann=7,-1,0
  4390.8   0.035       0  4449.8    0.12       0  4663.9   0.035       0
  5008.5   0.035       0  5012.5   0.035       0  5106.5    0.12       0
  5393.4   0.063       0
Bank Sta=5008.5,5012.5
Exp/Cntr=0.3,0.1

Type RM Length L Ch R = 1,2809,465,465,465
BEGIN DESCRIPTION:
Potter Tributary 3 6.0
END DESCRIPTION:
XS GIS Cut Line= 3
      2200775.00     13894375.00      2200475.00     13894325.00
      2199875.01     13894475.00
#Sta/Elev= 30
  4691.2 1080.50  4707.3 1078.69  4719.1 1076.89  4770.7 1071.79  4785.0 1070.21
  4792.6 1066.70  4802.4 1066.53  4823.0 1066.75  4833.1 1065.94  4853.4 1061.90
  4883.8 1058.06  4929.7 1055.28  4954.8 1055.00  4975.1 1053.84  4985.2 1052.44
  4990.8 1050.20  4991.1 1049.70  4994.8 1050.20  5013.4 1051.84  5054.6 1053.38
  5129.3 1053.96  5206.4 1056.77  5425.7 1060.93  5466.9 1063.83  5494.4 1068.55
  5508.2 1070.92  5513.2 1070.67  5549.4 1078.51  5590.6 1082.88  5613.8 1083.33
#Mann=10,-1,0
  4691.2    0.12       0  4707.3   0.035       0  4770.7    0.07       0
  4802.4   0.035       0  4929.7    0.12       0  4990.8    0.05       0
  4994.8    0.12       0  5206.4   0.035       0  5494.4    0.12       0
  5513.2   0.063       0
Bank Sta=4990.8,4994.8
Exp/Cntr=0.3,0.1

Type RM Length L Ch R = 1,2344,460,460,460
BEGIN DESCRIPTION:
Potter Tributary 3 5.0
END DESCRIPTION:
XS GIS Cut Line= 3
      2200759.37     13893888.11      2200275.00     13893925.00
      2199579.40     13894018.24
#Sta/Elev= 30
  4518.6 1065.70  4547.0 1063.58  4573.1 1061.42  4603.2 1061.99  4633.3 1058.72
  4653.4 1057.77  4683.4 1059.02  4723.6 1055.63  4858.4 1049.82  4938.9 1048.25
  4954.2 1046.89  4964.3 1043.95  4974.3 1042.59  4982.3 1042.42  4982.6 1041.92
  4986.3 1042.42  5001.9 1049.57  5043.8 1049.10  5105.3 1048.79  5256.6 1052.67
  5297.0 1054.97  5377.7 1062.02  5408.0 1061.39  5428.1 1064.10  5468.5 1064.66
  5511.9 1068.39  5559.3 1070.86  5571.7 1072.21  5589.6 1076.70  5706.2 1082.93
#Mann=7,-1,0
  4518.6   0.035       0  4547.0    0.07       0  4858.4    0.12       0
  4982.3    0.05       0  4986.3    0.12       0  5043.8   0.035       0
  5511.9    0.12       0
Bank Sta=4982.3,4986.3
Exp/Cntr=0.3,0.1

Type RM Length L Ch R = 1,1884,467,467,467
BEGIN DESCRIPTION:
Potter Tributary 3 4.0
END DESCRIPTION:
XS GIS Cut Line= 3
      2200418.67     13893538.72      2200125.00     13893525.00
      2199749.04     13893657.75
#Sta/Elev= 30
  4705.7 1050.50  4739.4 1049.36  4769.4 1047.22  4873.1 1044.55  4929.6 1041.63
  4939.6 1042.52  4969.7 1040.66  4989.7 1035.90  5007.8 1035.18  5008.1 1034.68
  5011.8 1035.18  5015.2 1036.73  5032.4 1040.15  5046.1 1043.45  5071.7 1042.18
  5158.8 1043.47  5164.5 1045.57  5170.6 1046.42  5190.1 1048.72  5195.4 1047.94
  5203.6 1048.42  5226.3 1048.96  5251.9 1052.36  5257.3 1052.27  5264.8 1054.21
  5288.2 1054.86  5307.2 1053.43  5313.8 1056.32  5344.7 1058.69  5398.4 1060.67
#Mann=7,-1,0
  4705.7    0.07       0  4873.1    0.12       0  5007.8    0.05       0
  5011.8    0.12       0  5032.4   0.035       0  5170.6    0.12       0
  5203.6   0.035       0
Bank Sta=5007.8,5011.8
Exp/Cntr=0.3,0.1

Type RM Length L Ch R = 1,1417,475,475,475
BEGIN DESCRIPTION:
Potter Tributary 3 3.0
END DESCRIPTION:
XS GIS Cut Line= 3
      2200424.98     13893125.00      2200125.00     13893125.00
      2199875.03     13893324.98
#Sta/Elev= 30
  4704.7 1057.75  4724.7 1056.25  4784.7 1044.96  4794.7 1043.96  4834.7 1040.50
  4894.7 1038.63  4904.7 1037.49  4914.7 1037.95  4924.7 1036.14  4944.1 1035.89
  4992.7 1030.99  4992.9 1030.49  4996.4 1030.49  4996.7 1030.99  5002.2 1034.01
  5018.3 1034.70  5026.3 1033.83  5040.7 1035.34  5055.1 1035.95  5068.7 1036.03
  5119.1 1034.17  5158.8 1034.33  5204.0 1035.48  5239.2 1037.65  5247.2 1039.23
  5253.6 1039.36  5274.4 1041.90  5296.8 1046.89  5321.5 1048.48  5324.8 1048.49
#Mann=6,-1,0
  4704.7    0.12       0  4944.1   0.035       0  4992.7   0.035       0
  4996.7   0.035       0  5158.8    0.12       0  5321.5   0.035       0
Bank Sta=4992.7,4996.7
Exp/Cntr=0.3,0.1

Type RM Length L Ch R = 1,942,450,450,450
BEGIN DESCRIPTION:
Potter Tributary 3 2.0
END DESCRIPTION:
XS GIS Cut Line= 3
      2200224.97     13892475.03      2199925.00     13892775.00
      2199675.02     13893074.97
#Sta/Elev= 30
  4576.2 1063.89  4632.7 1055.94  4661.0 1047.48  4670.3 1045.38  4689.3 1041.57
  4703.4 1037.47  4717.6 1036.47  4774.1 1033.79  4802.4 1034.08  4816.6 1033.43
  4887.3 1028.34  4958.0 1027.84  4986.3 1025.94  5001.1 1025.89  5034.2 1024.62
  5034.5 1024.12  5038.2 1024.62  5057.0 1027.64  5071.4 1028.89  5092.2 1029.55
  5114.3 1028.65  5120.8 1029.39  5128.6 1032.13  5135.1 1031.99  5143.0 1033.29
  5213.3 1037.62  5274.8 1040.18  5299.2 1041.46  5340.8 1046.86  5390.9 1048.83
#Mann=6,-1,0
  4576.2    0.12       0  4670.3    0.07       0  5001.1    0.12       0
  5034.2    0.05       0  5038.2    0.12       0  5274.8   0.035       0
Bank Sta=5034.2,5038.2
Exp/Cntr=0.3,0.1

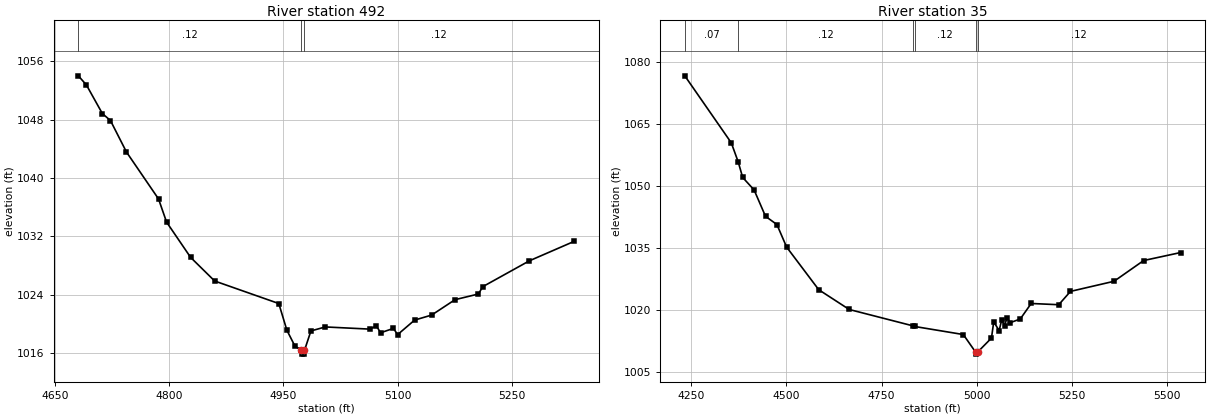
Type RM Length L Ch R = 1,492,457,457,457
BEGIN DESCRIPTION:
Potter Tributary 3 1.0
END DESCRIPTION:
XS GIS Cut Line= 3
      2200075.02     13892274.99      2199775.00     13892375.00
      2199624.98     13892675.03
#Sta/Elev= 30
  4680.4 1054.03  4691.0 1052.78  4712.0 1048.85  4722.6 1047.90  4743.7 1043.57
  4785.8 1037.14  4796.4 1033.96  4828.0 1029.12  4859.6 1025.88  4943.9 1022.79
  4954.5 1019.13  4965.0 1016.97  4973.6 1016.35  4973.8 1015.85  4977.3 1015.85
  4977.6 1016.35  4986.1 1019.03  5005.0 1019.58  5063.7 1019.28  5072.1 1019.73
  5077.7 1018.78  5094.5 1019.38  5100.1 1018.53  5122.4 1020.52  5144.8 1021.21
  5175.5 1023.32  5206.3 1024.10  5211.9 1025.10  5273.4 1028.66  5332.1 1031.32
#Mann=3,-1,0
  4680.4    0.12       0  4973.6    0.05       0  4977.6    0.12       0
Bank Sta=4973.6,4977.6
Exp/Cntr=0.3,0.1

Type RM Length L Ch R = 1,35,0,0,0
BEGIN DESCRIPTION:
Potter Tributary 3 0.1
END DESCRIPTION:
XS GIS Cut Line= 5
      2200217.17     13892184.63      2199450.00     13892200.00
      2199418.99     13892212.74      2199357.66     13892268.40
      2199257.19     13892676.23
#Sta/Elev= 30
  4232.7 1076.63  4354.9 1060.46  4373.1 1055.85  4384.9 1052.09  4414.9 1049.08
  4444.9 1042.71  4474.9 1040.72  4500.4 1035.28  4584.9 1024.98  4665.0 1020.21
  4833.3 1016.24  4836.7 1016.11  4965.0 1014.16  4997.2 1009.93  4997.7 1009.43
  5002.8 1009.93  5039.0 1013.31  5045.0 1017.22  5059.2 1015.12  5066.0 1017.69
  5073.4 1016.27  5080.2 1018.27  5087.6 1017.00  5114.8 1017.92  5143.5 1021.66
  5215.9 1021.36  5246.8 1024.58  5361.3 1027.02  5439.2 1032.03  5536.4 1033.96
#Mann=6,-1,0
  4232.7    0.07       0  4373.1    0.12       0  4833.3   0.035       0
  4836.7    0.12       0  4997.2    0.05       0  5002.8    0.12       0
Bank Sta=4997.2,5002.8
Exp/Cntr=0.3,0.1

Chan Stop Cuts=-1