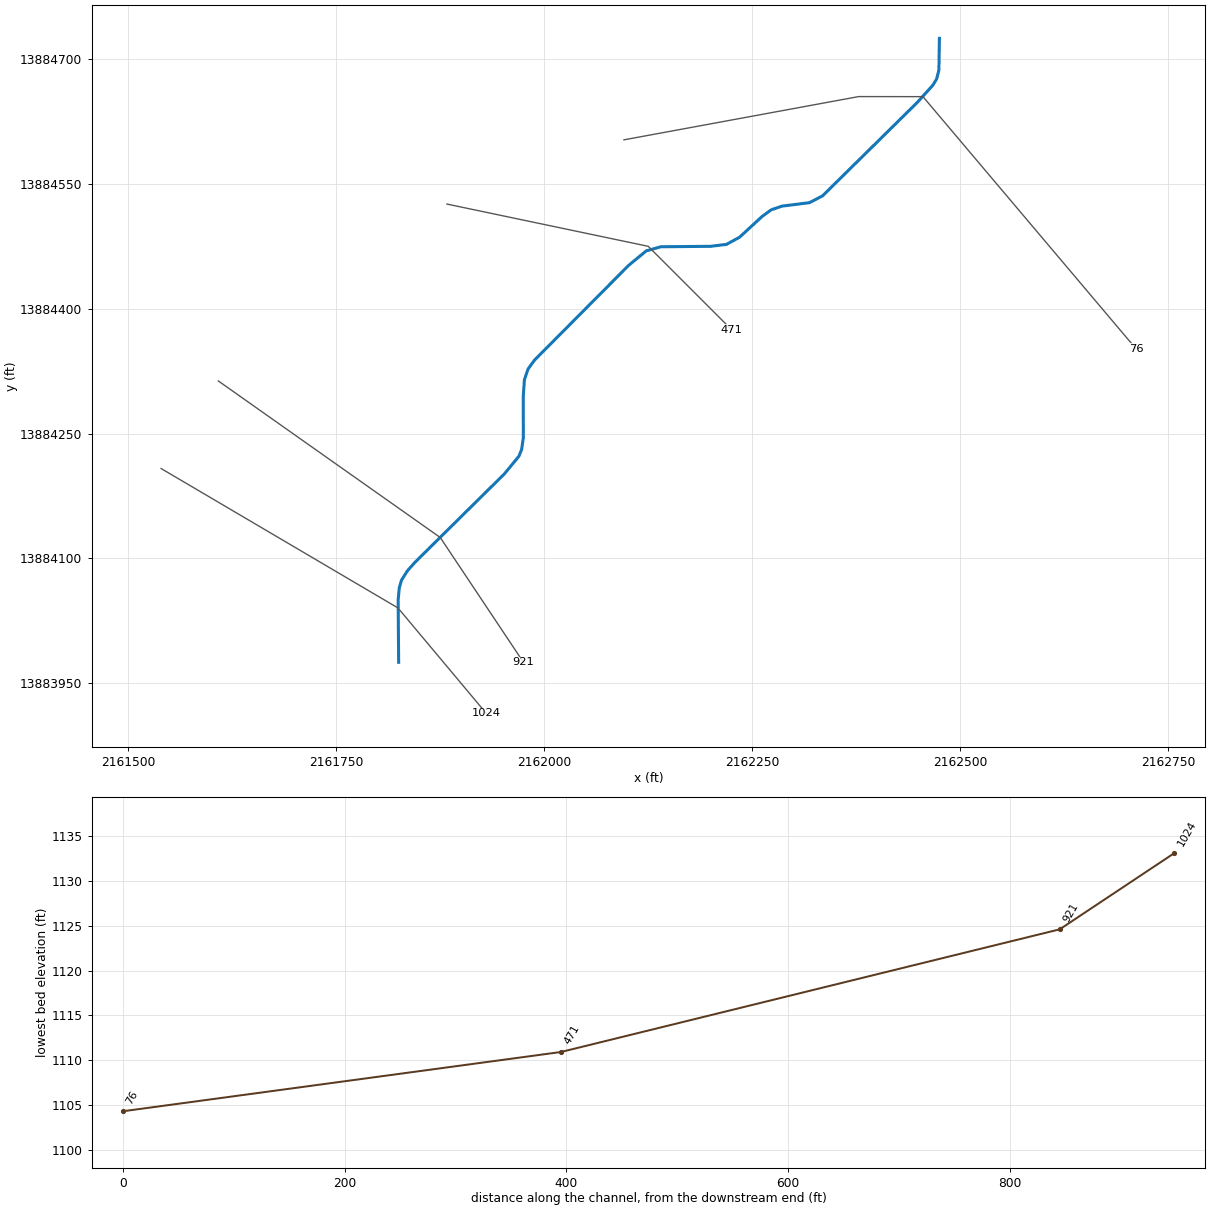
--- Puter Creek Tributary 1.prj (project) ---

Proj Title=Puter Creek Tributary 1 Base Level Engineering
Current Plan=p01
Default Exp/Contr=0.3,0.1
English Units
Geom File=g01
Flow File=f01
Plan File=p01
BEGIN DESCRIPTION:
Puter Creek Tributary 1
END DESCRIPTION:

--- Puter Creek Tributary 1.p01 (plan) ---

Plan Title=Multiple Run
Short Identifier=Multiple
Geom File=g01
Flow File=f01
Subcritical Flow
K Sum by GR= 0
Std Step Tol= 0.01
Critical Tol= 0.01
Num of Std Step Trials= 20
Max Error Tol= 0.3
Flow Tol Ratio= 0.001
Split Flow NTrial= 30
Split Flow Tol= 0.02
Split Flow Ratio= 0.02
Log Output Level= 0
Friction Slope Method= 1
Unsteady Friction Slope Method= 2
Unsteady Bridges Friction Slope Method= 1
Parabolic Critical Depth
Global Vel Dist=  1 , 1 , 1
Global Log Level= 0
CheckData=True
Encroach Param= -1, 0, 0, 0
BEGIN DESCRIPTION:
Multiple Run
END DESCRIPTION:

--- Puter Creek Tributary 1.f01 (steady flow) ---

Flow Title=Multiple
Number of Profiles=7
Profile Names=10-year,25-year,50-year,1pct_min,100-year,1pct_plu,500-year
River Rch & RM= Puter Creek Trib,Reach-1,1024
     691    1143    1562    1038    2070    4131    3592
River Rch & RM= Puter Creek Trib,Reach-1,76
     923    1555    2153    1446    2886    5759    5128
Boundary for River Rch & Prof#=Puter Creek Trib,Reach-1,1
Up Type=0
Dn Type=3
Dn Slope=0.005
Boundary for River Rch & Prof#=Puter Creek Trib,Reach-1,2
Up Type=0
Dn Type=3
Dn Slope=0.005
Boundary for River Rch & Prof#=Puter Creek Trib,Reach-1,3
Up Type=0
Dn Type=3
Dn Slope=0.005
Boundary for River Rch & Prof#=Puter Creek Trib,Reach-1,4
Up Type=0
Dn Type=3
Dn Slope=0.005
Boundary for River Rch & Prof#=Puter Creek Trib,Reach-1,5
Up Type=0
Dn Type=3
Dn Slope=0.005
Boundary for River Rch & Prof#=Puter Creek Trib,Reach-1,6
Up Type=0
Dn Type=3
Dn Slope=0.005
Boundary for River Rch & Prof#=Puter Creek Trib,Reach-1,7
Up Type=0
Dn Type=3
Dn Slope=0.005

--- Puter Creek Tributary 1.g01 (geometry) ---

Geom Title=Existing Conditions

River Reach=Puter Creek Trib,Reach-1
Reach XY= 30
      2161825.00     13883975.00      2161824.41     13884050.25
      2161825.81     13884064.66      2161828.38     13884073.60
      2161835.43     13884084.82      2161844.62     13884095.16
      2161952.12     13884201.48      2161969.48     13884222.57
      2161972.85     13884230.89      2161974.87     13884245.06
      2161974.82     13884295.08      2161976.17     13884314.52
      2161980.52     13884327.43      2161988.40     13884338.30
      2162101.48     13884452.13      2162122.57     13884469.48
      2162140.22     13884474.48      2162200.00     13884475.00
      2162219.03     13884477.33      2162234.65     13884485.84
      2162261.96     13884510.95      2162272.83     13884518.86
      2162285.71     13884523.28      2162318.97     13884527.50
      2162334.68     13884535.76      2162448.65     13884648.20
      2162467.24     13884668.79      2162471.73     13884676.36
      2162474.41     13884686.84      2162475.00     13884725.00

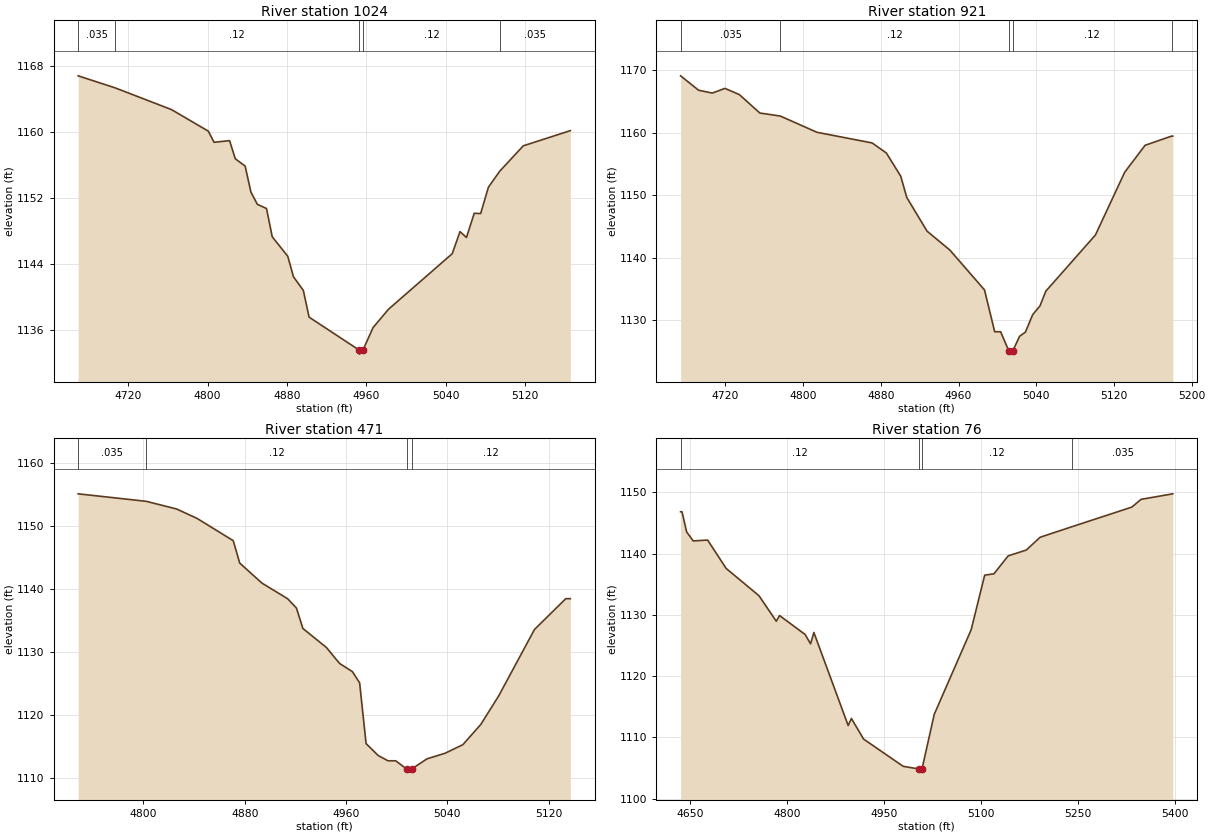
Type RM Length L Ch R = 1,1024,103,103,103
BEGIN DESCRIPTION:
Puter Creek Tributary 1 3.0
END DESCRIPTION:
XS GIS Cut Line= 3
      2161539.47     13884207.92      2161824.21     13884040.33
      2161930.33     13883913.60
#Sta/Elev= 30
  4669.6 1166.76  4706.9 1165.30  4763.6 1162.67  4800.7 1160.06  4806.5 1158.71
  4822.1 1158.91  4827.9 1156.71  4837.8 1155.83  4843.6 1152.68  4850.1 1151.19
  4859.3 1150.69  4865.1 1147.26  4880.7 1144.91  4886.5 1142.41  4896.4 1140.77
  4902.2 1137.53  4952.5 1133.55  4952.8 1133.05  4956.5 1133.55  4966.6 1136.26
  4982.2 1138.49  5046.4 1145.22  5054.2 1147.89  5060.7 1147.18  5068.5 1150.11
  5075.0 1150.08  5082.8 1153.27  5094.3 1155.22  5117.9 1158.28  5165.3 1160.12
#Mann=5,-1,0
  4669.6   0.035       0  4706.9    0.12       0  4952.5    0.05       0
  4956.5    0.12       0  5094.3   0.035       0
Bank Sta=4952.5,4956.5
Exp/Cntr=0.3,0.1

Type RM Length L Ch R = 1,921,450,450,450
BEGIN DESCRIPTION:
Puter Creek Tributary 1 2.0
END DESCRIPTION:
XS GIS Cut Line= 3
      2161608.32     13884313.13      2161875.00     13884125.00
      2161974.98     13883975.03
#Sta/Elev= 30
  4673.9 1169.09  4692.4 1166.79  4706.5 1166.33  4719.5 1167.08  4734.3 1166.10
  4755.5 1163.14  4776.5 1162.66  4814.3 1160.06  4871.0 1158.36  4885.7 1156.75
  4900.5 1153.04  4906.7 1149.64  4927.6 1144.25  4951.0 1141.24  4986.7 1134.86
  4997.2 1128.17  5003.3 1128.17  5011.8 1125.09  5012.0 1124.59  5015.8 1125.09
  5022.8 1127.44  5028.8 1128.11  5036.3 1130.90  5043.8 1132.30  5049.8 1134.65
  5100.9 1143.64  5131.0 1153.67  5152.0 1157.98  5179.2 1159.45  5180.5 1159.45
#Mann=5,-1,0
  4673.9   0.035       0  4776.5    0.12       0  5011.8    0.05       0
  5015.8    0.12       0  5179.2   0.035       0
Bank Sta=5011.8,5015.8
Exp/Cntr=0.3,0.1

Type RM Length L Ch R = 1,471,395,395,395
BEGIN DESCRIPTION:
Puter Creek Tributary 1 1.0
END DESCRIPTION:
XS GIS Cut Line= 3
      2161883.04     13884525.80      2162125.00     13884475.00
      2162225.03     13884374.97
#Sta/Elev= 30
  4748.4 1155.09  4802.2 1153.90  4826.2 1152.68  4842.4 1151.18  4870.9 1147.65
  4876.0 1144.10  4893.5 1140.93  4913.9 1138.43  4920.8 1136.96  4925.9 1133.72
  4944.5 1130.70  4954.8 1128.18  4965.0 1126.87  4970.7 1125.09  4975.8 1115.45
  4985.4 1113.55  4993.1 1112.72  4999.2 1112.72  5007.8 1111.42  5008.0 1110.92
  5011.5 1110.92  5011.8 1111.42  5023.9 1113.03  5038.1 1113.91  5052.2 1115.27
  5066.4 1118.49  5080.5 1123.01  5108.8 1133.56  5133.5 1138.45  5137.1 1138.45
#Mann=4,-1,0
  4748.4   0.035       0  4802.2    0.12       0  5007.8    0.05       0
  5011.8    0.12       0
Bank Sta=5007.8,5011.8
Exp/Cntr=0.3,0.1

Type RM Length L Ch R = 1,76,0,0,0
BEGIN DESCRIPTION:
Puter Creek Tributary 1 0.1
END DESCRIPTION:
XS GIS Cut Line= 4
      2162095.78     13884602.99      2162378.04     13884655.00
      2162455.22     13884654.91      2162711.14     13884352.06
#Sta/Elev= 30
  4635.8 1146.83  4638.0 1146.83  4645.2 1143.53  4655.3 1142.07  4677.6 1142.21
  4706.2 1137.58  4757.0 1133.12  4783.7 1128.96  4788.7 1129.89  4828.2 1126.80
  4836.7 1125.27  4841.8 1127.12  4894.8 1111.93  4899.8 1113.08  4918.7 1109.71
  4979.8 1105.27  5004.9 1104.82  5005.2 1104.32  5008.9 1104.82  5027.8 1113.75
  5084.9 1127.57  5105.8 1136.48  5120.1 1136.70  5142.1 1139.63  5170.1 1140.58
  5191.5 1142.67  5241.5 1144.42  5333.2 1147.59  5347.5 1148.86  5396.5 1149.76
#Mann=4,-1,0
  4635.8    0.12       0  5004.9    0.05       0  5008.9    0.12       0
  5241.5   0.035       0
Bank Sta=5004.9,5008.9
Exp/Cntr=0.3,0.1

Chan Stop Cuts=-1