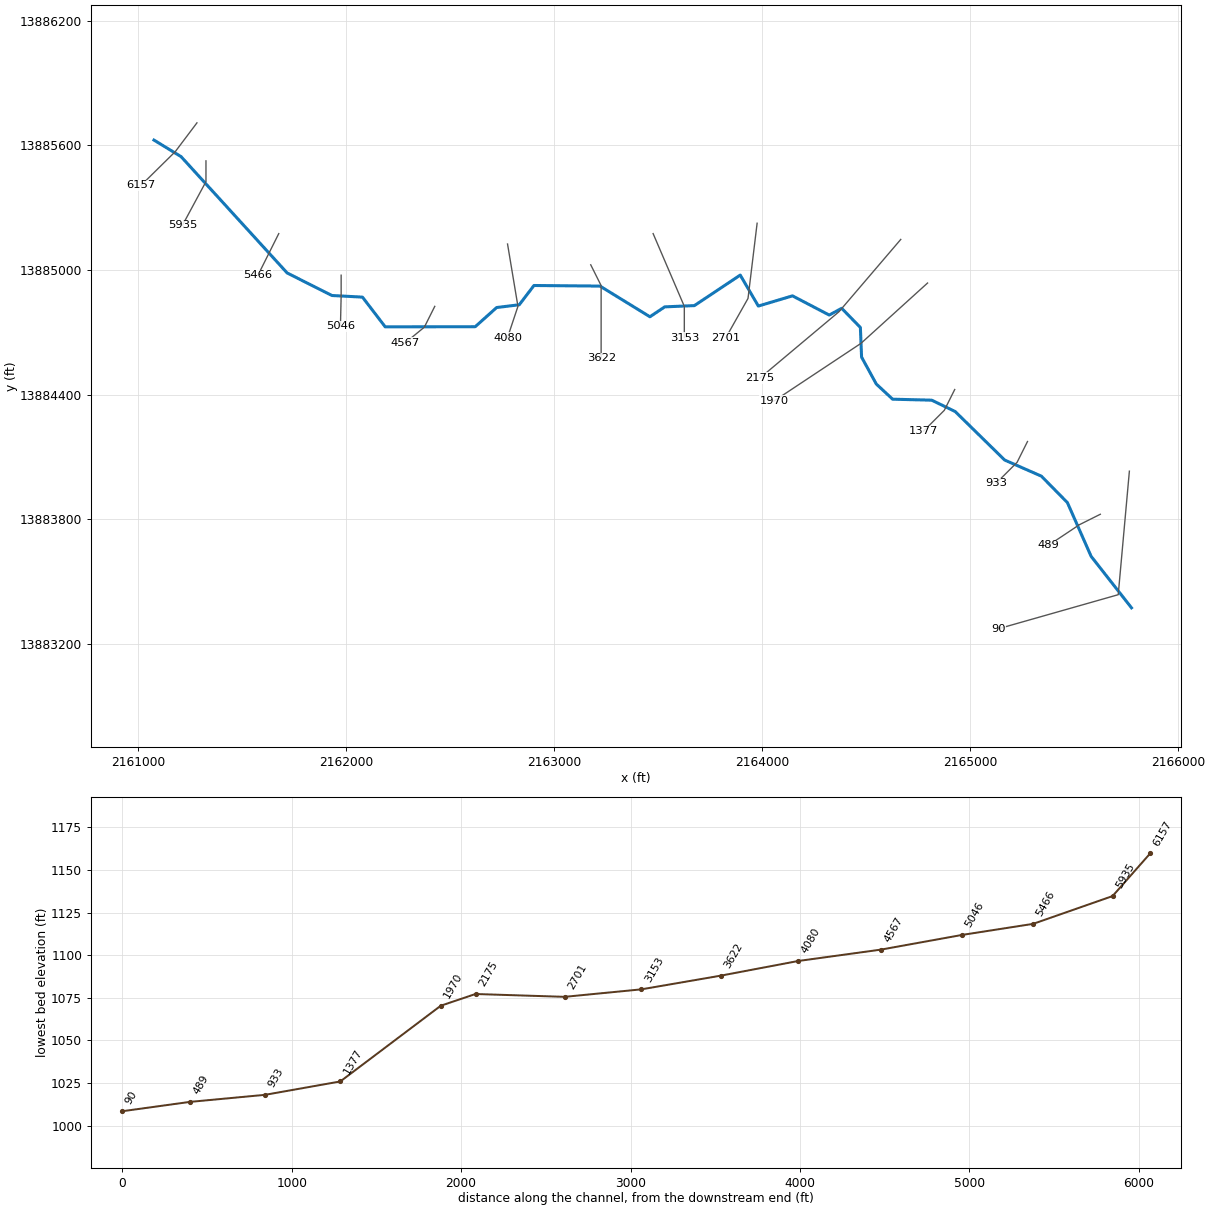
--- Puter Creek.prj (project) ---

Proj Title=Puter Creek Base Level Engineering
Current Plan=p01
Default Exp/Contr=0.3,0.1
English Units
Geom File=g01
Flow File=f01
Plan File=p01
BEGIN DESCRIPTION:
Puter Creek
END DESCRIPTION:

--- Puter Creek.p01 (plan) ---

Plan Title=Multiple Run
Short Identifier=Multiple
Geom File=g01
Flow File=f01
Subcritical Flow
K Sum by GR= 0
Std Step Tol= 0.01
Critical Tol= 0.01
Num of Std Step Trials= 20
Max Error Tol= 0.3
Flow Tol Ratio= 0.001
Split Flow NTrial= 30
Split Flow Tol= 0.02
Split Flow Ratio= 0.02
Log Output Level= 0
Friction Slope Method= 1
Unsteady Friction Slope Method= 2
Unsteady Bridges Friction Slope Method= 1
Parabolic Critical Depth
Global Vel Dist=  1 , 1 , 1
Global Log Level= 0
CheckData=True
Encroach Param= -1, 0, 0, 0
BEGIN DESCRIPTION:
Multiple Run
END DESCRIPTION:

--- Puter Creek.f01 (steady flow) ---

Flow Title=Multiple
Number of Profiles=7
Profile Names=10-year,25-year,50-year,1pct_min,100-year,1pct_plu,500-year
River Rch & RM= Puter Creek,Reach-1,6157
     923    1555    2153    1446    2886    5759    5128
River Rch & RM= Puter Creek,Reach-1,4080
    1778    3110    4417    3036    6058   12086   11278
Boundary for River Rch & Prof#=Puter Creek,Reach-1,1
Up Type=0
Dn Type=3
Dn Slope=0.005
Boundary for River Rch & Prof#=Puter Creek,Reach-1,2
Up Type=0
Dn Type=3
Dn Slope=0.005
Boundary for River Rch & Prof#=Puter Creek,Reach-1,3
Up Type=0
Dn Type=3
Dn Slope=0.005
Boundary for River Rch & Prof#=Puter Creek,Reach-1,4
Up Type=0
Dn Type=3
Dn Slope=0.005
Boundary for River Rch & Prof#=Puter Creek,Reach-1,5
Up Type=0
Dn Type=3
Dn Slope=0.005
Boundary for River Rch & Prof#=Puter Creek,Reach-1,6
Up Type=0
Dn Type=3
Dn Slope=0.005
Boundary for River Rch & Prof#=Puter Creek,Reach-1,7
Up Type=0
Dn Type=3
Dn Slope=0.005

--- Puter Creek.g01 (geometry) ---

Geom Title=Existing Conditions

River Reach=Puter Creek,Reach-1
Reach XY= 30
      2161075.00     13885625.00      2161205.23     13885545.42
      2161715.32     13884985.76      2161930.52     13884877.36
      2162077.46     13884869.54      2162186.83     13884726.62
      2162619.57     13884727.13      2162722.58     13884819.46
      2162831.43     13884832.79      2162901.95     13884925.43
      2163219.48     13884922.65      2163459.58     13884775.03
      2163530.93     13884822.70      2163673.44     13884828.76
      2163893.85     13884975.55      2163980.83     13884826.54
      2164145.05     13884875.60      2164321.77     13884783.25
      2164381.69     13884815.71      2164471.46     13884723.56
      2164477.25     13884580.93      2164547.99     13884451.48
      2164626.45     13884378.53      2164814.50     13884373.80
      2164927.30     13884319.17      2165165.32     13884085.76
      2165341.68     13884008.36      2165466.86     13883881.06
      2165580.85     13883622.71      2165775.00     13883375.00

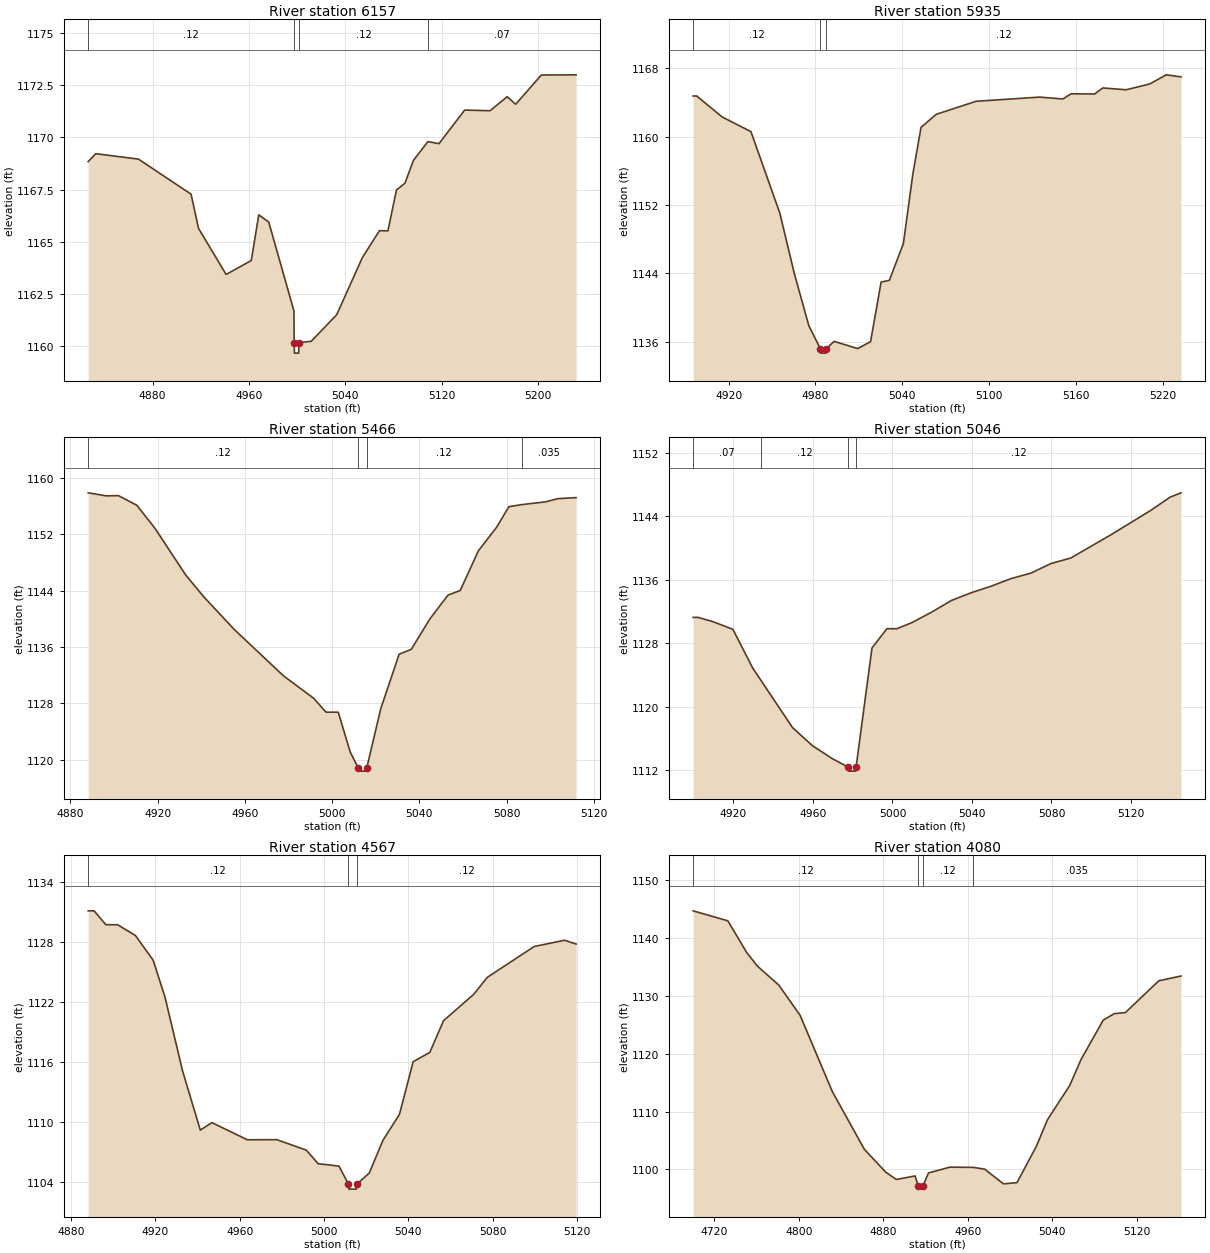
Type RM Length L Ch R = 1,6157,222,222,222
BEGIN DESCRIPTION:
Puter Creek 14.0
END DESCRIPTION:
XS GIS Cut Line= 3
      2161281.64     13885707.83      2161177.36     13885569.28
      2161012.39     13885406.73
#Sta/Elev= 30
  4826.6 1168.84  4832.9 1169.22  4868.3 1168.96  4912.0 1167.28  4918.2 1165.64
  4941.1 1163.43  4962.0 1164.10  4968.2 1166.29  4976.5 1165.94  4997.4 1161.68
  4997.6 1160.16  4997.8 1159.66  5001.3 1159.66  5001.6 1160.16  5011.8 1160.23
  5032.9 1161.50  5054.2 1164.24  5068.4 1165.53  5075.4 1165.52  5082.5 1167.48
  5089.5 1167.80  5096.6 1168.90  5108.6 1169.80  5117.8 1169.70  5139.1 1171.31
  5160.2 1171.28  5174.4 1171.95  5181.5 1171.59  5202.7 1172.99  5231.6 1173.00
#Mann=4,-1,0
  4826.6    0.12       0  4997.6    0.05       0  5001.6    0.12       0
  5108.6    0.07       0
Bank Sta=4997.6,5001.6
Exp/Cntr=0.3,0.1

Type RM Length L Ch R = 1,5935,469,469,469
BEGIN DESCRIPTION:
Puter Creek 13.0
END DESCRIPTION:
XS GIS Cut Line= 3
      2161325.00     13885524.99      2161325.00     13885425.00
      2161212.41     13885215.99
#Sta/Elev= 30
  4895.4 1164.77  4897.9 1164.77  4915.4 1162.32  4935.4 1160.59  4955.4 1151.02
  4965.4 1143.95  4975.4 1137.87  4983.4 1135.14  4983.6 1134.64  4987.1 1134.64
  4987.4 1135.14  4992.9 1136.02  5009.2 1135.17  5018.1 1135.98  5025.4 1142.96
  5031.1 1143.17  5040.8 1147.47  5047.3 1155.57  5053.0 1161.09  5063.5 1162.62
  5091.1 1164.15  5134.9 1164.64  5151.1 1164.42  5156.8 1165.03  5173.0 1165.00
  5178.7 1165.71  5194.9 1165.50  5211.2 1166.18  5222.6 1167.25  5232.8 1167.01
#Mann=3,-1,0
  4895.4    0.12       0  4983.4    0.05       0  4987.4    0.12       0
Bank Sta=4983.4,4987.4
Exp/Cntr=0.3,0.1

Type RM Length L Ch R = 1,5466,420,420,420
BEGIN DESCRIPTION:
Puter Creek 12.0
END DESCRIPTION:
XS GIS Cut Line= 3
      2161674.98     13885174.96      2161625.00     13885075.00
      2161574.98     13884974.97
#Sta/Elev= 30
  4888.2 1157.87  4896.5 1157.44  4902.1 1157.47  4910.5 1156.10  4918.9 1152.79
  4932.9 1146.20  4941.3 1143.06  4955.2 1138.45  4977.6 1131.91  4991.6 1128.68
  4997.2 1126.72  5002.8 1126.72  5008.3 1121.05  5011.9 1118.85  5012.2 1118.35
  5015.7 1118.35  5015.9 1118.85  5022.3 1127.23  5030.7 1134.95  5036.3 1135.65
  5044.7 1139.92  5053.1 1143.35  5058.7 1144.00  5067.0 1149.62  5075.4 1152.99
  5081.0 1155.90  5086.8 1156.19  5097.8 1156.59  5103.4 1157.04  5111.8 1157.19
#Mann=4,-1,0
  4888.2    0.12       0  5011.9    0.05       0  5015.9    0.12       0
  5086.8   0.035       0
Bank Sta=5011.9,5015.9
Exp/Cntr=0.3,0.1

Type RM Length L Ch R = 1,5046,479,479,479
BEGIN DESCRIPTION:
Puter Creek 11.0
END DESCRIPTION:
XS GIS Cut Line= 3
      2161975.00     13884974.97      2161975.00     13884875.00
      2161971.56     13884729.51
#Sta/Elev= 29
  4899.7 1131.25  4902.2 1131.25  4909.7 1130.71  4919.7 1129.75  4929.7 1124.85
  4933.7 1123.35  4949.7 1117.35  4959.7 1115.07  4969.7 1113.43  4977.7 1112.35
  4977.9 1111.85  4981.4 1111.85  4981.7 1112.35  4989.7 1127.39  4997.2 1129.82
  5002.2 1129.82  5009.7 1130.58  5019.7 1131.91  5029.7 1133.39  5039.7 1134.37
  5049.7 1135.19  5059.7 1136.15  5069.7 1136.84  5079.7 1138.04  5089.7 1138.74
  5109.7 1141.64  5129.7 1144.71  5139.7 1146.42  5145.2 1146.97
#Mann=4,-1,0
  4899.7    0.07       0  4933.7    0.12       0  4977.7    0.05       0
  4981.7    0.12       0
Bank Sta=4977.7,4981.7
Exp/Cntr=0.3,0.1

Type RM Length L Ch R = 1,4567,487,487,487
BEGIN DESCRIPTION:
Puter Creek 10.0
END DESCRIPTION:
XS GIS Cut Line= 3
      2162425.02     13884825.04      2162375.00     13884725.00
      2162282.46     13884649.16
#Sta/Elev= 30
  4888.1 1131.15  4890.9 1131.15  4896.5 1129.76  4902.1 1129.75  4910.5 1128.68
  4918.9 1126.21  4924.5 1122.54  4932.9 1115.08  4941.3 1109.16  4946.8 1109.91
  4963.6 1108.19  4977.6 1108.20  4991.6 1107.15  4997.2 1105.79  5007.1 1105.55
  5011.6 1103.74  5011.8 1103.24  5015.3 1103.24  5015.6 1103.74  5021.5 1104.86
  5027.9 1108.11  5035.8 1110.74  5042.3 1116.02  5050.2 1116.95  5056.7 1120.13
  5071.0 1122.77  5077.5 1124.48  5099.7 1127.57  5114.1 1128.20  5119.6 1127.82
#Mann=3,-1,0
  4888.1    0.12       0  5011.6    0.05       0  5015.6    0.12       0
Bank Sta=5011.6,5015.6
Exp/Cntr=0.3,0.1

Type RM Length L Ch R = 1,4080,458,458,458
BEGIN DESCRIPTION:
Puter Creek 9.0
END DESCRIPTION:
XS GIS Cut Line= 3
      2162775.00     13885124.99      2162825.00     13884825.00
      2162775.01     13884675.04
#Sta/Elev= 30
  4699.8 1144.70  4732.7 1142.97  4750.5 1137.51  4760.6 1135.16  4780.9 1131.88
  4801.2 1126.62  4831.6 1113.48  4862.0 1103.48  4882.3 1099.52  4892.4 1098.26
  4910.1 1098.87  4913.1 1097.09  4913.3 1096.59  4917.1 1096.59  4917.4 1097.09
  4922.8 1099.39  4943.1 1100.39  4965.2 1100.35  4976.0 1100.04  4993.8 1097.50
  5006.6 1097.71  5025.0 1104.00  5035.5 1108.59  5056.6 1114.52  5067.2 1118.97
  5088.3 1125.80  5098.8 1126.93  5109.3 1127.11  5141.0 1132.61  5162.0 1133.43
#Mann=4,-1,0
  4699.8    0.12       0  4913.1   0.035       0  4917.4    0.12       0
  4965.2   0.035       0
Bank Sta=4913.1,4917.4
Exp/Cntr=0.3,0.1

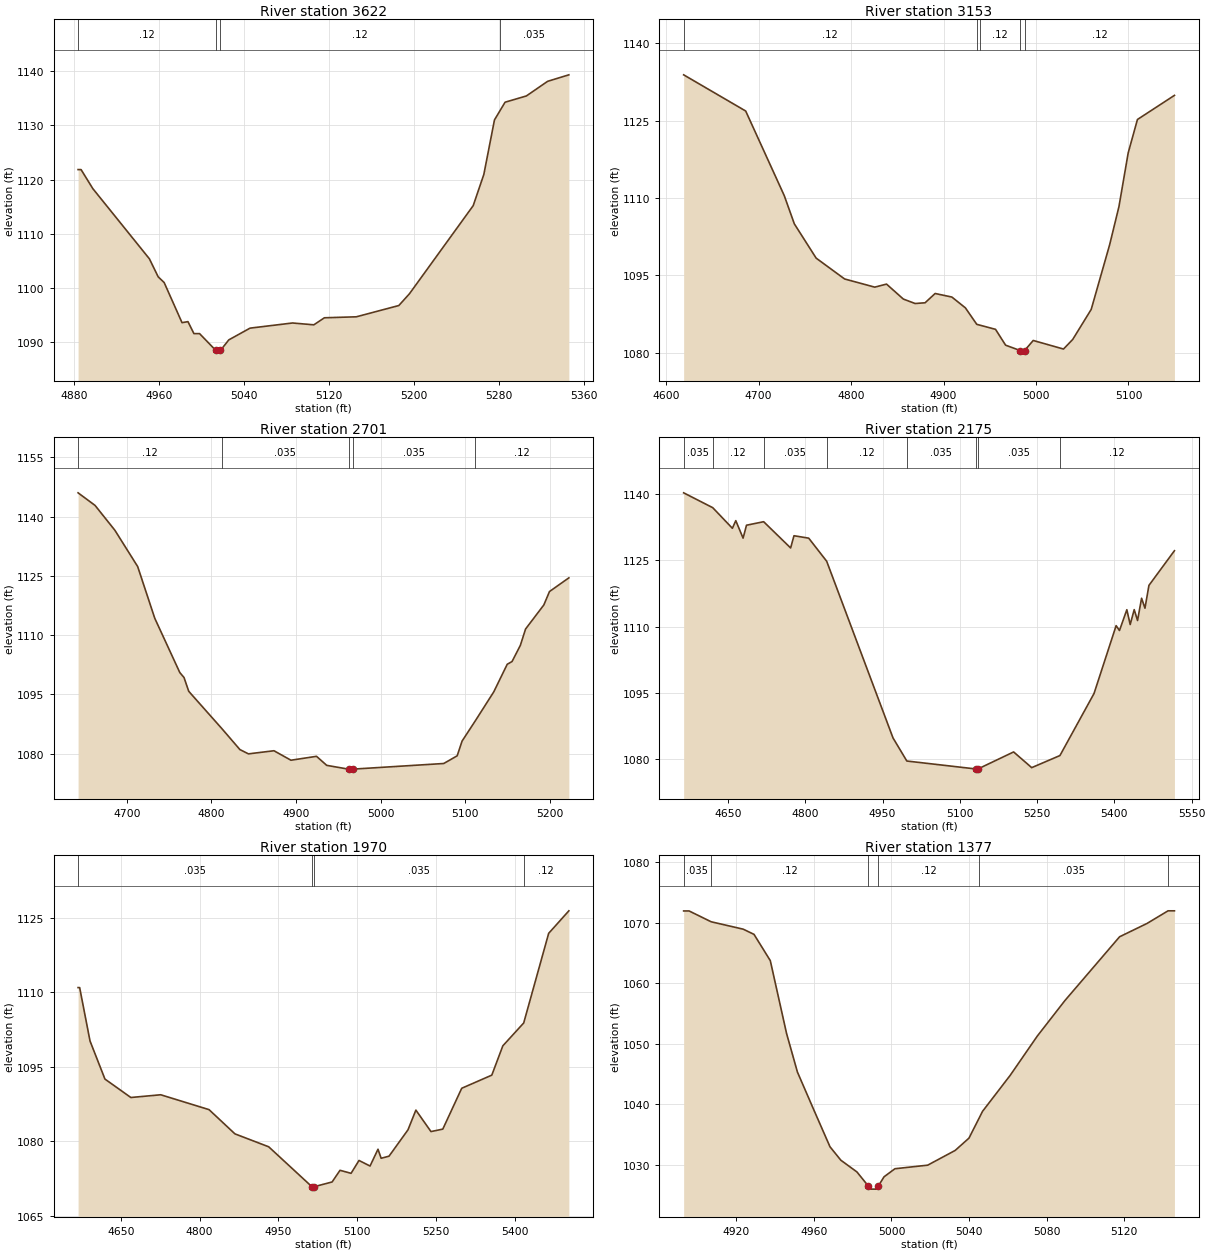
Type RM Length L Ch R = 1,3622,469,469,469
BEGIN DESCRIPTION:
Puter Creek 8.0
END DESCRIPTION:
XS GIS Cut Line= 3
      2163175.01     13885024.97      2163225.00     13884925.00
      2163225.00     13884574.97
#Sta/Elev= 30
  4883.7 1121.84  4886.5 1121.84  4897.6 1118.32  4950.8 1105.38  4959.1 1102.05
  4964.7 1101.00  4981.5 1093.60  4987.1 1093.79  4992.7 1091.58  4998.0 1091.58
  5013.3 1088.48  5013.6 1087.98  5017.4 1087.98  5017.7 1088.48  5025.5 1090.42
  5045.5 1092.59  5085.5 1093.54  5105.5 1093.20  5115.5 1094.50  5145.5 1094.68
  5185.5 1096.76  5195.5 1098.93  5255.5 1115.19  5265.5 1120.95  5275.5 1131.00
  5280.5 1132.64  5285.5 1134.27  5305.5 1135.42  5325.5 1138.12  5345.5 1139.32
#Mann=4,-1,0
  4883.7    0.12       0  5013.3    0.05       0  5017.7    0.12       0
  5280.5   0.035       0
Bank Sta=5013.3,5017.7
Exp/Cntr=0.3,0.1

Type RM Length L Ch R = 1,3153,452,452,452
BEGIN DESCRIPTION:
Puter Creek 7.0
END DESCRIPTION:
XS GIS Cut Line= 3
      2163474.99     13885175.02      2163625.00     13884825.00
      2163625.00     13884675.01
#Sta/Elev= 30
  4618.9 1133.85  4686.0 1126.84  4727.7 1110.46  4738.6 1104.99  4762.2 1098.35
  4793.0 1094.31  4825.6 1092.73  4838.3 1093.32  4856.5 1090.42  4869.2 1089.56
  4880.0 1089.70  4890.9 1091.50  4909.0 1090.81  4923.6 1088.72  4935.9 1085.53
  4939.6 1085.35  4956.2 1084.56  4967.1 1081.49  4982.9 1080.45  4983.2 1079.95
  4987.6 1080.45  4997.0 1082.40  5029.7 1080.74  5039.7 1082.60  5059.7 1088.42
  5079.7 1100.99  5089.7 1108.34  5099.7 1118.74  5109.7 1125.20  5149.7 1129.87
#Mann=5,-1,0
  4618.9    0.12       0  4935.9   0.035       0  4939.6    0.12       0
  4982.9    0.05       0  4987.6    0.12       0
Bank Sta=4982.9,4987.6
Exp/Cntr=0.3,0.1

Type RM Length L Ch R = 1,2701,526,526,526
BEGIN DESCRIPTION:
Puter Creek 6.0
END DESCRIPTION:
XS GIS Cut Line= 3
      2163975.00     13885225.00      2163931.18     13884863.16
      2163825.02     13884675.03
#Sta/Elev= 30
  4642.2 1146.04  4662.3 1142.85  4685.7 1136.57  4712.7 1127.37  4732.9 1114.28
  4762.5 1100.54  4767.5 1099.27  4773.1 1095.78  4812.2 1086.35  4833.6 1081.03
  4843.7 1079.94  4873.9 1080.73  4894.0 1078.33  4924.2 1079.32  4936.3 1077.03
  4962.1 1076.07  4962.5 1075.57  4966.9 1076.07  5074.7 1077.50  5090.6 1079.45
  5096.4 1083.18  5111.9 1088.26  5133.9 1095.65  5149.8 1102.63  5155.5 1103.32
  5165.3 1107.41  5171.5 1111.56  5193.1 1117.65  5199.8 1121.05  5222.7 1124.51
#Mann=5,-1,0
  4642.2    0.12       0  4812.2   0.035       0  4962.1   0.035       0
  4966.9   0.035       0  5111.9    0.12       0
Bank Sta=4962.1,4966.9
Exp/Cntr=0.3,0.1

Type RM Length L Ch R = 1,2175,205,205,205
BEGIN DESCRIPTION:
Puter Creek 5.0
END DESCRIPTION:
XS GIS Cut Line= 3
      2164665.59     13885147.05      2164368.68     13884799.36
      2163989.13     13884480.70
#Sta/Elev= 30
  4563.8 1140.34  4620.3 1136.97  4658.4 1132.30  4665.0 1134.03  4679.2 1130.07
  4685.8 1132.99  4719.1 1133.79  4771.5 1127.84  4778.0 1130.61  4806.6 1130.06
  4841.5 1124.82  4970.2 1084.77  4997.1 1079.52  5130.4 1077.73  5130.7 1077.23
  5135.3 1077.73  5204.4 1081.58  5239.5 1078.02  5294.3 1080.76  5360.5 1094.83
  5403.4 1110.22  5409.9 1109.12  5424.2 1113.83  5430.7 1110.47  5438.5 1113.85
  5445.0 1111.39  5452.8 1116.44  5459.4 1114.18  5467.1 1119.35  5516.6 1127.21
#Mann=8,-1,0
  4563.8   0.035       0  4620.3    0.12       0  4719.1   0.035       0
  4841.5    0.12       0  4997.1   0.035       0  5130.4   0.035       0
  5135.3   0.035       0  5294.3    0.12       0
Bank Sta=5130.4,5135.3
Exp/Cntr=0.3,0.1

Type RM Length L Ch R = 1,1970,593,593,593
BEGIN DESCRIPTION:
Puter Creek 4.0
END DESCRIPTION:
XS GIS Cut Line= 3
      2164794.44     13884937.36      2164474.15     13884647.02
      2164056.45     13884369.85
#Sta/Elev= 30
  4568.8 1110.92  4571.8 1110.92  4591.5 1100.18  4619.9 1092.51  4669.2 1088.80
  4726.0 1089.35  4817.9 1086.36  4867.2 1081.48  4931.4 1078.88  5013.5 1070.86
  5013.8 1070.36  5018.4 1070.86  5052.0 1071.80  5067.1 1074.15  5088.1 1073.54
  5103.2 1076.13  5124.2 1075.01  5139.3 1078.39  5145.3 1076.57  5160.3 1076.99
  5196.4 1082.30  5211.4 1086.26  5240.1 1081.94  5262.6 1082.44  5298.6 1090.66
  5355.8 1093.30  5376.8 1099.20  5416.5 1103.80  5464.0 1121.84  5502.4 1126.37
#Mann=4,-1,0
  4568.8   0.035       0  5013.5   0.035       0  5018.4   0.035       0
  5416.5    0.12       0
Bank Sta=5013.5,5018.4
Exp/Cntr=0.3,0.1

Type RM Length L Ch R = 1,1377,444,444,444
BEGIN DESCRIPTION:
Puter Creek 3.0
END DESCRIPTION:
XS GIS Cut Line= 3
      2164925.00     13884425.00      2164875.00     13884325.00
      2164775.02     13884225.02
#Sta/Elev= 30
  4892.8 1071.94  4895.6 1071.94  4907.0 1070.15  4923.5 1068.93  4929.1 1068.07
  4937.5 1063.73  4945.9 1051.68  4951.5 1045.31  4959.9 1039.10  4968.3 1032.96
  4973.9 1030.74  4982.2 1028.80  4988.1 1026.46  4988.4 1025.96  4992.8 1025.96
  4993.2 1026.46  4996.2 1028.00  5001.8 1029.33  5018.7 1029.92  5032.9 1032.36
  5040.0 1034.39  5045.3 1037.74  5047.0 1038.82  5061.2 1044.74  5075.3 1051.28
  5089.5 1057.13  5117.7 1067.67  5131.9 1069.88  5142.7 1071.96  5146.0 1071.96
#Mann=6,-1,0
  4892.8   0.035       0  4907.0    0.12       0  4988.1    0.05       0
  4993.2    0.12       0  5045.3   0.035       0  5142.7    0.12       0
Bank Sta=4988.1,4993.2
Exp/Cntr=0.3,0.1

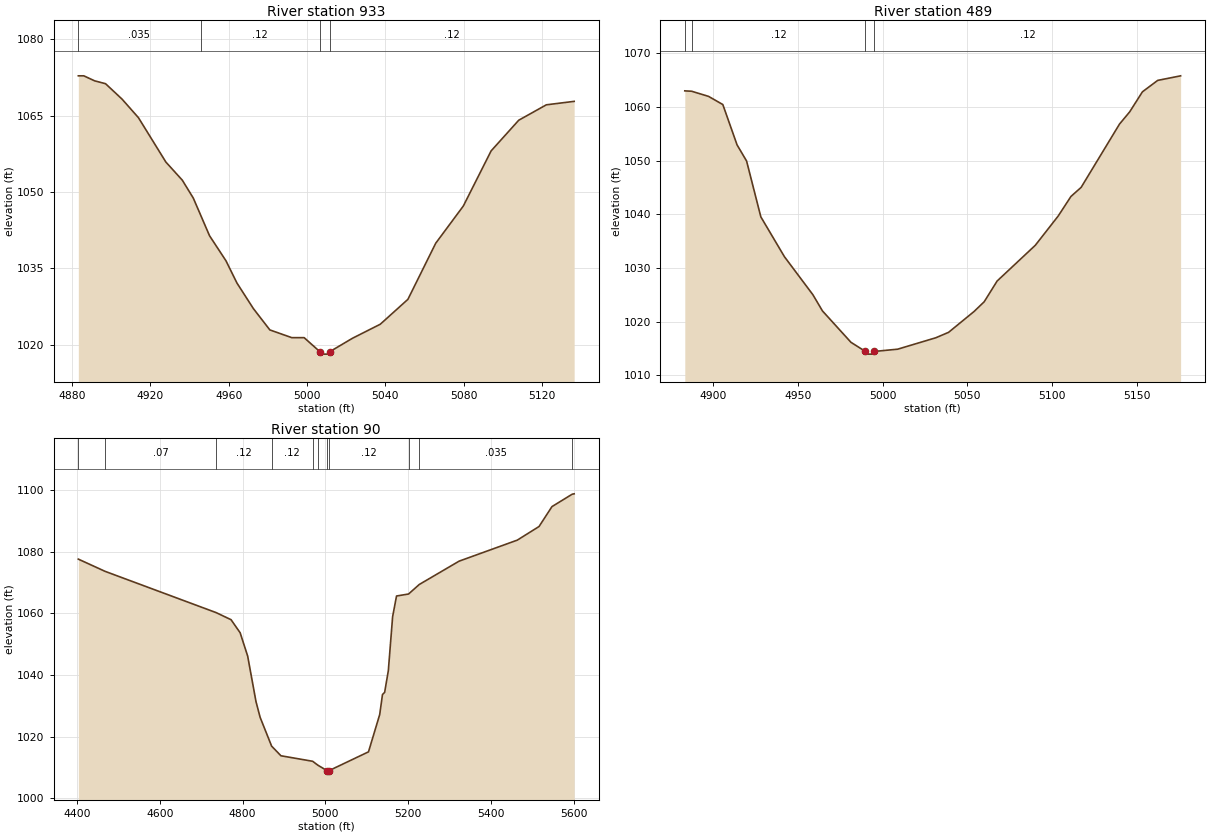
Type RM Length L Ch R = 1,933,444,444,444
BEGIN DESCRIPTION:
Puter Creek 2.0
END DESCRIPTION:
XS GIS Cut Line= 3
      2165274.98     13884174.96      2165225.00     13884075.00
      2165124.99     13883974.99
#Sta/Elev= 30
  4883.2 1072.84  4886.0 1072.84  4891.5 1071.86  4897.1 1071.29  4905.5 1068.27
  4913.9 1064.61  4927.9 1055.89  4936.3 1052.32  4941.9 1048.81  4945.6 1045.51
  4950.2 1041.40  4958.6 1036.47  4964.2 1032.10  4972.6 1027.07  4981.0 1022.88
  4992.2 1021.36  4998.5 1021.36  5006.5 1018.62  5006.9 1018.12  5011.3 1018.12
  5011.7 1018.62  5023.2 1021.24  5037.4 1024.00  5051.5 1028.89  5065.7 1039.92
  5079.8 1047.24  5094.0 1058.08  5108.1 1064.11  5122.2 1067.14  5136.4 1067.82
#Mann=4,-1,0
  4883.2   0.035       0  4945.6    0.12       0  5006.5    0.05       0
  5011.7    0.12       0
Bank Sta=5006.5,5011.7
Exp/Cntr=0.3,0.1

Type RM Length L Ch R = 1,489,399,399,399
BEGIN DESCRIPTION:
Puter Creek 1.0
END DESCRIPTION:
XS GIS Cut Line= 3
      2165625.04     13883825.02      2165525.00     13883775.00
      2165375.02     13883675.01
#Sta/Elev= 30
  4883.5 1063.02  4887.5 1062.95  4897.5 1061.99  4905.9 1060.47  4914.3 1052.95
  4919.9 1049.95  4928.3 1039.54  4942.2 1032.12  4959.0 1025.02  4964.6 1022.02
  4981.4 1016.17  4989.9 1014.47  4990.4 1013.97  4994.8 1013.97  4995.2 1014.47
  5008.9 1014.89  5031.4 1017.02  5038.9 1018.03  5053.9 1021.91  5059.9 1023.73
  5067.5 1027.59  5090.0 1034.25  5103.5 1039.71  5111.0 1043.35  5117.0 1045.04
  5139.6 1056.83  5145.6 1059.11  5153.1 1062.84  5162.1 1064.97  5175.6 1065.82
#Mann=4,-1,0
  4883.5    0.07       0  4887.5    0.12       0  4989.9    0.05       0
  4995.2    0.12       0
Bank Sta=4989.9,4995.2
Exp/Cntr=0.3,0.1

Type RM Length L Ch R = 1,90,0,0,0
BEGIN DESCRIPTION:
Puter Creek 0.1
END DESCRIPTION:
XS GIS Cut Line= 3
      2165764.85     13884032.23      2165711.22     13883438.15
      2165133.45     13883273.77
#Sta/Elev= 30
  4403.5 1077.62  4468.0 1073.66  4736.1 1060.27  4772.2 1057.97  4794.2 1053.73
  4812.4 1046.15  4832.5 1031.37  4842.5 1026.27  4870.2 1016.94  4892.7 1013.81
  4969.3 1012.02  4981.9 1010.75  5003.8 1009.00  5004.2 1008.50  5009.1 1009.00
  5104.1 1015.08  5131.2 1027.19  5137.9 1033.68  5143.1 1034.38  5152.0 1041.41
  5162.4 1058.96  5171.8 1065.65  5200.9 1066.30  5226.6 1069.38  5322.9 1076.96
  5463.5 1083.79  5515.9 1088.20  5547.1 1094.66  5596.0 1098.69  5600.7 1098.81
#Mann=11,-1,0
  4403.5   0.035       0  4468.0    0.07       0  4736.1    0.12       0
  4870.2    0.12       0  4969.3    0.12       0  4981.9    0.12       0
  5003.8    0.05       0  5009.1    0.12       0  5200.9    0.12       0
  5226.6   0.035       0  5596.0    0.12       0
Bank Sta=5003.8,5009.1
Exp/Cntr=0.3,0.1

Chan Stop Cuts=-1