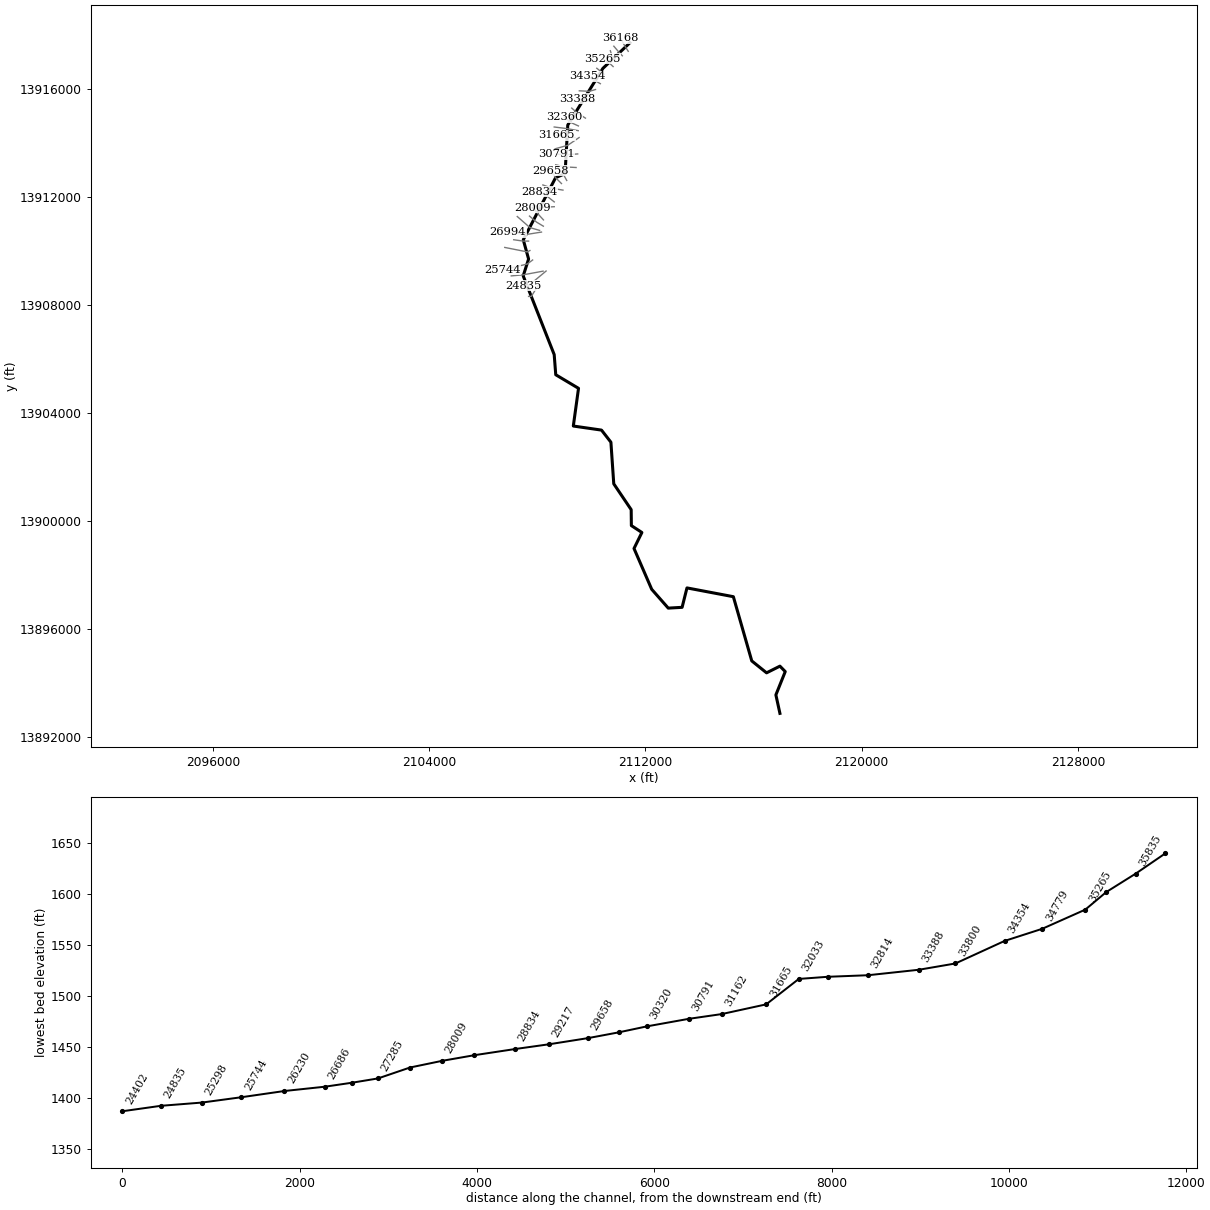
--- RAWLS CREEK.prj (project) ---

Proj Title=RAWLS CREEK Base Level Engineering
Current Plan=p01
Default Exp/Contr=0.3,0.1
English Units
Geom File=g01
Flow File=f01
Plan File=p01
Y Axis Title=Elevation
X Axis Title(PF)=Main Channel Distance
X Axis Title(XS)=Station
BEGIN DESCRIPTION:
RAWLS CREEK
END DESCRIPTION:
DSS Export Rating Curves= 0
DSS Export Rating Curve Sorted= 0
DSS Export Volume Flow Curves= 0
DXF OffsetX= 0
DXF OffsetY= 0
DXF ScaleX= 1
DXF ScaleY= 10

--- RAWLS CREEK.p01 (plan) ---

Plan Title=Multiple Run
Short Identifier=Multiple
Geom File=g01
Flow File=f01
Subcritical Flow
K Sum by GR= 0
Std Step Tol= 0.01
Critical Tol= 0.01
Num of Std Step Trials= 20
Max Error Tol= 0.3
Flow Tol Ratio= 0.001
Split Flow NTrial= 30
Split Flow Tol= 0.02
Split Flow Ratio= 0.02
Log Output Level= 0
Friction Slope Method= 1
Unsteady Friction Slope Method= 2
Unsteady Bridges Friction Slope Method= 1
Parabolic Critical Depth
Global Vel Dist=  1 , 1 , 1
Global Log Level= 0
CheckData=True
Encroach Param= -1, 0, 0, 0
BEGIN DESCRIPTION:
Multiple Run
END DESCRIPTION:

--- RAWLS CREEK.f01 (steady flow) ---

Flow Title=Multiple
Number of Profiles=7
Profile Names=10-year,25-year,50-year,1pct_min,100-year,1pct_plu,500-year
River Rch & RM= RAWLS CREEK,Reach-1,36168
     814    1383    1929    1311    2617    5221    4758
River Rch & RM= RAWLS CREEK,Reach-1,32360
    1626    2865    4092    2837    5661   11294   10733
River Rch & RM= RAWLS CREEK,Reach-1,26686
    2594    4640    6692    4668    9315   18585   17864
River Rch & RM= RAWLS CREEK,Reach-1,20215
    3773    6857    9993    7035   14037   28008   27426
River Rch & RM= RAWLS CREEK,Reach-1,15636
    5334    9806   14399   10200   20352   40608   40270
River Rch & RM= RAWLS CREEK,Reach-1,10218
    5278    9676   14181   10025   20003   39911   39415
River Rch & RM= RAWLS CREEK,Reach-1,6512
    6158   11334   16655   11798   23540   46969   46574
River Rch & RM= RAWLS CREEK,Reach-1,1781
    6607   12181   17920   12705   25350   50581   50243
Boundary for River Rch & Prof#=RAWLS CREEK,Reach-1,1
Up Type=0
Dn Type=3
Dn Slope=0.005
Boundary for River Rch & Prof#=RAWLS CREEK,Reach-1,2
Up Type=0
Dn Type=3
Dn Slope=0.005
Boundary for River Rch & Prof#=RAWLS CREEK,Reach-1,3
Up Type=0
Dn Type=3
Dn Slope=0.005
Boundary for River Rch & Prof#=RAWLS CREEK,Reach-1,4
Up Type=0
Dn Type=3
Dn Slope=0.005
Boundary for River Rch & Prof#=RAWLS CREEK,Reach-1,5
Up Type=0
Dn Type=3
Dn Slope=0.005
Boundary for River Rch & Prof#=RAWLS CREEK,Reach-1,6
Up Type=0
Dn Type=3
Dn Slope=0.005
Boundary for River Rch & Prof#=RAWLS CREEK,Reach-1,7
Up Type=0
Dn Type=3
Dn Slope=0.005

--- RAWLS CREEK.g01 (geometry) ---

Geom Title=Existing Conditions
Program Version=4.10

River Reach=RAWLS CREEK     ,Reach-1
Reach XY= 30
        2111425.       13917725.        2110425.       13916775.
        2109125.       13914675.        2109025.       13912875.
        2108675.       13912725.      2107478.54     13910423.54
      2107675.44     13909711.18      2107476.09     13909085.54
      2108622.64     13906169.48      2108680.52     13905422.57
      2109522.92     13904919.52      2109330.34     13903522.26
       2110373.5     13903371.39      2110721.17     13902923.42
      2110826.98     13901380.62      2111471.46     13900423.54
      2111478.21     13899832.99       2111867.5     13899578.13
       2111576.2     13898984.59      2112230.83      13897472.7
      2112843.11     13896775.04       2113355.6     13896804.34
      2113535.43     13897523.95      2115251.88     13897198.73
      2115933.14     13894818.95      2116480.56     13894377.26
        2116975.       13894625.      2117171.84     13894423.35
      2116825.51     13893559.79        2116975.       13892875.

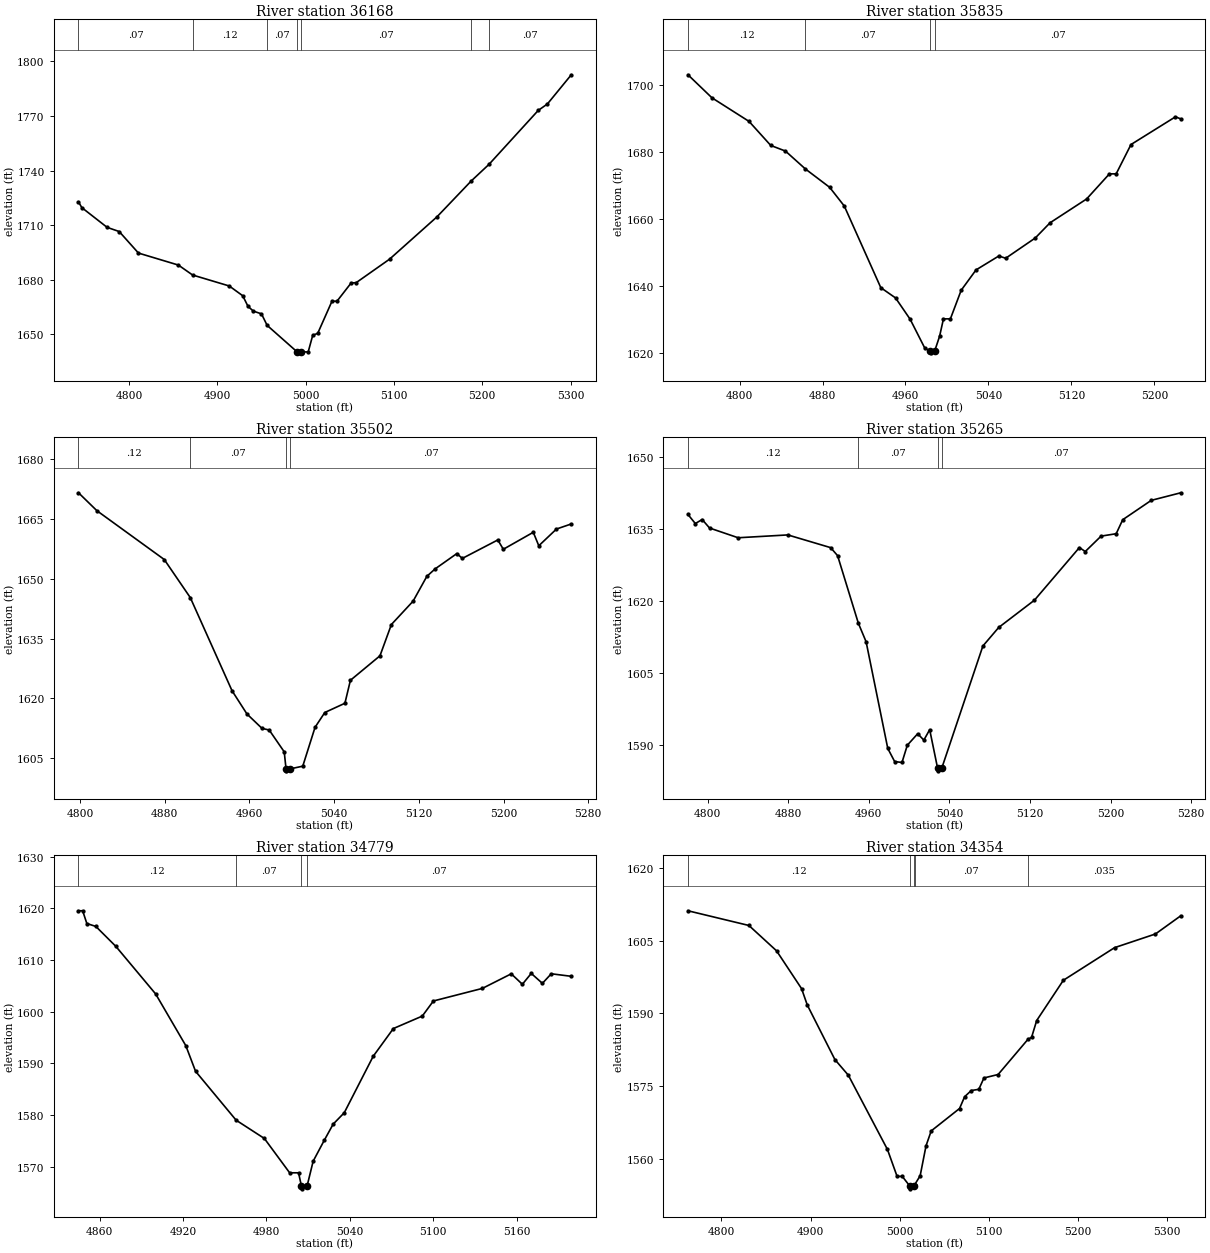
Type RM Length L Ch R = 1 ,36168   ,333,333,333
BEGIN DESCRIPTION:
RAWLS CREEK 80.0
END DESCRIPTION:
XS GIS Cut Line= 3
      2111362.54     13917407.66        2111225.       13917625.
      2111079.37      13917888.2
#Sta/Elev= 30
  4742.8 1722.74  4746.6 1719.58  4775.2 1708.75  4788.9 1706.45  4810.7 1694.61
  4855.9 1688.02    4872 1682.55  4913.5 1676.52  4928.8 1671.14  4934.7 1665.35
  4940.8  1662.7    4950 1661.19  4956.4 1654.87  4990.4 1640.27  4990.6 1639.77
  4994.4 1640.27  5002.9 1640.28    5008  1649.4  5013.7 1650.51  5029.8 1668.13
  5035.5 1668.16  5051.5 1678.17  5057.2 1678.34    5095 1691.25  5148.6 1714.48
  5187.3 1734.15  5207.7 1743.42  5263.4 1773.05  5273.7 1776.55  5300.8 1792.62
#Mann= 7 ,-1 , 0
  4742.8     .07       0    4872     .12       0  4956.4     .07       0
  4990.4     .05       0  4994.4     .07       0  5187.3    .035       0
  5207.7     .07       0
Bank Sta=4990.4,4994.4
XS Rating Curve= 0 ,0
Exp/Cntr=0.3,0.1

Type RM Length L Ch R = 1 ,35835   ,333,333,333
BEGIN DESCRIPTION:
RAWLS CREEK 79.0
END DESCRIPTION:
XS GIS Cut Line= 3
      2111143.79     13917240.99        2110975.       13917425.
      2110829.33       13917597.
#Sta/Elev= 30
  4750.3  1703.2  4773.4 1696.31  4809.2 1689.24  4830.1 1682.05  4844.3 1680.36
  4863.5 1675.01  4886.9 1669.51    4901 1663.91  4936.2 1639.48  4950.4 1636.41
  4964.5 1630.02  4978.7 1621.33  4984.1 1620.47  4984.4 1619.97  4988.1 1620.47
  4992.9 1624.95  4996.6 1630.14  5003.3 1630.14  5013.7  1638.7    5028 1644.79
    5050 1648.96  5056.6 1648.28  5085.1 1654.34  5099.4  1658.9  5134.6 1666.02
  5156.6 1673.54  5163.1 1673.54  5177.4 1682.32  5220.3 1690.62  5225.4 1689.99
#Mann= 4 ,-1 , 0
  4750.3     .12       0  4863.5     .07       0  4984.1     .05       0
  4988.1     .07       0
Bank Sta=4984.1,4988.1
XS Rating Curve= 0 ,0
Exp/Cntr=0.3,0.1

Type RM Length L Ch R = 1 ,35502   ,237,237,237
BEGIN DESCRIPTION:
RAWLS CREEK 78.0
END DESCRIPTION:
XS GIS Cut Line= 3
      2110922.46     13917037.83        2110775.       13917175.
       2110701.1     13917428.45
#Sta/Elev= 30
  4798.6 1671.57    4816 1667.07  4879.6 1654.83  4904.2 1645.27  4943.6 1621.92
  4957.7 1616.09  4971.9 1612.48  4978.7 1612.07  4992.9 1606.59  4994.6 1602.33
  4994.8 1601.83  4998.6 1602.33  5010.4    1603    5022 1612.75  5031.2 1616.46
  5050.2 1618.78  5055.4 1624.54  5083.3 1630.68  5094.1 1638.53  5114.6 1644.39
  5127.6 1650.62  5135.4 1652.48  5155.9 1656.32  5161.1 1655.11  5194.6 1659.74
  5199.8  1657.4  5228.1 1661.66  5233.3 1658.28    5250 1662.48    5264 1663.75
#Mann= 4 ,-1 , 0
  4798.6     .12       0  4904.2     .07       0  4994.6     .05       0
  4998.6     .07       0
Bank Sta=4994.6,4998.6
XS Rating Curve= 0 ,0
Exp/Cntr=0.3,0.1

Type RM Length L Ch R = 1 ,35265   ,486,486,486
BEGIN DESCRIPTION:
RAWLS CREEK 77.0
END DESCRIPTION:
XS GIS Cut Line= 3
      2110802.65     13916842.54      2110642.39     13916992.39
      2110409.73     13917128.81
#Sta/Elev= 30
  4780.6 1637.98  4787.9 1636.09  4794.7 1636.93    4802 1635.16  4830.4 1633.13
  4879.7 1633.72  4922.2 1631.07  4929.1  1629.4  4949.7 1615.32  4957.4 1611.46
  4978.9 1589.24  4985.7 1586.51    4993 1586.31  4998.3 1589.91  5008.6  1592.3
  5014.7 1590.97  5020.5 1593.15  5028.4 1585.07  5028.6 1584.57  5032.4 1585.07
  5073.3 1610.58    5089 1614.44  5124.5 1620.13  5169.1 1631.09  5174.9 1630.26
  5190.6 1633.47  5205.6 1633.97  5212.1 1636.89  5240.4 1640.92  5269.7  1642.5
#Mann= 4 ,-1 , 0
  4780.6     .12       0  4949.7     .07       0  5028.4     .05       0
  5032.4     .07       0
Bank Sta=5028.4,5032.4
XS Rating Curve= 0 ,0
Exp/Cntr=0.3,0.1

Type RM Length L Ch R = 1 ,34779   ,425,425,425
BEGIN DESCRIPTION:
RAWLS CREEK 76.0
END DESCRIPTION:
XS GIS Cut Line= 3
      2110474.55     13916556.06      2110354.89     13916654.89
      2110199.27      13916779.4
#Sta/Elev= 30
  4844.8 1619.51  4847.8 1619.51  4850.8 1617.05  4857.3 1616.48  4871.7 1612.62
  4900.3 1603.43    4922 1593.43    4929 1588.48  4958.2 1579.02  4978.5 1575.49
  4996.7 1568.85  5003.1 1568.85  5005.2 1566.25  5005.5 1565.75  5009.2 1566.25
  5013.6 1571.09  5021.6 1575.14    5028 1578.26    5036 1580.47  5056.8 1591.38
  5071.3 1596.74  5092.1 1599.15  5100.1 1602.07  5135.3  1604.5  5156.1 1607.32
  5164.1  1605.3  5170.5  1607.4  5178.5 1605.48  5184.9 1607.33  5199.3 1606.84
#Mann= 4 ,-1 , 0
  4844.8     .12       0  4958.2     .07       0  5005.2     .05       0
  5009.2     .07       0
Bank Sta=5005.2,5009.2
XS Rating Curve= 0 ,0
Exp/Cntr=0.3,0.1

Type RM Length L Ch R = 1 ,34354   ,554,554,554
BEGIN DESCRIPTION:
RAWLS CREEK 75.0
END DESCRIPTION:
XS GIS Cut Line= 3
      2110331.29     13916207.12        2110125.       13916325.
      2109850.27     13916480.13
#Sta/Elev= 30
  4762.4 1611.14  4830.8 1608.11  4861.8 1602.89  4889.9 1595.09  4896.3 1591.72
  4927.3 1580.47  4942.4 1577.24  4986.3 1561.93  4997.1 1556.39  5002.9 1556.39
  5011.7 1554.32  5011.9 1553.82  5015.7 1554.32  5016.7 1554.62    5023 1556.52
  5029.6  1562.7  5035.4 1565.76  5067.2 1570.38  5072.9 1572.81  5080.4 1574.09
  5088.8 1574.33  5094.6 1576.68  5110.5 1577.39  5144.2 1584.69    5148 1585.02
  5153.8 1588.52  5183.7 1596.81  5241.2 1603.54  5287.1 1606.36  5315.5 1610.11
#Mann= 5 ,-1 , 0
  4762.4     .12       0  5011.7     .05       0  5015.7     .12       0
  5016.7     .07       0  5144.2    .035       0
Bank Sta=5011.7,5015.7
XS Rating Curve= 0 ,0
Exp/Cntr=0.3,0.1

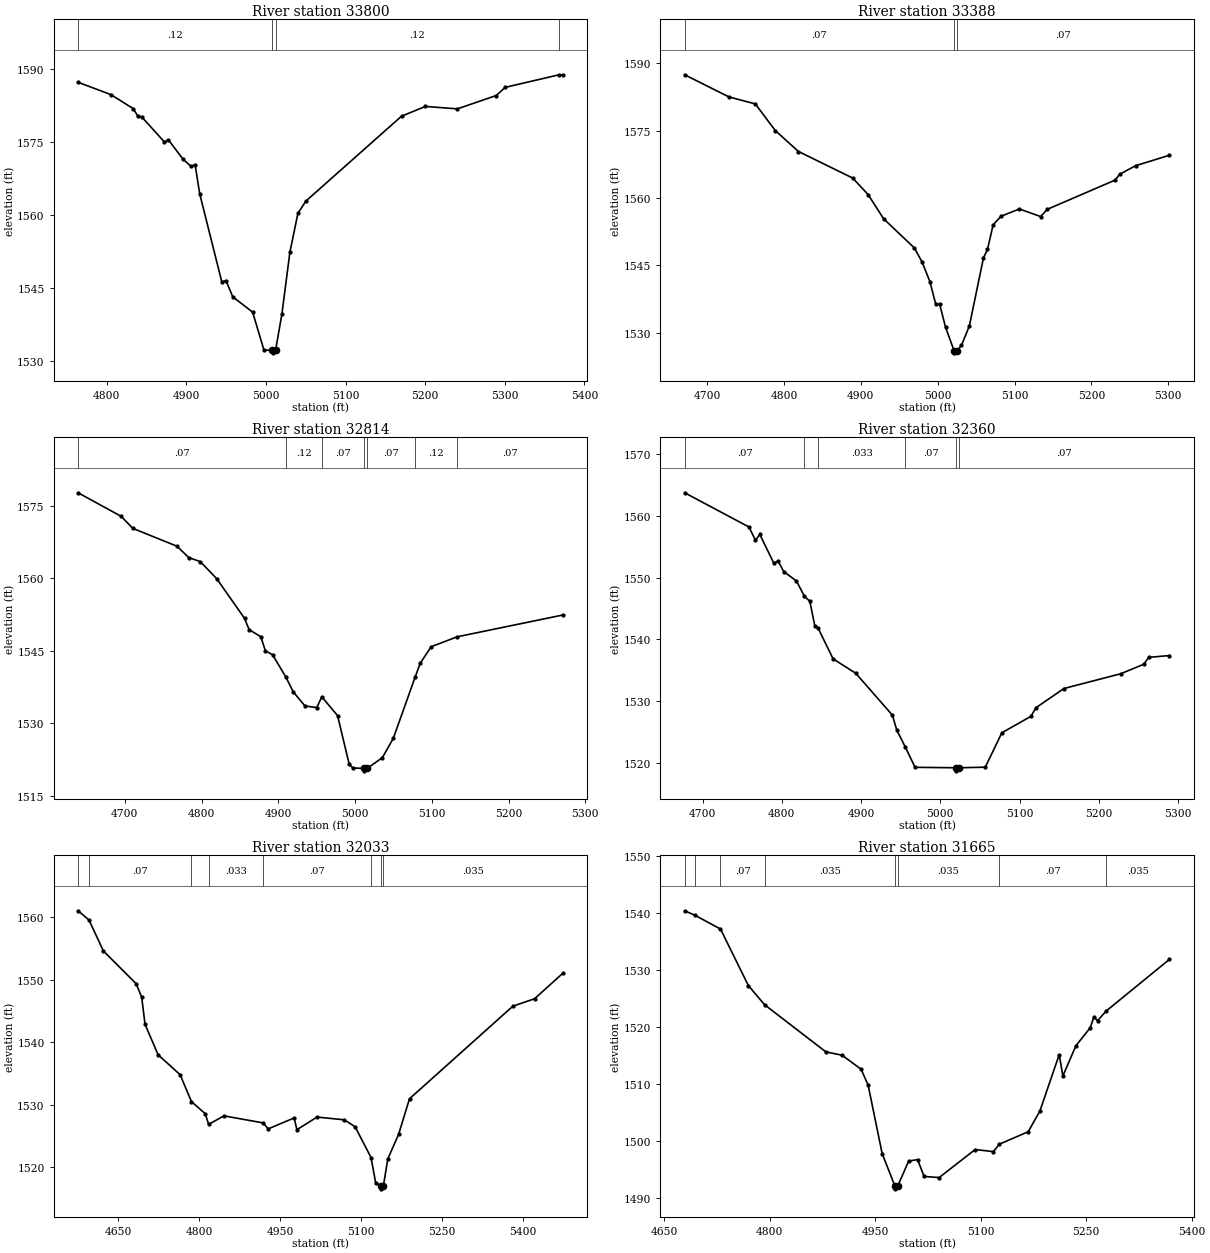
Type RM Length L Ch R = 1 ,33800   ,412,412,412
BEGIN DESCRIPTION:
RAWLS CREEK 74.0
END DESCRIPTION:
XS GIS Cut Line= 3
       2110151.6     13915990.96        2109925.       13915925.
      2109552.69     13915944.09
#Sta/Elev= 30
    4764 1587.21  4805.3 1584.68  4833.4 1581.79  4838.8 1580.32    4844  1580.1
  4872.3 1574.99  4877.5 1575.39  4895.8 1571.44  4905.8 1569.97    4911  1570.3
  4916.7 1564.37  4944.5 1546.27  4949.7 1546.55  4958.3 1543.21  4983.2 1540.08
  4997.4 1532.31    5008 1532.23  5008.3 1531.73    5012 1532.23    5020 1539.72
    5030 1552.36  5040.1 1560.36  5050.1 1562.85  5170.2 1580.26  5200.3 1582.26
  5240.3 1581.76  5289.2  1584.5  5300.4 1586.17  5368.1 1588.75  5372.8 1588.72
#Mann= 4 ,-1 , 0
    4764     .12       0    5008     .05       0    5012     .12       0
  5368.1     .07       0
Bank Sta=5008,5012
XS Rating Curve= 0 ,0
Exp/Cntr=0.3,0.1

Type RM Length L Ch R = 1 ,33388   ,574,574,574
BEGIN DESCRIPTION:
RAWLS CREEK 73.0
END DESCRIPTION:
XS GIS Cut Line= 3
      2110102.18     13915540.44        2109775.       13915575.
      2109482.38     13915647.21
#Sta/Elev= 30
    4671 1587.39  4728.5 1582.47  4762.9 1580.91  4788.8 1574.99    4819 1570.33
  4889.4 1564.44  4909.5 1560.77  4929.6  1555.4  4969.8 1548.87  4979.9  1545.7
  4989.9  1541.4  4997.5 1536.36  5002.6 1536.36  5010.3 1531.23  5021.3 1526.07
  5021.6 1525.57  5025.3 1526.07  5030.9 1527.21  5041.2 1531.55  5059.6  1546.7
  5064.8 1548.56  5072.1 1554.02  5082.4 1555.94  5106.3 1557.55  5133.9 1555.87
  5142.6 1557.48  5230.7 1563.97  5236.9  1565.3  5257.5 1567.18  5301.4  1569.5
#Mann= 3 ,-1 , 0
    4671     .07       0  5021.3     .05       0  5025.3     .07       0
Bank Sta=5021.3,5025.3
XS Rating Curve= 0 ,0
Exp/Cntr=0.3,0.1

Type RM Length L Ch R = 1 ,32814   ,454,454,454
BEGIN DESCRIPTION:
RAWLS CREEK 72.0
END DESCRIPTION:
XS GIS Cut Line= 3
      2109779.24     13914931.06        2109475.       13915125.
      2109271.44     13915303.44
#Sta/Elev= 30
  4639.2  1577.7  4695.3 1572.83  4710.6 1570.33  4768.1 1566.64  4783.3 1564.31
  4798.4 1563.46  4819.7 1559.95  4856.1 1551.71    4862  1549.4  4877.3 1547.92
  4883.2 1545.01  4892.5 1544.21  4909.6 1539.66  4919.6  1536.5  4934.8 1533.61
  4950.1 1533.27  4956.7 1535.49  4977.2 1531.62  4992.4 1521.55    4997 1520.79
  5011.8 1520.69    5012 1520.19  5015.8 1520.69  5035.6 1522.92  5049.8  1526.9
  5078.1  1539.5  5084.9 1542.45  5099.2 1545.86    5133 1547.91  5270.7 1552.42
#Mann= 7 ,-1 , 0
  4639.2     .07       0  4909.6     .12       0  4956.7     .07       0
  5011.8     .05       0  5015.8     .07       0  5078.1     .12       0
    5133     .07       0
Bank Sta=5011.8,5015.8
XS Rating Curve= 0 ,0
Exp/Cntr=0.3,0.1

Type RM Length L Ch R = 1 ,32360   ,327,327,327
BEGIN DESCRIPTION:
RAWLS CREEK 71.0
END DESCRIPTION:
XS GIS Cut Line= 3
       2109518.8     13914642.01        2109225.       13914775.
      2109000.59      13914957.1
#Sta/Elev= 30
  4677.5 1563.75  4758.5 1558.21  4766.8 1556.05  4772.3 1556.99  4789.9 1552.34
  4795.4 1552.68  4802.4 1550.97  4818.5 1549.45  4828.6 1546.95  4835.3 1546.17
  4841.6 1542.21    4846 1541.75  4864.7 1536.82  4893.3 1534.48  4939.5 1527.69
  4945.1 1525.25  4955.7 1522.55  4968.1 1519.23  5019.6 1519.16  5019.8 1518.66
  5023.6 1519.16  5056.7 1519.25  5077.6 1524.83  5114.2 1527.49  5120.7  1528.9
  5155.9 1532.01  5227.7 1534.41  5256.5 1535.94  5262.9 1537.06    5289 1537.36
#Mann= 6 ,-1 , 0
  4677.5     .07       0  4828.6     .12       0    4846    .033       0
  4955.7     .07       0  5019.6     .05       0  5023.6     .07       0
Bank Sta=5019.6,5023.6
XS Rating Curve= 0 ,0
Exp/Cntr=0.3,0.1

Type RM Length L Ch R = 1 ,32033   ,368,368,368
BEGIN DESCRIPTION:
RAWLS CREEK 70.0
END DESCRIPTION:
XS GIS Cut Line= 3
      2109510.99     13914467.53      2109093.69     13914543.69
        2108623.     13914602.94
#Sta/Elev= 30
  4575.8 1561.03  4596.1 1559.55  4622.6 1554.61  4683.5 1549.36  4693.7 1547.21
  4699.9 1542.87  4724.2 1537.99  4764.9 1534.82  4785.9 1530.52  4811.5 1528.58
  4817.8 1526.87  4846.2 1528.23  4918.6 1527.11  4928.2 1526.15  4976.4  1527.9
  4981.4 1526.02  5018.8 1528.04  5069.2  1527.6  5089.4 1526.48  5118.9 1521.55
  5127.6 1517.43  5137.8 1517.06    5138 1516.56  5141.8 1517.06  5149.9 1521.33
    5170 1525.29  5190.2 1530.97  5381.7 1545.77    5422 1546.96  5474.4 1551.04
#Mann= 8 ,-1 , 0
  4575.8    .035       0  4596.1     .07       0  4785.9     .12       0
  4817.8    .033       0  4918.6     .07       0  5118.9    .035       0
  5137.8     .05       0  5141.8    .035       0
Bank Sta=5137.8,5141.8
XS Rating Curve= 0 ,0
Exp/Cntr=0.3,0.1

Type RM Length L Ch R = 1 ,31665   ,503,503,503
BEGIN DESCRIPTION:
RAWLS CREEK 69.0
END DESCRIPTION:
XS GIS Cut Line= 3
      2109395.49     13914208.85        2109075.       13914225.
      2108714.97      13914302.6
#Sta/Elev= 30
  4679.1  1540.4  4693.9  1539.6    4730  1537.2  4769.7 1527.26  4792.7 1523.91
  4879.8 1515.64  4902.8 1515.05  4929.9  1512.6  4939.9 1509.81  4959.9 1497.76
    4978  1492.1  4978.2  1491.6    4982  1492.1  4997.5 1496.46  5010.2 1496.74
  5019.5 1493.77  5040.9 1493.58  5092.1  1498.5  5118.1 1498.13  5126.2 1499.42
  5167.5 1501.62  5184.1 1505.25  5211.6 1515.15  5216.8  1511.4  5235.3 1516.71
  5255.7 1519.87  5260.9 1521.76  5266.1 1521.11  5278.5 1522.82  5368.3 1531.87
#Mann= 8 ,-1 , 0
  4679.1     .07       0  4693.9    .035       0    4730     .07       0
  4792.7    .035       0    4978    .035       0    4982    .035       0
  5126.2     .07       0  5278.5    .035       0
Bank Sta=4978,4982
XS Rating Curve= 0 ,0
Exp/Cntr=0.3,0.1

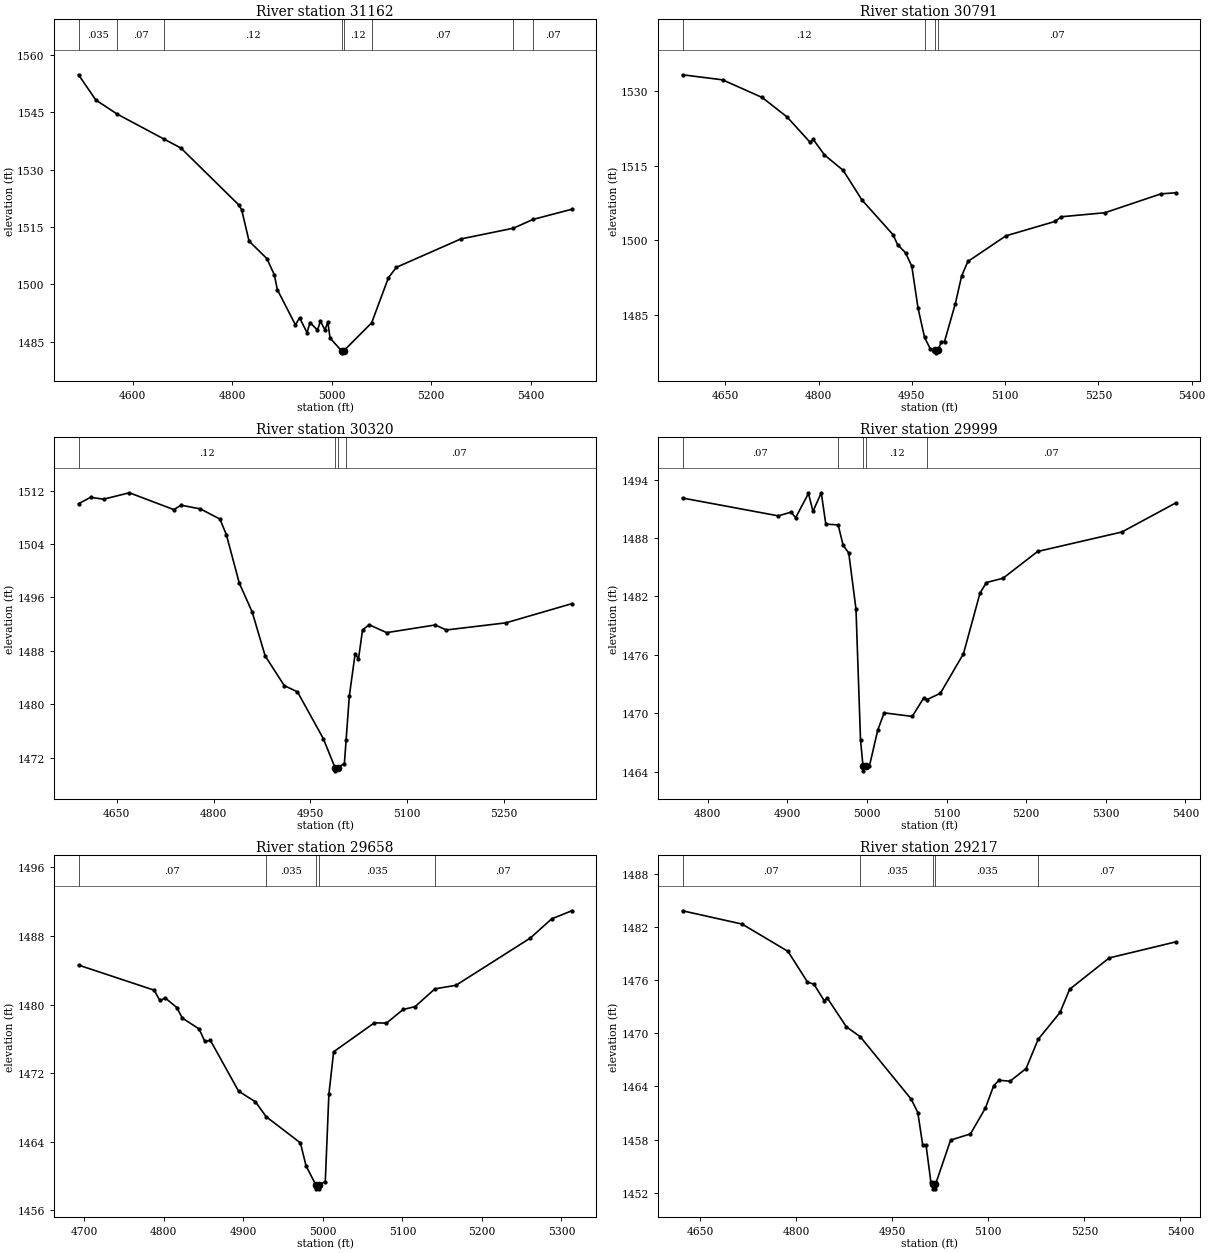
Type RM Length L Ch R = 1 ,31162   ,371,371,371
BEGIN DESCRIPTION:
RAWLS CREEK 68.0
END DESCRIPTION:
XS GIS Cut Line= 3
      2109544.81     13914212.29        2109125.       13913925.
      2108659.72     13913795.73
#Sta/Elev= 30
  4491.3 1554.78  4526.1 1548.18  4569.1 1544.49  4663.9 1537.91  4697.1 1535.62
  4813.1 1520.78  4819.2  1519.5  4834.1 1511.27    4870 1506.69  4884.9 1502.45
    4891 1498.56  4927.3 1489.36  4935.7  1491.2  4950.6 1487.34  4956.7 1489.96
  4971.6 1487.99  4977.6 1490.32  4986.5 1488.07  4992.5 1490.04    4997 1485.89
  5020.3 1482.54  5020.6 1482.04  5024.3 1482.54  5080.6  1489.9  5114.2 1501.66
  5130.2 1504.41  5259.5 1511.82  5365.3 1514.64  5405.2 1516.95  5482.9  1519.6
#Mann= 8 ,-1 , 0
  4491.3    .035       0  4569.1     .07       0  4663.9     .12       0
  5020.3     .05       0  5024.3     .12       0  5080.6     .07       0
  5365.3    .035       0  5405.2     .07       0
Bank Sta=5020.3,5024.3
XS Rating Curve= 0 ,0
Exp/Cntr=0.3,0.1

Type RM Length L Ch R = 1 ,30791   ,471,471,471
BEGIN DESCRIPTION:
RAWLS CREEK 67.0
END DESCRIPTION:
XS GIS Cut Line= 3
      2109492.75     13913604.68        2109075.       13913575.
       2108701.1     13913594.26
#Sta/Elev= 30
  4581.2 1533.35  4645.7 1532.33  4709.3 1528.78  4749.4 1524.85  4786.4 1519.75
  4791.4 1520.34  4809.5 1517.21  4839.6 1514.11  4869.7 1508.16  4919.8 1501.15
  4927.1 1499.14  4939.8 1497.53  4949.9 1494.82  4959.9  1486.4  4970.4 1480.49
  4979.9 1478.12    4988 1477.88  4988.2 1477.38    4992 1477.88  4997.5 1479.64
  5002.5 1479.64    5020 1487.31    5030 1492.85  5040.1 1495.77  5101.2 1500.93
  5180.2 1503.83  5190.3 1504.77  5260.3 1505.58  5350.5 1509.38  5374.4  1509.6
#Mann= 4 ,-1 , 0
  4581.2     .12       0  4970.4     .07       0    4988     .05       0
    4992     .07       0
Bank Sta=4988,4992
XS Rating Curve= 0 ,0
Exp/Cntr=0.3,0.1

Type RM Length L Ch R = 1 ,30320   ,321,321,321
BEGIN DESCRIPTION:
RAWLS CREEK 66.0
END DESCRIPTION:
XS GIS Cut Line= 3
      2109433.71     13913101.21        2109025.       13913125.
      2108678.35     13913201.56
#Sta/Elev= 30
  4590.6 1510.01  4609.3 1510.98  4629.4  1510.7  4669.4 1511.66  4738.2 1509.14
  4749.6  1509.8  4779.6 1509.24  4809.7 1507.72  4819.7 1505.38  4839.7 1498.14
  4859.8 1493.78  4879.8 1487.23  4909.4 1482.78  4929.9 1481.84  4969.9 1474.84
    4988 1470.51  4988.2 1470.01    4992 1470.51  5002.6  1471.1  5005.3 1474.68
  5010.2 1481.18  5019.3 1487.58  5024.4 1486.74  5030.7 1491.11    5041 1491.89
  5068.1 1490.71  5143.4 1491.86  5160.5 1491.11    5253 1492.18    5355 1495.05
#Mann= 4 ,-1 , 0
  4590.6     .12       0    4988     .05       0    4992     .12       0
  5005.3     .07       0
Bank Sta=4988,4992
XS Rating Curve= 0 ,0
Exp/Cntr=0.3,0.1

Type RM Length L Ch R = 1 ,29999   ,341,341,341
BEGIN DESCRIPTION:
RAWLS CREEK 65.0
END DESCRIPTION:
XS GIS Cut Line= 3
      2109086.53     13912622.02        2108975.       13912825.
      2108736.76     13913131.25
#Sta/Elev= 30
  4768.4 1492.11  4888.7 1490.28  4904.8 1490.66  4910.5 1490.09  4926.6 1492.58
  4932.3 1490.74  4942.7 1492.65  4948.4 1489.43  4963.9 1489.35  4970.2 1487.24
  4977.2 1486.47  4986.3  1480.7    4992 1467.26  4995.1 1464.58  4995.4 1464.08
  4999.1 1464.58  5003.2 1464.58  5013.6 1468.26  5021.7 1470.04    5057 1469.67
  5071.5 1471.59  5075.5  1471.4  5092.3 1472.05  5121.3 1476.11  5142.1 1482.35
  5150.2 1483.43    5171 1483.87  5214.5 1486.62  5320.3 1488.62    5388 1491.61
#Mann= 5 ,-1 , 0
  4768.4     .07       0  4963.9     .12       0  4995.1     .05       0
  4999.1     .12       0  5075.5     .07       0
Bank Sta=4995.1,4999.1
XS Rating Curve= 0 ,0
Exp/Cntr=0.3,0.1

Type RM Length L Ch R = 1 ,29658   ,441,441,441
BEGIN DESCRIPTION:
RAWLS CREEK 64.0
END DESCRIPTION:
XS GIS Cut Line= 3
      2108892.06     13912507.47        2108675.       13912725.
      2108503.18     13912986.62
#Sta/Elev= 30
  4692.7  1484.6  4787.9 1481.67  4794.9 1480.48    4802 1480.75  4816.2 1479.65
  4823.2 1478.42  4844.4 1477.15  4851.5  1475.7  4858.6 1475.81  4893.9 1469.91
  4915.2 1468.65  4928.7 1466.92  4971.7 1463.87  4978.8 1461.19  4990.9 1459.01
  4991.2 1458.51  4994.7 1458.51  4994.9 1459.01    5003 1459.35  5007.5 1469.51
  5013.5 1474.49  5064.8 1477.87  5079.9 1477.83  5100.9 1479.42    5116 1479.76
  5140.9 1481.83  5167.3 1482.24  5260.7 1487.74  5287.7 1489.99    5313 1490.93
#Mann= 5 ,-1 , 0
  4692.7     .07       0  4928.7    .035       0  4990.9    .035       0
  4994.9    .035       0  5140.9     .07       0
Bank Sta=4990.9,4994.9
XS Rating Curve= 0 ,0
Exp/Cntr=0.3,0.1

Type RM Length L Ch R = 1 ,29217   ,383,383,383
BEGIN DESCRIPTION:
RAWLS CREEK 63.0
END DESCRIPTION:
XS GIS Cut Line= 3
      2108947.61     13912264.41        2108575.       13912325.
      2108204.57     13912455.37
#Sta/Elev= 30
  4622.5 1483.82  4715.5 1482.32  4787.2 1479.24  4817.6 1475.78  4827.8 1475.53
  4843.6 1473.69  4848.7 1473.96  4878.4 1470.72    4900 1469.61  4979.7 1462.55
  4989.9 1461.05  4997.5  1457.4  5002.7  1457.4  5010.2 1453.26  5013.5 1452.94
  5013.7 1452.44  5017.2 1452.44  5017.5 1452.94  5041.1 1457.94  5072.1 1458.64
  5095.4 1461.55  5108.4 1464.08  5116.6 1464.69    5134 1464.59    5159 1466.02
  5177.8 1469.31    5212 1472.35  5226.9 1474.96  5288.8  1478.5  5392.7 1480.31
#Mann= 5 ,-1 , 0
  4622.5     .07       0    4900    .035       0  5013.5    .035       0
  5017.5    .035       0  5177.8     .07       0
Bank Sta=5013.5,5017.5
XS Rating Curve= 0 ,0
Exp/Cntr=0.3,0.1

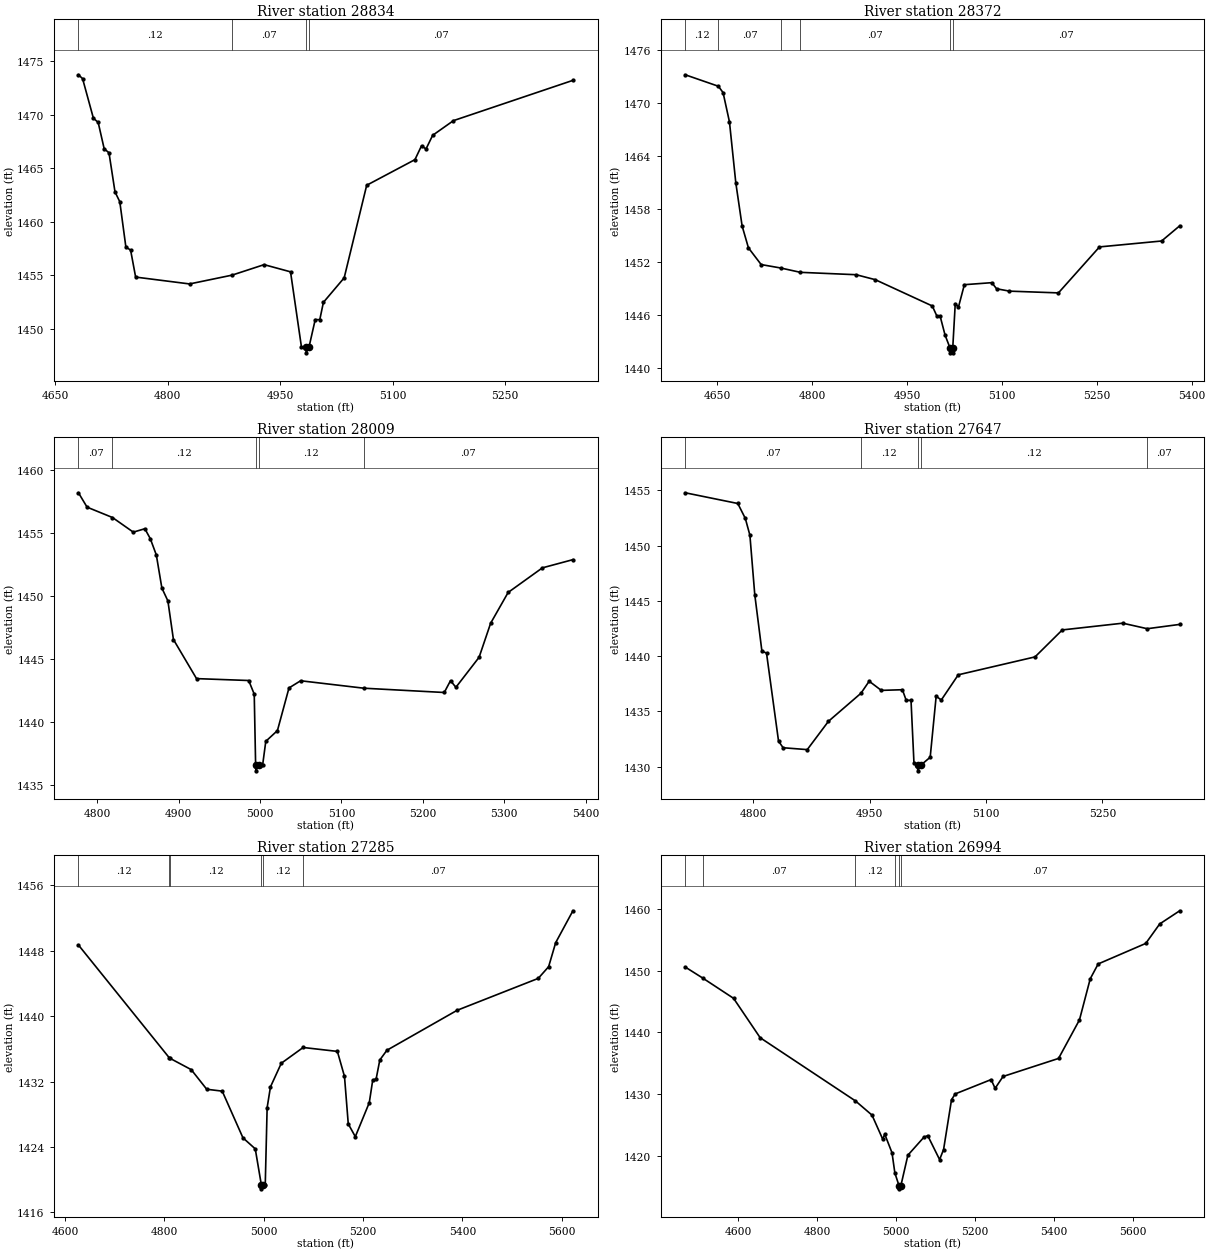
Type RM Length L Ch R = 1 ,28834   ,462,462,462
BEGIN DESCRIPTION:
RAWLS CREEK 62.0
END DESCRIPTION:
XS GIS Cut Line= 3
      2108624.68     13911826.93        2108375.       13912025.
      2108086.54     13912205.36
#Sta/Elev= 30
  4681.3 1473.72  4686.8 1473.36  4701.2 1469.67  4707.6 1469.27  4715.6 1466.81
    4722 1466.44    4730 1462.79  4736.4 1461.87  4744.5 1457.64  4750.8 1457.36
  4757.5 1454.84  4829.4  1454.2  4885.9 1455.02  4928.7    1456  4963.9 1455.33
  4978.4 1448.34  4984.4 1448.27  4984.7 1447.77  4988.4 1448.27  4996.8 1450.87
  5002.9 1450.87  5007.7 1452.48  5035.4 1454.77  5065.4 1463.41  5129.7  1465.8
  5138.5  1467.1  5144.4 1466.79  5153.3 1468.07    5181 1469.44  5340.2  1473.2
#Mann= 4 ,-1 , 0
  4681.3     .12       0  4885.9     .07       0  4984.4     .05       0
  4988.4     .07       0
Bank Sta=4984.4,4988.4
XS Rating Curve= 0 ,0
Exp/Cntr=0.3,0.1

Type RM Length L Ch R = 1 ,28372   ,363,363,363
BEGIN DESCRIPTION:
RAWLS CREEK 61.0
END DESCRIPTION:
XS GIS Cut Line= 3
      2108624.73     13911649.82        2108225.       13911625.
      2107850.38     13911694.96
#Sta/Elev= 30
  4599.5 1473.19  4651.9 1471.89  4659.3 1471.17  4669.4 1467.85  4679.4 1460.96
  4689.4 1456.06  4699.4 1453.58  4719.5 1451.69  4750.5  1451.3  4781.5 1450.81
  4869.7 1450.54  4899.8 1449.98    4990    1447  4997.5 1445.82  5002.5 1445.82
  5010.2  1443.7  5018.3 1442.19  5018.6 1441.69  5022.1 1441.69  5022.3 1442.19
  5026.3 1447.26  5031.4 1446.88  5040.7 1449.41  5084.1 1449.64  5091.6 1448.95
  5111.9 1448.68  5189.4 1448.48  5254.3 1453.69  5352.5 1454.36  5381.1 1456.08
#Mann= 6 ,-1 , 0
  4599.5     .12       0  4651.9     .07       0  4750.5     .12       0
  4781.5     .07       0  5018.3     .05       0  5022.3     .07       0
Bank Sta=5018.3,5022.3
XS Rating Curve= 0 ,0
Exp/Cntr=0.3,0.1

Type RM Length L Ch R = 1 ,28009   ,362,362,362
BEGIN DESCRIPTION:
RAWLS CREEK 60.0
END DESCRIPTION:
XS GIS Cut Line= 3
      2108225.41     13911160.23        2108075.       13911325.
      2107822.63     13911615.09
#Sta/Elev= 30
  4776.9  1458.2  4787.5 1457.06  4818.7 1456.24  4844.3 1455.08  4858.5 1455.35
  4865.2 1454.56  4872.6 1453.27  4879.4 1450.65  4886.8 1449.63  4893.6 1446.57
    4922 1443.47  4986.1 1443.32  4992.9 1442.24  4994.6 1436.66  4994.9 1436.16
  4998.6 1436.66  5003.3 1436.66  5007.1  1438.5  5021.4 1439.35  5035.6 1442.73
  5049.9  1443.3  5127.6 1442.71  5226.4 1442.37  5234.1 1443.31  5240.7 1442.78
  5269.2 1445.16  5283.4 1447.86  5304.9  1450.3    5347 1452.25  5384.5  1452.9
#Mann= 5 ,-1 , 0
  4776.9     .07       0  4818.7     .12       0  4994.6     .05       0
  4998.6     .12       0  5127.6     .07       0
Bank Sta=4994.6,4998.6
XS Rating Curve= 0 ,0
Exp/Cntr=0.3,0.1

Type RM Length L Ch R = 1 ,27647   ,362,362,362
BEGIN DESCRIPTION:
RAWLS CREEK 59.0
END DESCRIPTION:
XS GIS Cut Line= 3
      2108221.95     13910927.59        2107975.       13911075.
      2107709.04     13911301.75
#Sta/Elev= 30
  4712.4 1454.78  4780.1 1453.81  4789.8 1452.46  4795.7 1450.94    4802 1445.55
  4811.2 1440.44  4817.1 1440.28  4832.6 1432.31  4838.5 1431.71  4869.6 1431.54
  4896.9  1434.1  4938.8 1436.64  4949.4 1437.73    4965  1436.9  4992.2 1436.96
  4997.1    1436  5003.3    1436  5007.1 1430.32  5011.7 1430.12    5012 1429.62
  5015.7 1430.12    5028 1430.85  5035.7 1436.37  5042.3 1436.03  5064.2 1438.31
  5163.1 1439.93  5198.2 1442.37  5276.1 1442.98  5307.7 1442.48  5349.5 1442.87
#Mann= 5 ,-1 , 0
  4712.4     .07       0  4938.8     .12       0  5011.7     .05       0
  5015.7     .12       0  5307.7     .07       0
Bank Sta=5011.7,5015.7
XS Rating Curve= 0 ,0
Exp/Cntr=0.3,0.1

Type RM Length L Ch R = 1 ,27285   ,291,291,291
BEGIN DESCRIPTION:
RAWLS CREEK 58.0
END DESCRIPTION:
XS GIS Cut Line= 3
        2108083.     13910771.36        2107725.       13910875.
      2107256.66     13911285.23
#Sta/Elev= 30
  4627.3 1448.71  4809.7 1434.95  4811.1 1434.87  4854.3 1433.47  4885.5 1431.07
  4916.7 1430.84  4958.4 1425.13  4983.2 1423.78  4995.4 1419.39  4995.6 1418.89
  4999.4 1419.39  5003.3 1419.39  5007.1 1428.82  5013.8 1431.36  5035.6 1434.25
  5079.6 1436.18  5148.5  1435.7  5162.8 1432.64  5170.4 1426.83  5184.6 1425.27
  5212.7 1429.43  5219.7 1432.21  5226.4  1432.3  5233.9 1434.65  5248.2 1435.84
  5389.6 1440.73  5552.8 1444.63  5573.7 1446.06  5587.9    1449  5622.6  1452.9
#Mann= 6 ,-1 , 0
  4627.3     .12       0  4809.7     .07       0  4811.1     .12       0
  4995.4     .05       0  4999.4     .12       0  5079.6     .07       0
Bank Sta=4995.4,4999.4
XS Rating Curve= 0 ,0
Exp/Cntr=0.3,0.1

Type RM Length L Ch R = 1 ,26994   ,308,308,308
BEGIN DESCRIPTION:
RAWLS CREEK 57.0
END DESCRIPTION:
XS GIS Cut Line= 3
      2108152.55     13910709.03        2107625.       13910625.
      2106909.31     13910694.91
#Sta/Elev= 30
  4465.8 1450.58  4510.3 1448.79  4588.3 1445.52  4655.7 1439.15  4897.2 1428.93
  4939.2 1426.63  4966.4 1422.73  4971.4 1423.56  4989.9 1420.54  4997.1 1417.28
  5007.7 1415.21    5008 1414.71  5012.3 1415.21  5030.1 1420.15  5070.3 1423.03
  5080.4 1423.32  5110.5 1419.44  5120.6 1421.07  5140.7 1429.12    5150 1430.06
  5241.1 1432.38  5251.2 1430.96  5271.3 1432.88    5412  1435.8    5465 1442.03
  5492.3 1448.68  5512.4 1451.08    5633  1454.4  5668.4 1457.55  5719.1 1459.68
#Mann= 6 ,-1 , 0
  4465.8    .035       0  4510.3     .07       0  4897.2     .12       0
  4997.1     .07       0  5007.7     .05       0  5012.3     .07       0
Bank Sta=5007.7,5012.3
XS Rating Curve= 0 ,0
Exp/Cntr=0.3,0.1

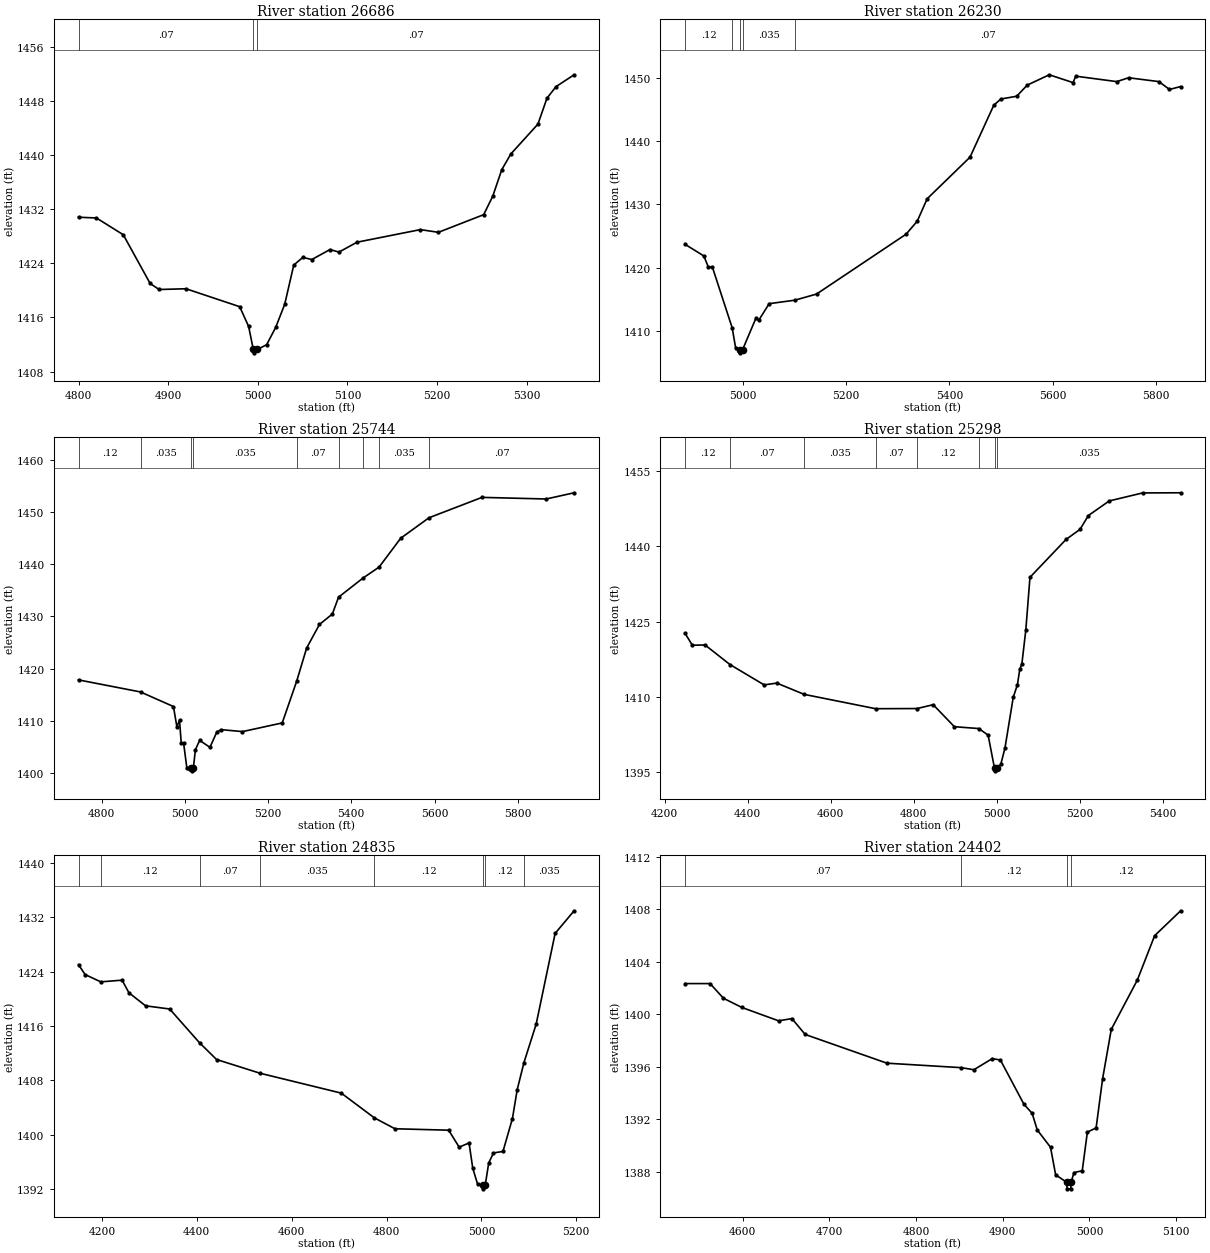
Type RM Length L Ch R = 1 ,26686   ,456,456,456
BEGIN DESCRIPTION:
RAWLS CREEK 56.0
END DESCRIPTION:
XS GIS Cut Line= 3
      2107674.97       13910375.        2107475.       13910375.
      2107125.03       13910425.
#Sta/Elev= 30
  4799.6 1430.81  4819.6  1430.7  4849.6 1428.22  4879.6 1421.02  4889.6 1420.13
  4919.6 1420.24  4979.6 1417.59  4989.6 1414.67  4994.8 1411.27  4995.1 1410.77
  4999.4 1411.27  5009.7 1411.97  5019.8 1414.52  5029.9 1417.95    5040 1423.74
  5050.1 1424.87  5060.2 1424.56  5080.4 1426.03  5090.5 1425.66  5110.7 1427.12
  5181.4 1428.98  5201.6 1428.58  5252.1 1431.19  5262.2  1433.9  5272.3 1437.83
  5282.4 1440.15  5312.7 1444.57  5322.8  1448.4  5332.9 1450.11  5353.1 1451.86
#Mann= 3 ,-1 , 0
  4799.6     .07       0  4994.8     .05       0  4999.4     .07       0
Bank Sta=4994.8,4999.4
XS Rating Curve= 0 ,0
Exp/Cntr=0.3,0.1

Type RM Length L Ch R = 1 ,26230   ,486,486,486
BEGIN DESCRIPTION:
RAWLS CREEK 55.0
END DESCRIPTION:
XS GIS Cut Line= 3
      2107725.03     13910025.01        2107625.       13909975.
      2106793.78     13910140.18
#Sta/Elev= 30
  4888.2  1423.7  4924.6 1421.86  4932.9 1420.18  4941.3 1420.06  4979.5 1410.49
  4986.1 1407.35  4994.9 1407.05  4995.2 1406.55  4999.6 1407.05  5025.6 1412.06
  5030.7 1411.67    5051 1414.32  5100.8 1414.87  5142.8 1415.84  5316.1  1425.3
  5337.6 1427.35  5356.9  1430.9  5439.8 1437.47  5485.9 1445.69  5499.6 1446.66
  5530.2  1447.1  5550.6 1448.86  5593.3 1450.49  5639.3 1449.25  5644.4 1450.27
  5723.9 1449.41  5746.7 1450.02  5805.5 1449.41  5825.9 1448.17  5847.5 1448.63
#Mann= 5 ,-1 , 0
  4888.2     .12       0  4979.5    .035       0  4994.9    .035       0
  4999.6    .035       0  5100.8     .07       0
Bank Sta=4994.9,4999.6
XS Rating Curve= 0 ,0
Exp/Cntr=0.3,0.1

Type RM Length L Ch R = 1 ,25744   ,446,446,446
BEGIN DESCRIPTION:
RAWLS CREEK 54.0
END DESCRIPTION:
XS GIS Cut Line= 3
      2107824.98     13909674.98        2107625.       13909525.
      2106709.77     13909307.05
#Sta/Elev= 30
  4744.6 1417.85  4893.6 1415.54  4972.7 1412.75    4981 1408.86  4987.3 1410.15
  4991.4 1405.75  4997.1 1405.75  5004.9 1401.01  5015.9 1400.94  5016.2 1400.44
  5020.6 1400.94  5025.4 1404.48  5035.7 1406.27  5060.4 1404.94  5076.8 1407.84
  5087.1 1408.33  5138.5 1407.95  5234.1 1409.61  5268.8  1417.6  5292.7 1423.94
  5323.5 1428.46  5354.4 1430.44  5369.4 1433.68  5428.1 1437.34  5466.8 1439.44
  5518.8 1444.97  5586.8 1448.89  5714.1 1452.79  5868.3 1452.48  5935.4 1453.67
#Mann= 9 ,-1 , 0
  4744.6     .12       0  4893.6    .035       0  5015.9    .035       0
  5020.6    .035       0  5268.8     .07       0  5369.4     .12       0
  5428.1     .07       0  5466.8    .035       0  5586.8     .07       0
Bank Sta=5015.9,5020.6
XS Rating Curve= 0 ,0
Exp/Cntr=0.3,0.1

Type RM Length L Ch R = 1 ,25298   ,463,463,463
BEGIN DESCRIPTION:
RAWLS CREEK 53.0
END DESCRIPTION:
XS GIS Cut Line= 3
      2108212.26     13909261.45        2107475.       13909125.
      2107033.83     13909085.67
#Sta/Elev= 30
  4249.4 1422.65  4266.9 1420.27  4297.5 1420.32  4357.4 1416.42  4439.8 1412.35
  4470.3 1412.71    4536 1410.46  4708.1  1407.6  4807.7 1407.63  4846.6  1408.4
  4897.5 1404.01  4956.4 1403.64  4978.8 1402.32  4994.2  1395.7  4994.5  1395.2
  4999.1  1395.7  5009.2 1396.47  5019.3 1399.74  5039.3 1409.89  5049.4 1412.41
  5054.9 1415.46    5060 1416.53  5069.5  1423.3  5079.5 1433.82  5166.5 1441.39
    5200 1443.39  5220.1 1446.15  5270.2 1449.06  5350.6 1450.66  5442.1 1450.69
#Mann= 8 ,-1 , 0
  4249.4     .12       0  4357.4     .07       0    4536    .035       0
  4708.1     .07       0  4807.7     .12       0  4956.4    .035       0
  4994.2    .035       0  4999.1    .035       0
Bank Sta=4994.2,4999.1
XS Rating Curve= 0 ,0
Exp/Cntr=0.3,0.1

Type RM Length L Ch R = 1 ,24835   ,433,433,433
BEGIN DESCRIPTION:
RAWLS CREEK 52.0
END DESCRIPTION:
XS GIS Cut Line= 3
      2108323.58     13909266.42        2107675.       13908725.
      2107474.96       13908725.
#Sta/Elev= 30
  4150.6 1425.03  4164.5 1423.58  4197.5  1422.5  4242.5 1422.75  4256.9 1420.89
    4292 1418.97  4342.8  1418.5  4405.7 1413.53  4441.7 1411.06  4533.3 1409.04
  4704.6 1406.11  4774.5 1402.46  4817.8 1400.86    4931 1400.65  4953.2 1398.15
    4974 1398.77  4981.8 1395.06  4992.2 1392.65    5003 1392.51  5003.4 1392.01
    5008 1392.51  5015.5 1395.83  5025.5  1397.3  5045.5 1397.52  5065.5 1402.37
  5075.5 1406.61  5089.8 1410.62  5115.5 1416.27  5155.5 1429.64  5195.5 1432.97
#Mann= 8 ,-1 , 0
  4150.6     .07       0  4197.5     .12       0  4405.7     .07       0
  4533.3    .035       0  4774.5     .12       0    5003     .05       0
    5008     .12       0  5089.8    .035       0
Bank Sta=5003,5008
XS Rating Curve= 0 ,0
Exp/Cntr=0.3,0.1

Type RM Length L Ch R = 1 ,24402   ,468,468,468
BEGIN DESCRIPTION:
RAWLS CREEK 51.0
END DESCRIPTION:
XS GIS Cut Line= 3
      2108025.02     13908725.03        2107775.       13908325.
      2107675.03       13908325.
#Sta/Elev= 30
  4533.5 1402.34  4562.4 1402.34  4577.8 1401.22    4599 1400.52  4641.4  1399.5
  4656.8 1399.67  4672.1 1398.46  4766.4 1396.27    4852 1395.93  4866.7 1395.77
  4887.9 1396.62  4897.3 1396.51  4924.5 1393.13  4933.9 1392.45  4939.8 1391.18
  4955.1 1389.86    4961 1387.76  4973.8 1387.19  4974.2 1386.69  4978.5 1386.69
  4978.8 1387.19  4982.2 1387.93  4991.7 1388.07  4997.6 1391.01  5007.7 1391.34
  5015.2 1395.09  5025.2 1398.85  5055.2  1402.6  5075.2 1405.99  5105.2 1407.89
#Mann= 4 ,-1 , 0
  4533.5     .07       0    4852     .12       0  4973.8     .05       0
  4978.8     .12       0
Bank Sta=4973.8,4978.8
XS Rating Curve= 0 ,0
Exp/Cntr=0.3,0.1