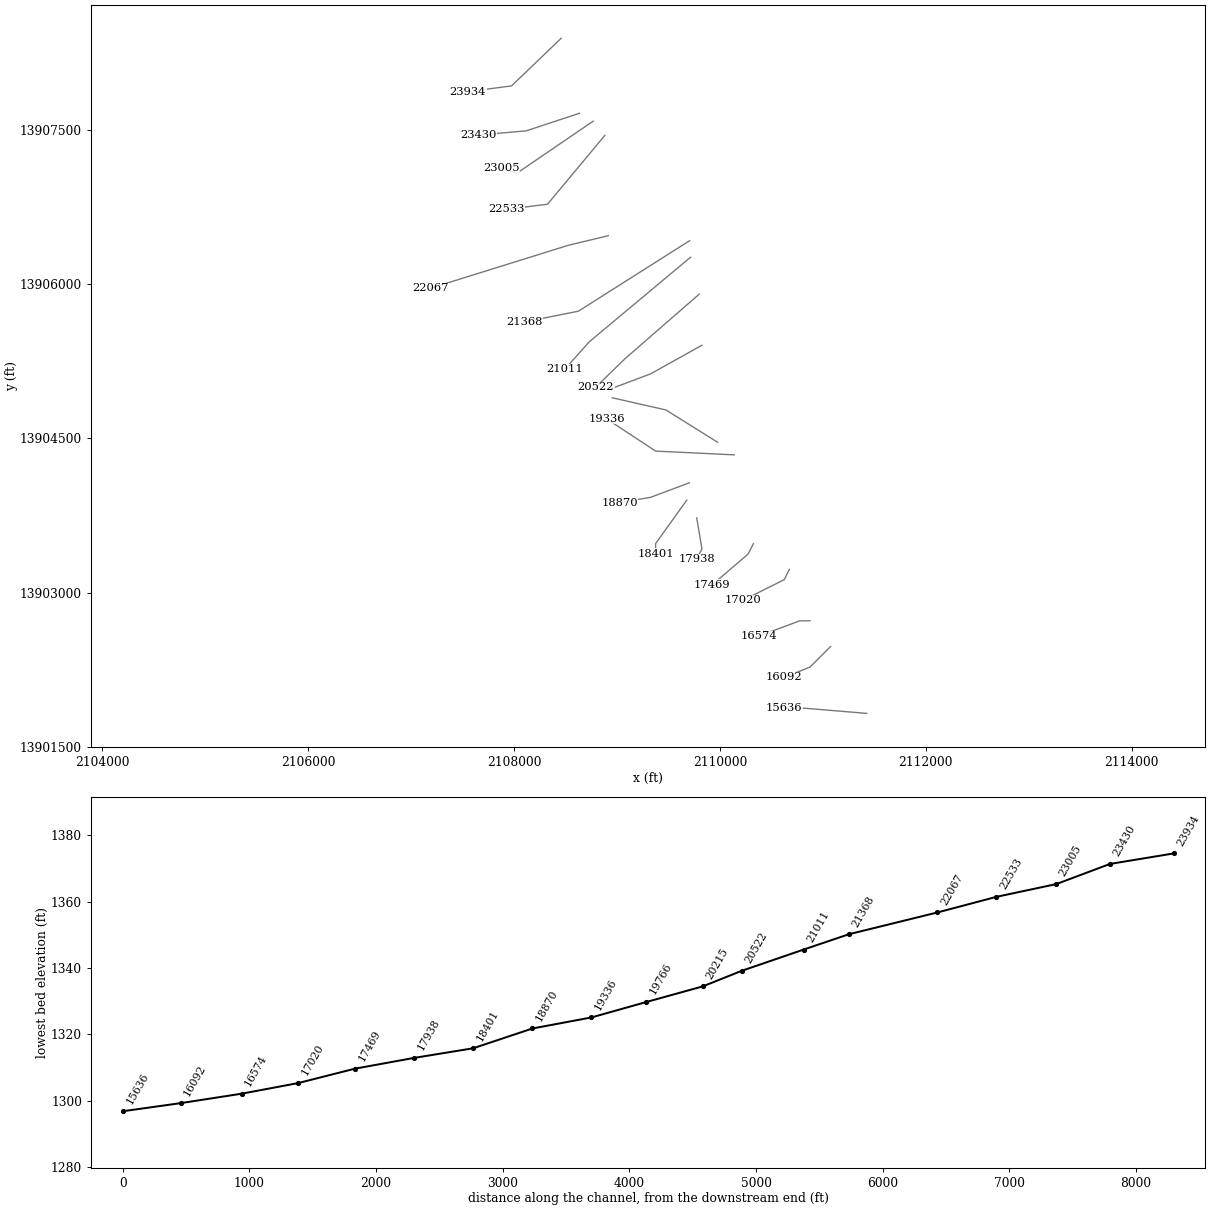
HEC-RAS study RAWLS CREEK.prj: RAWLS CREEK Base Level Engineering

--- RAWLS CREEK.g01 (geometry) --- (continued)

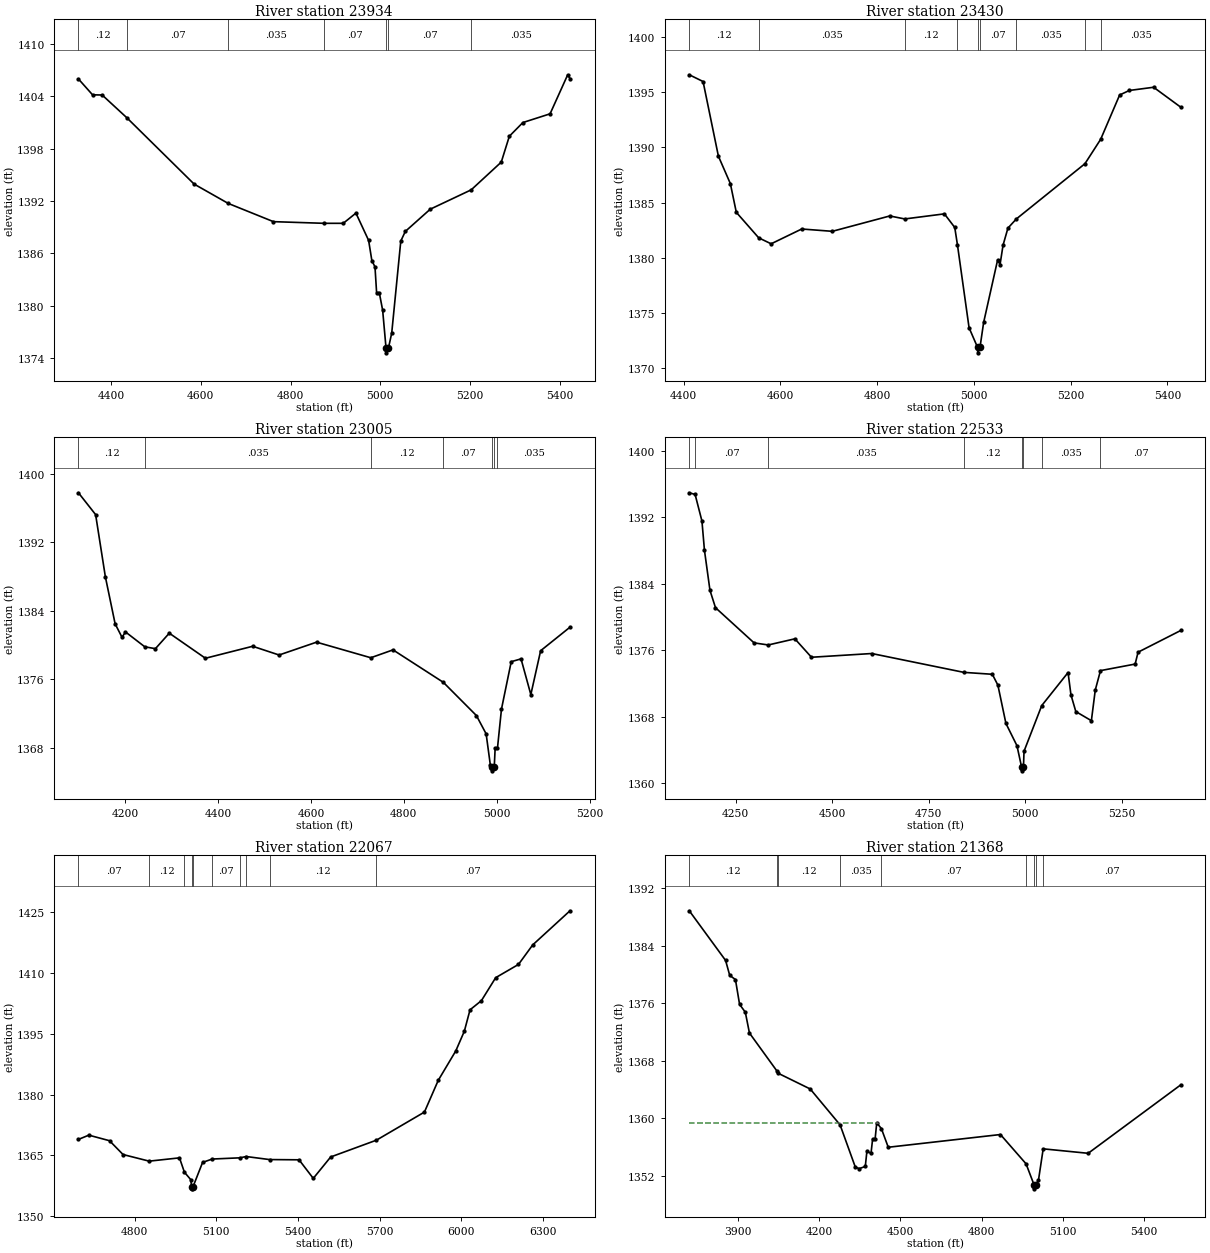
Type RM Length L Ch R = 1 ,23934   ,504,504,504
BEGIN DESCRIPTION:
RAWLS CREEK 50.0
END DESCRIPTION:
XS GIS Cut Line= 3
      2108456.99     13908387.72        2107975.       13907925.
      2107550.92     13907869.87
#Sta/Elev= 30
  4327.1    1406  4358.6 1404.18    4380 1404.16  4434.8 1401.56    4585 1393.94
  4661.1 1391.72  4761.8 1389.63  4874.4 1389.44  4917.4 1389.44  4945.7 1390.61
    4974 1387.48  4981.2 1385.17  4988.2 1384.44  4991.8 1381.48  4997.8 1381.48
  5005.3 1379.46  5012.9 1375.08  5013.3 1374.58    5018 1375.08  5025.5 1376.85
  5045.7  1387.4  5055.8 1388.51  5111.4 1391.06  5202.7 1393.28  5269.7 1396.46
  5287.7 1399.43  5317.9    1401  5378.5    1402  5417.8 1406.48  5422.9 1406.05
#Mann= 7 ,-1 , 0
  4327.1     .12       0  4434.8     .07       0  4661.1    .035       0
  4874.4     .07       0  5012.9     .05       0    5018     .07       0
  5202.7    .035       0
Bank Sta=5012.9,5018
XS Rating Curve= 0 ,0
Exp/Cntr=0.3,0.1

Type RM Length L Ch R = 1 ,23430   ,425,425,425
BEGIN DESCRIPTION:
Rawls Creek 49.0
END DESCRIPTION:
XS GIS Cut Line= 3
      2108635.61     13907659.41      2108118.81     13907488.53
      2107648.96     13907446.95
#Sta/Elev= 30
  4411.6 1396.58  4440.1 1395.97  4471.8 1389.21  4496.5 1386.73  4508.8 1384.13
  4555.1 1381.82  4580.8 1381.28    4644 1382.62  4707.2 1382.41    4826  1383.8
    4857 1383.53  4938.9 1383.99  4960.3 1382.76  4965.8 1381.21  4989.9 1373.68
  5007.4 1371.91  5007.8 1371.41  5012.5 1371.91    5020 1374.16  5048.9 1379.82
  5053.9 1379.39  5060.1 1381.15  5070.2  1382.7  5087.6 1383.53  5229.4 1388.53
  5261.9 1390.74  5301.1 1394.75  5321.1 1395.16  5371.3 1395.45  5427.6 1393.64
#Mann= 9 ,-1 , 0
  4411.6     .12       0  4555.1    .035       0    4857     .12       0
  4965.8     .07       0  5007.4     .05       0  5012.5     .07       0
  5087.6    .035       0  5229.4     .07       0  5261.9    .035       0
Bank Sta=5007.4,5012.5
XS Rating Curve= 0 ,0
Exp/Cntr=0.3,0.1

Type RM Length L Ch R = 1 ,23005   ,472,472,472
BEGIN DESCRIPTION:
RAWLS CREEK 48.0
END DESCRIPTION:
XS GIS Cut Line= 3
      2108768.61      13907582.2        2108025.       13907075.
      2107875.03     13907124.99
#Sta/Elev= 30
  4099.5  1397.8  4136.5 1395.25  4157.5 1387.98  4178.5 1382.49  4193.4 1380.91
  4200.7 1381.55  4242.3 1379.81  4265.2 1379.59  4295.1  1381.4  4372.9 1378.47
  4474.6 1379.87  4531.5 1378.85  4612.1 1380.35  4728.9 1378.53  4776.7 1379.45
    4885 1375.66  4956.2 1371.78  4977.2 1369.64  4986.1 1366.05  4989.6 1365.82
    4990 1365.32  4994.7 1365.82  4996.6 1367.98  5001.6 1367.98  5010.2 1372.53
  5031.2 1378.07  5052.3  1378.4  5073.4 1374.23  5094.5 1379.35  5157.7  1382.1
#Mann= 7 ,-1 , 0
  4099.5     .12       0  4242.3    .035       0  4728.9     .12       0
    4885     .07       0  4989.6     .05       0  4994.7     .07       0
  5001.6    .035       0
Bank Sta=4989.6,4994.7
XS Rating Curve= 0 ,0
Exp/Cntr=0.3,0.1

Type RM Length L Ch R = 1 ,22533   ,466,466,466
BEGIN DESCRIPTION:
RAWLS CREEK 47.0
END DESCRIPTION:
XS GIS Cut Line= 3
      2108881.94     13907444.03        2108325.       13906775.
      2107925.02       13906725.
#Sta/Elev= 30
    4130 1394.97  4145.1 1394.77  4162.8 1391.57  4169.3 1388.05  4183.6 1383.22
  4197.9 1381.13  4297.9 1376.89  4334.6 1376.64  4403.6 1377.38  4446.6 1375.16
  4602.8 1375.61  4841.5 1373.34  4915.2 1373.11  4929.6  1371.8  4950.4 1367.19
    4979 1364.51  4990.8 1361.98  4991.2 1361.48  4995.9 1361.98  4997.3 1363.84
  5043.2 1369.34  5111.4 1373.32  5118.9 1370.63  5131.5 1368.62  5171.8 1367.52
  5181.9 1371.21  5195.4 1373.55  5285.2 1374.34  5292.8 1375.77  5403.6 1378.39
#Mann= 8 ,-1 , 0
    4130     .12       0  4145.1     .07       0  4334.6    .035       0
  4841.5     .12       0  4990.8     .05       0  4995.9     .12       0
  5043.2    .035       0  5195.4     .07       0
Bank Sta=4990.8,4995.9
XS Rating Curve= 0 ,0
Exp/Cntr=0.3,0.1

Type RM Length L Ch R = 1 ,22067   ,699,699,699
BEGIN DESCRIPTION:
RAWLS CREEK 46.0
END DESCRIPTION:
XS GIS Cut Line= 3
      2108916.07      13906469.2        2108525.       13906375.
      2107184.29     13905957.04
#Sta/Elev= 30
  4593.2 1368.96  4631.4 1370.01  4707.4 1368.64  4757.2 1365.23  4853.2  1363.6
  4964.6 1364.41  4982.7 1360.87  5005.9 1359.05  5009.2 1357.27  5009.6 1356.77
  5014.3 1357.27  5049.5 1363.29  5084.8 1364.12  5187.1 1364.42  5209.6 1364.74
  5295.5 1363.99    5404 1363.93  5456.3 1359.35  5520.3 1364.63  5688.3 1368.77
  5864.8  1375.7  5915.7 1383.54  5980.1 1390.79  6011.5 1395.65  6032.4 1400.92
  6074.3 1403.19  6126.7 1408.85  6210.5 1412.12  6262.9 1416.94  6399.8 1425.35
#Mann= 10 ,-1 , 0
  4593.2     .07       0  4853.2     .12       0  4982.7    .035       0
  5009.2    .035       0  5014.3    .035       0  5084.8     .07       0
  5187.1    .035       0  5209.6     .07       0  5295.5     .12       0
  5688.3     .07       0
Bank Sta=5009.2,5014.3
XS Rating Curve= 0 ,0
Exp/Cntr=0.3,0.1

Type RM Length L Ch R = 1 ,21368   ,357,357,357
BEGIN DESCRIPTION:
Rawls Creek 45.0
END DESCRIPTION:
XS GIS Cut Line= 3
       2109705.6     13906420.32      2108624.99       13905735.
      2108099.35     13905630.13
#Sta/Elev= 30
  3720.4 1388.85  3854.5 1381.95  3869.8 1379.87  3890.9 1379.29  3906.2 1375.84
  3927.4 1374.75  3942.6 1371.86  4044.1 1366.58  4048.4 1366.27  4167.1 1364.08
  4277.4 1359.09  4334.1 1353.18  4348.7 1353.02  4370.5 1353.31  4376.4  1355.4
  4391.7 1355.15  4397.6 1357.13  4406.9 1357.17  4412.8 1359.38    4430 1358.57
  4455.3 1355.98  4869.7 1357.75  4964.3 1353.68  4994.4  1350.7  4994.8  1350.2
  4999.7  1350.7  5010.2 1351.41  5027.6 1355.76  5193.7 1355.14    5536 1364.66
#Mann= 9 ,-1 , 0
  3720.4     .12       0  4044.1     .07       0  4048.4     .12       0
  4277.4    .035       0    4430     .07       0  4964.3    .035       0
  4994.4    .035       0  4999.7    .035       0  5027.6     .07       0
#XS Ineff= 2 , 0
       0 4417.78 1359.34               0
Permanent Ineff=
       F       F
Bank Sta=4994.4,4999.7
XS Rating Curve= 0 ,0
Exp/Cntr=0.3,0.1

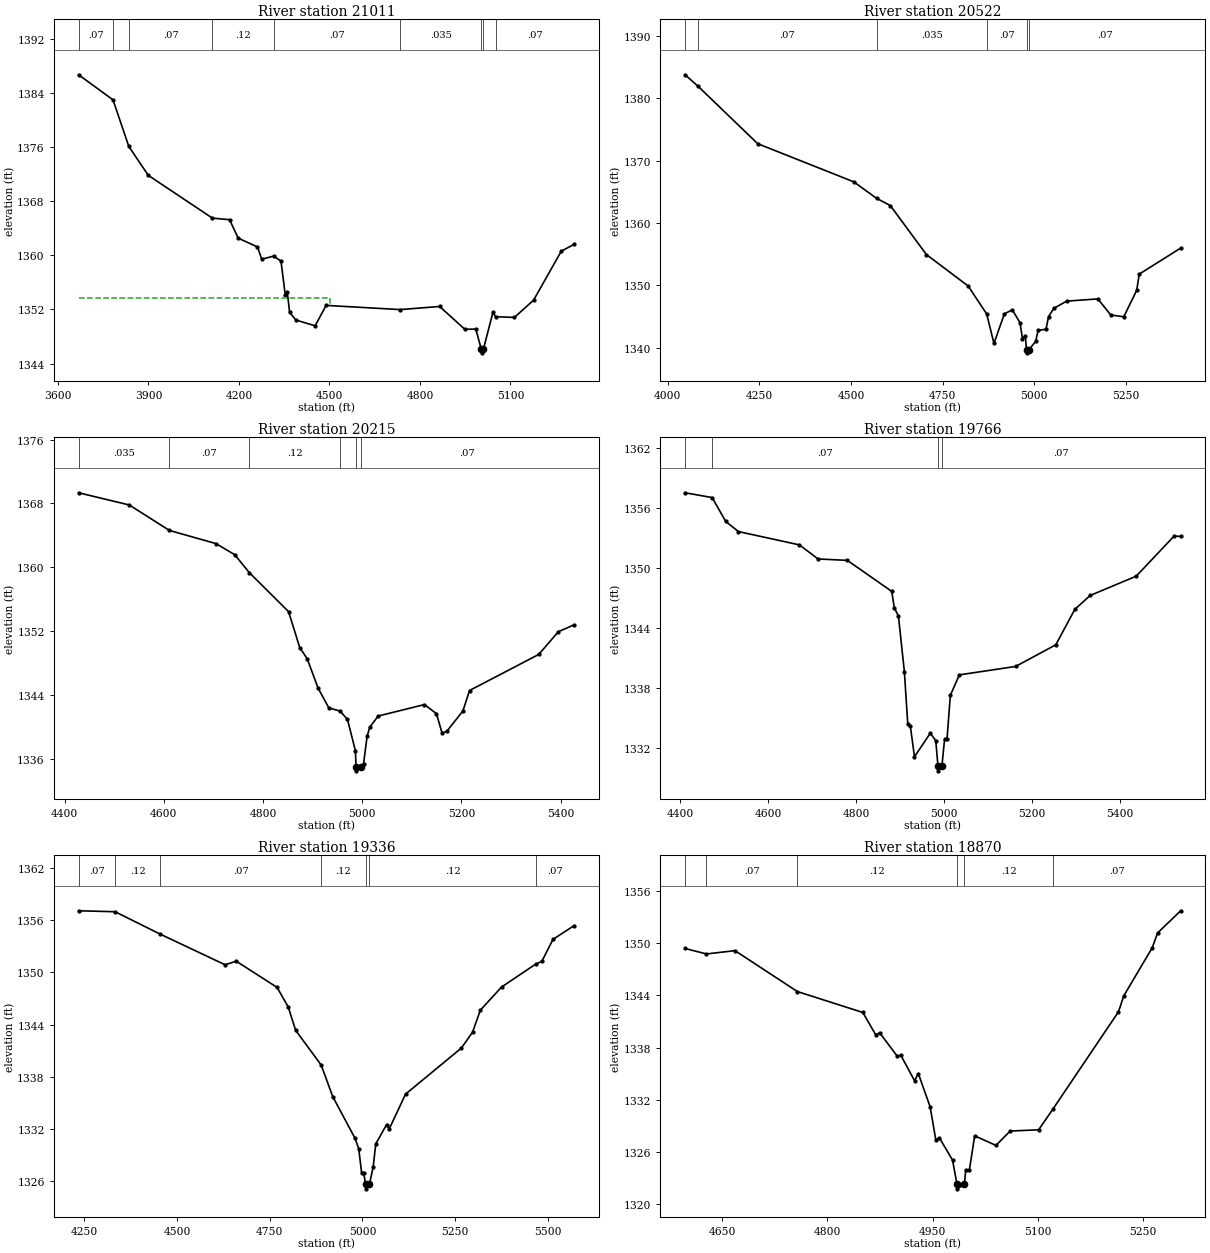
Type RM Length L Ch R = 1 ,21011   ,489,489,489
BEGIN DESCRIPTION:
Rawls Creek 44.0
END DESCRIPTION:
XS GIS Cut Line= 3
      2109714.93     13906259.97      2108731.42     13905438.15
      2108491.05     13905168.77
#Sta/Elev= 30
  3668.6 1386.72  3782.6 1383.01  3834.8 1376.13  3899.5 1371.84  4112.1 1365.51
  4168.9 1365.28  4197.5 1362.55  4261.3 1361.25  4275.6 1359.44  4315.3 1359.89
  4339.4 1359.15  4353.7 1354.11  4360.2 1354.59    4368 1351.55  4388.9 1350.43
  4452.6 1349.58    4489  1352.6  4734.8 1351.98  4865.2 1352.44  4948.8 1349.07
  4985.2 1349.09  5003.6 1346.08  5004.1 1345.58  5010.2 1346.08  5042.1  1351.6
  5050.6 1350.93  5113.1 1350.82  5176.7 1353.37  5268.6 1360.62  5311.3 1361.64
#Mann= 9 ,-1 , 0
  3668.6     .07       0  3782.6     .12       0  3834.8     .07       0
  4112.1     .12       0  4315.3     .07       0  4734.8    .035       0
  5003.6    .035       0  5010.2    .035       0  5050.6     .07       0
#XS Ineff= 2 , 0
       0 4501.72 1353.71               0
Permanent Ineff=
       F       F
Bank Sta=5003.6,5010.2
XS Rating Curve= 0 ,0
Exp/Cntr=0.3,0.1

Type RM Length L Ch R = 1 ,20522   ,307,307,307
BEGIN DESCRIPTION:
Rawls Creek 43.0
END DESCRIPTION:
XS GIS Cut Line= 3
      2109798.84     13905900.57      2109079.97     13905275.07
      2108793.96     13904996.43
#Sta/Elev= 30
  4047.1 1383.75  4082.6  1381.9  4245.2  1372.7  4507.3 1366.59  4569.6 1363.94
    4607 1362.79  4705.7 1354.92  4819.6 1349.88    4870 1345.41  4889.9 1340.68
  4918.4 1345.43  4940.2 1346.06  4961.1 1343.97  4967.7 1341.41  4975.4 1341.92
  4978.7 1339.67  4979.2 1339.17  4985.3 1339.67  5003.6    1341  5010.6 1342.78
  5031.9 1342.95  5038.9 1344.97    5053 1346.29  5088.5 1347.46  5173.4 1347.82
  5208.6 1345.24  5244.1 1344.95  5279.4 1349.19  5286.3 1351.79  5399.3 1355.96
#Mann= 6 ,-1 , 0
  4047.1     .12       0  4082.6     .07       0  4569.6    .035       0
    4870     .07       0  4978.7     .05       0  4985.3     .07       0
Bank Sta=4978.7,4985.3
XS Rating Curve= 0 ,0
Exp/Cntr=0.3,0.1

Type RM Length L Ch R = 1 ,20215   ,449,449,449
BEGIN DESCRIPTION:
RAWLS CREEK 42.0
END DESCRIPTION:
XS GIS Cut Line= 3
      2109824.24     13905403.39        2109325.       13905125.
      2108925.01       13904975.
#Sta/Elev= 30
  4428.4 1369.34  4530.6 1367.81  4611.3 1364.62  4705.2 1362.97  4742.9 1361.58
  4772.5 1359.33  4851.5 1354.44  4874.1 1349.93  4889.2 1348.52  4910.9 1344.87
  4932.6 1342.38  4955.6 1341.96  4970.3 1340.92  4986.3 1336.99  4987.5 1334.98
    4988 1334.48  4996.6 1334.98  5002.7 1335.36  5009.8  1338.8  5015.1 1339.94
  5032.1 1341.35  5125.5 1342.79  5149.5 1341.65  5161.1 1339.19  5170.9 1339.47
  5202.9 1341.98  5216.3 1344.55    5356 1349.08  5395.2 1351.92  5427.2 1352.79
#Mann= 6 ,-1 , 0
  4428.4    .035       0  4611.3     .07       0  4772.5     .12       0
  4955.6     .07       0  4987.5     .05       0  4996.6     .07       0
Bank Sta=4987.5,4996.6
XS Rating Curve= 0 ,0
Exp/Cntr=0.3,0.1

Type RM Length L Ch R = 1 ,19766   ,430,430,430
BEGIN DESCRIPTION:
RAWLS CREEK 41.0
END DESCRIPTION:
XS GIS Cut Line= 3
      2109977.82     13904460.67        2109475.       13904775.
      2108954.38     13904892.96
#Sta/Elev= 30
  4411.3 1357.54  4472.9 1357.06  4503.7 1354.67  4532.6 1353.66  4671.2 1352.33
  4713.6 1350.92  4780.2 1350.78  4881.1 1347.68    4887 1346.05  4896.4  1345.2
  4909.9 1339.65  4917.6 1334.43  4923.5 1334.19  4932.9 1331.14  4968.9  1333.5
  4981.3 1332.75  4986.2 1330.23  4986.7 1329.73  4995.3 1330.23  5001.3 1332.87
  5006.8 1332.87  5014.5 1337.29    5035 1339.33  5162.9 1340.17  5254.3 1342.34
  5297.5 1345.88  5332.4 1347.27  5437.1  1349.2  5523.4 1353.22  5538.1 1353.17
#Mann= 4 ,-1 , 0
  4411.3     .12       0  4472.9     .07       0  4986.2     .05       0
  4995.3     .07       0
Bank Sta=4986.2,4995.3
XS Rating Curve= 0 ,0
Exp/Cntr=0.3,0.1

Type RM Length L Ch R = 1 ,19336   ,466,466,466
BEGIN DESCRIPTION:
RAWLS CREEK 40.0
END DESCRIPTION:
XS GIS Cut Line= 3
      2110139.33     13904338.26        2109375.       13904375.
      2108898.52      13904688.9
#Sta/Elev= 30
  4235.1 1357.09  4333.3 1356.98  4454.2 1354.42  4629.9 1350.88  4659.9 1351.29
    4770 1348.28  4800.1 1346.03  4820.1 1343.34  4888.9 1339.35  4920.2 1335.71
  4980.3 1330.91  4990.3  1329.7  4997.8 1326.98  5003.3 1326.98  5008.8 1325.61
  5009.3 1325.11  5018.9 1325.61  5028.9 1327.59  5036.2 1330.29  5065.1 1332.49
  5072.2 1331.98  5116.3    1336  5266.8  1341.3    5297 1343.13    5318 1345.66
  5375.2 1348.32  5466.9 1350.95  5483.7 1351.27  5513.8  1353.8  5570.9 1355.39
#Mann= 7 ,-1 , 0
  4235.1     .07       0  4333.3     .12       0  4454.2     .07       0
  4888.9     .12       0  5008.8     .05       0  5018.9     .12       0
  5466.9     .07       0
Bank Sta=5008.8,5018.9
XS Rating Curve= 0 ,0
Exp/Cntr=0.3,0.1

Type RM Length L Ch R = 1 ,18870   ,469,469,469
BEGIN DESCRIPTION:
RAWLS CREEK 39.0
END DESCRIPTION:
XS GIS Cut Line= 3
      2109702.53     13904066.54        2109325.       13903925.
      2109025.03       13903875.
#Sta/Elev= 30
  4596.8 1349.39  4627.2 1348.76    4668 1349.14  4757.1 1344.44  4850.5 1342.04
  4869.1 1339.44  4874.5 1339.71  4899.4 1337.04  4904.8 1337.11  4924.3  1334.2
  4929.7 1335.02  4946.6 1331.19  4954.6 1327.41  4959.9 1327.62  4978.6 1325.07
  4984.9 1322.28  4985.4 1321.78  4995.4 1322.28  4997.3  1323.9  5002.5  1323.9
  5010.1 1327.87  5040.5 1326.77  5060.8 1328.42  5101.4 1328.56  5121.8 1330.94
  5215.4 1342.12    5223 1343.96  5263.6 1349.48  5271.2 1351.17  5304.1 1353.72
#Mann= 6 ,-1 , 0
  4596.8    .035       0  4627.2     .07       0  4757.1     .12       0
  4984.9     .05       0  4995.4     .12       0  5121.8     .07       0
Bank Sta=4984.9,4995.4
XS Rating Curve= 0 ,0
Exp/Cntr=0.3,0.1

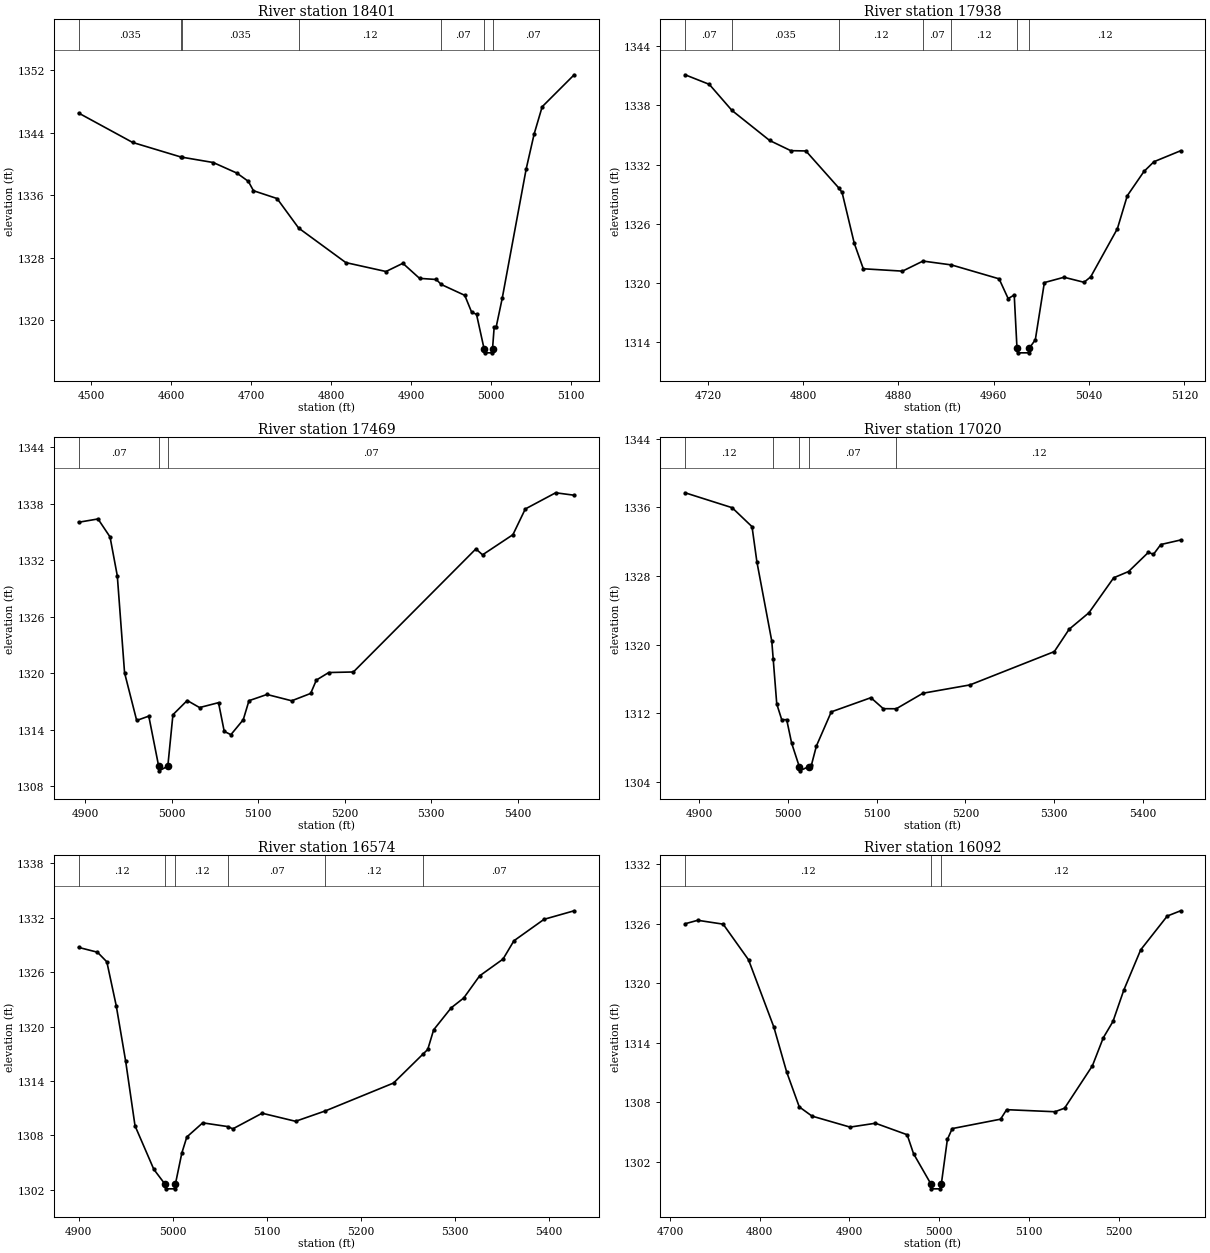
Type RM Length L Ch R = 1 ,18401   ,463,463,463
BEGIN DESCRIPTION:
RAWLS CREEK 38.0
END DESCRIPTION:
XS GIS Cut Line= 3
      2109677.45     13903897.52        2109375.       13903475.
        2109375.     13903375.02
#Sta/Elev= 30
  4484.2 1346.49  4551.7 1342.73  4612.6 1340.85  4612.9 1340.85  4652.5 1340.16
    4682 1338.81  4696.4 1337.75  4702.8 1336.55  4732.3 1335.55  4759.3 1331.77
  4818.3 1327.35  4868.5 1326.21  4889.6 1327.26  4910.5 1325.33  4931.3 1325.19
  4937.6 1324.55    4967 1323.16  4975.6    1321  4981.7 1320.73  4991.2  1316.3
  4991.7  1315.8  5001.2  1315.8  5001.7  1316.3  5003.8 1319.12  5006.3 1319.12
  5013.8 1322.76  5043.8 1339.34  5053.8 1343.83  5063.8  1347.3  5103.8 1351.39
#Mann= 7 ,-1 , 0
  4484.2    .035       0  4612.6     .12       0  4612.9    .035       0
  4759.3     .12       0  4937.6     .07       0  4991.2     .05       0
  5001.7     .07       0
Bank Sta=4991.2,5001.7
XS Rating Curve= 0 ,0
Exp/Cntr=0.3,0.1

Type RM Length L Ch R = 1 ,17938   ,469,469,469
BEGIN DESCRIPTION:
RAWLS CREEK 37.0
END DESCRIPTION:
XS GIS Cut Line= 3
        2109775.     13903725.02        2109825.       13903425.
      2109774.98     13903324.97
#Sta/Elev= 30
  4700.9  1341.1  4721.2 1340.13  4740.2 1337.49  4771.9 1334.44  4789.6 1333.41
  4802.3 1333.38    4830 1329.62  4832.7 1329.17  4842.9 1324.03  4850.5 1321.44
  4883.4  1321.2  4900.6 1322.22  4924.5 1321.83  4964.5 1320.42  4972.1 1318.42
  4977.2 1318.78  4979.5 1313.42    4980 1312.92  4989.5 1312.92    4990 1313.42
  4994.9 1314.24  5002.5 1320.04    5019 1320.58  5035.8 1320.07  5041.4 1320.62
  5063.8  1325.5  5072.1 1328.84  5086.1  1331.3  5094.5 1332.29  5116.9  1333.4
#Mann= 7 ,-1 , 0
  4700.9     .07       0  4740.2    .035       0    4830     .12       0
  4900.6     .07       0  4924.5     .12       0  4979.5     .05       0
    4990     .12       0
Bank Sta=4979.5,4990
XS Rating Curve= 0 ,0
Exp/Cntr=0.3,0.1

Type RM Length L Ch R = 1 ,17469   ,449,449,449
BEGIN DESCRIPTION:
RAWLS CREEK 36.0
END DESCRIPTION:
XS GIS Cut Line= 3
        2110325.       13903475.        2110275.       13903375.
      2109924.99     13903074.99
#Sta/Elev= 30
  4892.4 1336.06  4914.8 1336.41  4928.7  1334.5  4937.1 1330.37  4945.5 1320.07
  4959.5 1315.01  4973.5 1315.47  4984.9 1310.16  4985.4 1309.66  4995.5 1310.16
  5001.4 1315.62  5017.9 1317.13  5032.2 1316.38  5054.1  1316.9  5060.7 1313.85
  5068.4  1313.5  5082.7 1315.09  5089.3 1317.11  5110.1 1317.77  5138.7  1317.1
  5160.6 1317.88  5167.2  1319.3  5181.5  1320.1    5210 1320.16  5351.6 1333.23
  5359.3  1332.6  5394.4 1334.74  5408.7 1337.47  5443.8 1339.19  5465.2 1338.93
#Mann= 3 ,-1 , 0
  4892.4     .07       0  4984.9     .05       0  4995.5     .07       0
Bank Sta=4984.9,4995.5
XS Rating Curve= 0 ,0
Exp/Cntr=0.3,0.1

Type RM Length L Ch R = 1 ,17020   ,446,446,446
BEGIN DESCRIPTION:
RAWLS CREEK 35.0
END DESCRIPTION:
XS GIS Cut Line= 3
        2110675.     13903224.99        2110625.       13903125.
      2110225.01       13902925.
#Sta/Elev= 30
  4883.9  1337.7    4937 1335.96  4959.4 1333.75  4964.9 1329.65  4981.7 1320.41
  4983.3 1318.32  4987.3  1313.1  4992.9 1311.27  4998.5 1311.27  5004.1 1308.53
  5012.7 1305.81  5013.2 1305.31  5023.5 1305.81  5026.4 1305.98    5032  1308.2
  5048.8 1312.18  5093.5 1313.83  5107.5 1312.55  5122.1 1312.54  5152.2 1314.35
  5205.3 1315.32  5300.4  1319.2  5317.1  1321.8  5339.5 1323.73  5367.4  1327.8
  5384.2 1328.53  5406.6 1330.77  5412.2 1330.52  5420.5 1331.67  5442.9  1332.2
#Mann= 5 ,-1 , 0
  4883.9     .12       0  4983.3     .07       0  5012.7     .05       0
  5023.5     .07       0  5122.1     .12       0
Bank Sta=5012.7,5023.5
XS Rating Curve= 0 ,0
Exp/Cntr=0.3,0.1

Type RM Length L Ch R = 1 ,16574   ,482,482,482
BEGIN DESCRIPTION:
RAWLS CREEK 34.0
END DESCRIPTION:
XS GIS Cut Line= 3
      2110874.99       13902725.        2110775.       13902725.
      2110374.99       13902575.
#Sta/Elev= 30
    4900 1328.74    4920 1328.21    4930 1327.15    4940 1322.31    4950 1316.21
    4960 1309.06    4980 1304.26    4992 1302.61  4992.5 1302.11  5002.4 1302.11
  5002.9 1302.61  5009.8 1306.06  5015.1 1307.83    5032 1309.39  5058.5 1308.98
  5064.1 1308.73  5095.2 1310.45  5130.8 1309.56  5162.6 1310.71    5235 1313.78
  5266.6    1317  5271.4 1317.48  5277.7 1319.65  5296.4 1322.08  5309.7 1323.16
  5326.6  1325.6  5351.5 1327.45  5363.1 1329.47  5395.2 1331.84  5427.2 1332.78
#Mann= 6 ,-1 , 0
    4900     .12       0    4992     .05       0  5002.9     .12       0
  5058.5     .07       0  5162.6     .12       0  5266.6     .07       0
Bank Sta=4992,5002.9
XS Rating Curve= 0 ,0
Exp/Cntr=0.3,0.1

Type RM Length L Ch R = 1 ,16092   ,456,456,456
BEGIN DESCRIPTION:
RAWLS CREEK 33.0
END DESCRIPTION:
XS GIS Cut Line= 3
      2111074.97     13902474.97        2110875.       13902275.
      2110624.96     13902174.98
#Sta/Elev= 30
  4716.9 1326.01    4731 1326.36  4759.3 1325.97  4787.6 1322.37  4815.8 1315.58
    4830 1311.07  4844.1 1307.53  4858.3  1306.6  4900.7 1305.49    4929 1305.88
  4964.3 1304.72  4971.4 1302.81  4990.7 1299.76  4991.2 1299.26  5001.2 1299.26
  5001.7 1299.76  5002.4 1299.76  5009.1 1304.24  5014.5 1305.34  5068.4 1306.29
  5075.1 1307.25  5128.9 1307.04  5139.7  1307.4  5170.7 1311.68  5182.8  1314.5
  5193.6 1316.15  5205.7 1319.32  5224.5 1323.38  5254.1 1326.79    5269 1327.32
#Mann= 3 ,-1 , 0
  4716.9     .12       0  4990.7     .05       0  5001.7     .12       0
Bank Sta=4990.7,5001.7
XS Rating Curve= 0 ,0
Exp/Cntr=0.3,0.1

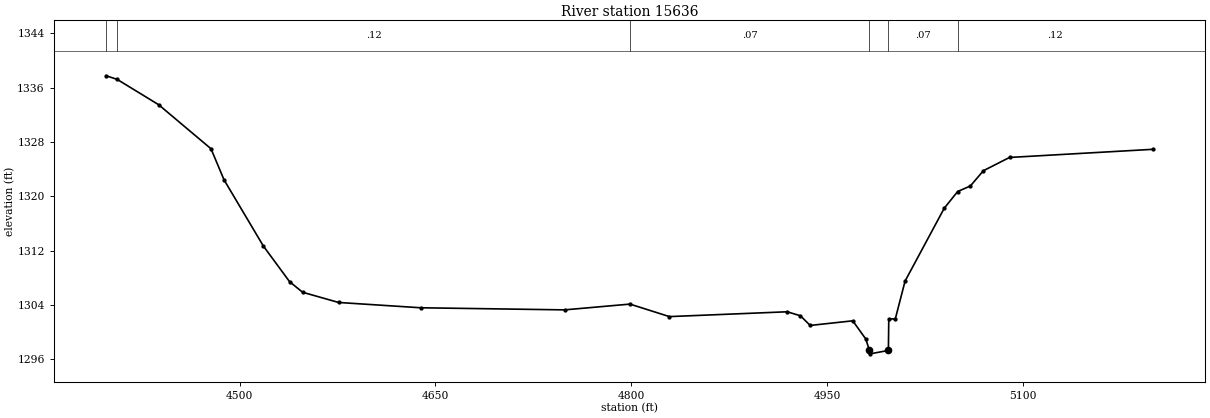
Type RM Length L Ch R = 1 ,15636   ,450,450,450
BEGIN DESCRIPTION:
RAWLS CREEK 32.0
END DESCRIPTION:
XS GIS Cut Line= 3
      2111425.02       13901825.        2110825.       13901875.
        2110625.       13901875.
#Sta/Elev= 30
  4397.8 1337.74  4406.2 1337.21    4438 1333.48  4478.1    1327  4488.1 1322.42
  4518.2 1312.69  4538.3 1307.44  4548.3 1305.88  4575.9 1304.38  4638.7  1303.6
    4749 1303.29  4799.1 1304.14  4829.3  1302.3  4919.6 1303.01  4929.7 1302.42
  4937.2    1301  4969.8 1301.68  4979.8    1299  4982.6 1297.32  4983.1 1296.82
  4997.1 1297.32  4997.4 1301.96  5002.4 1301.96  5009.9 1307.53  5039.9 1318.25
  5050.2 1320.71  5059.9 1321.52  5069.9 1323.77  5089.9 1325.72  5199.9 1326.92
#Mann= 6 ,-1 , 0
  4397.8     .07       0  4406.2     .12       0  4799.1     .07       0
  4982.6     .05       0  4997.1     .07       0  5050.2     .12       0
Bank Sta=4982.6,4997.1
XS Rating Curve= 0 ,0
Exp/Cntr=0.3,0.1