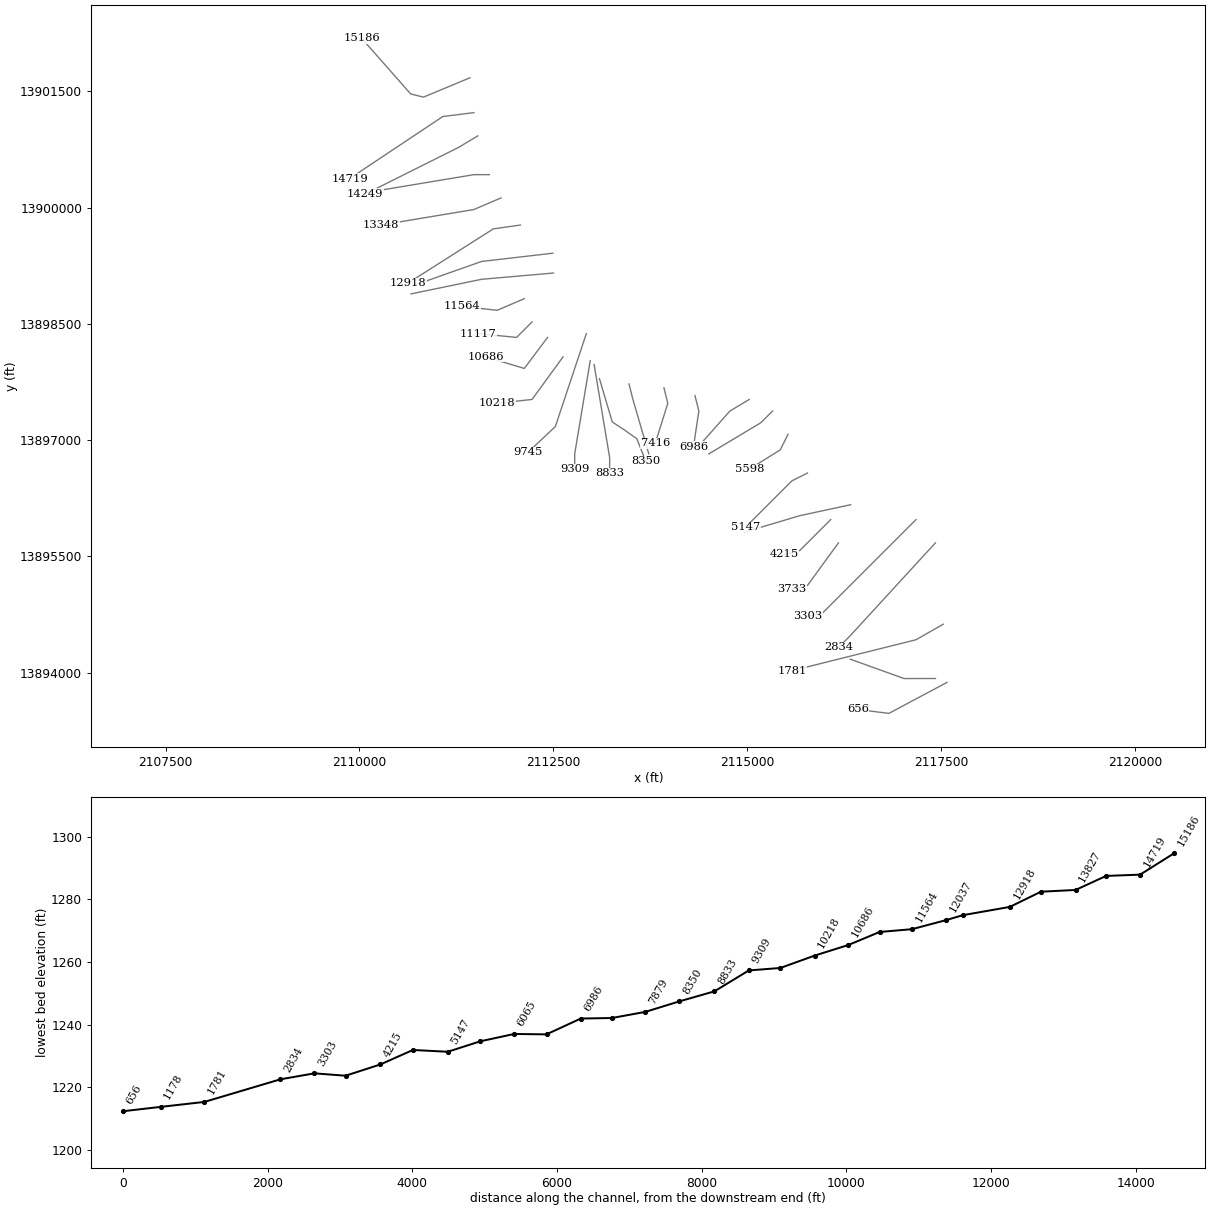
HEC-RAS study RAWLS CREEK.prj: RAWLS CREEK Base Level Engineering

--- RAWLS CREEK.g01 (geometry) --- (continued)

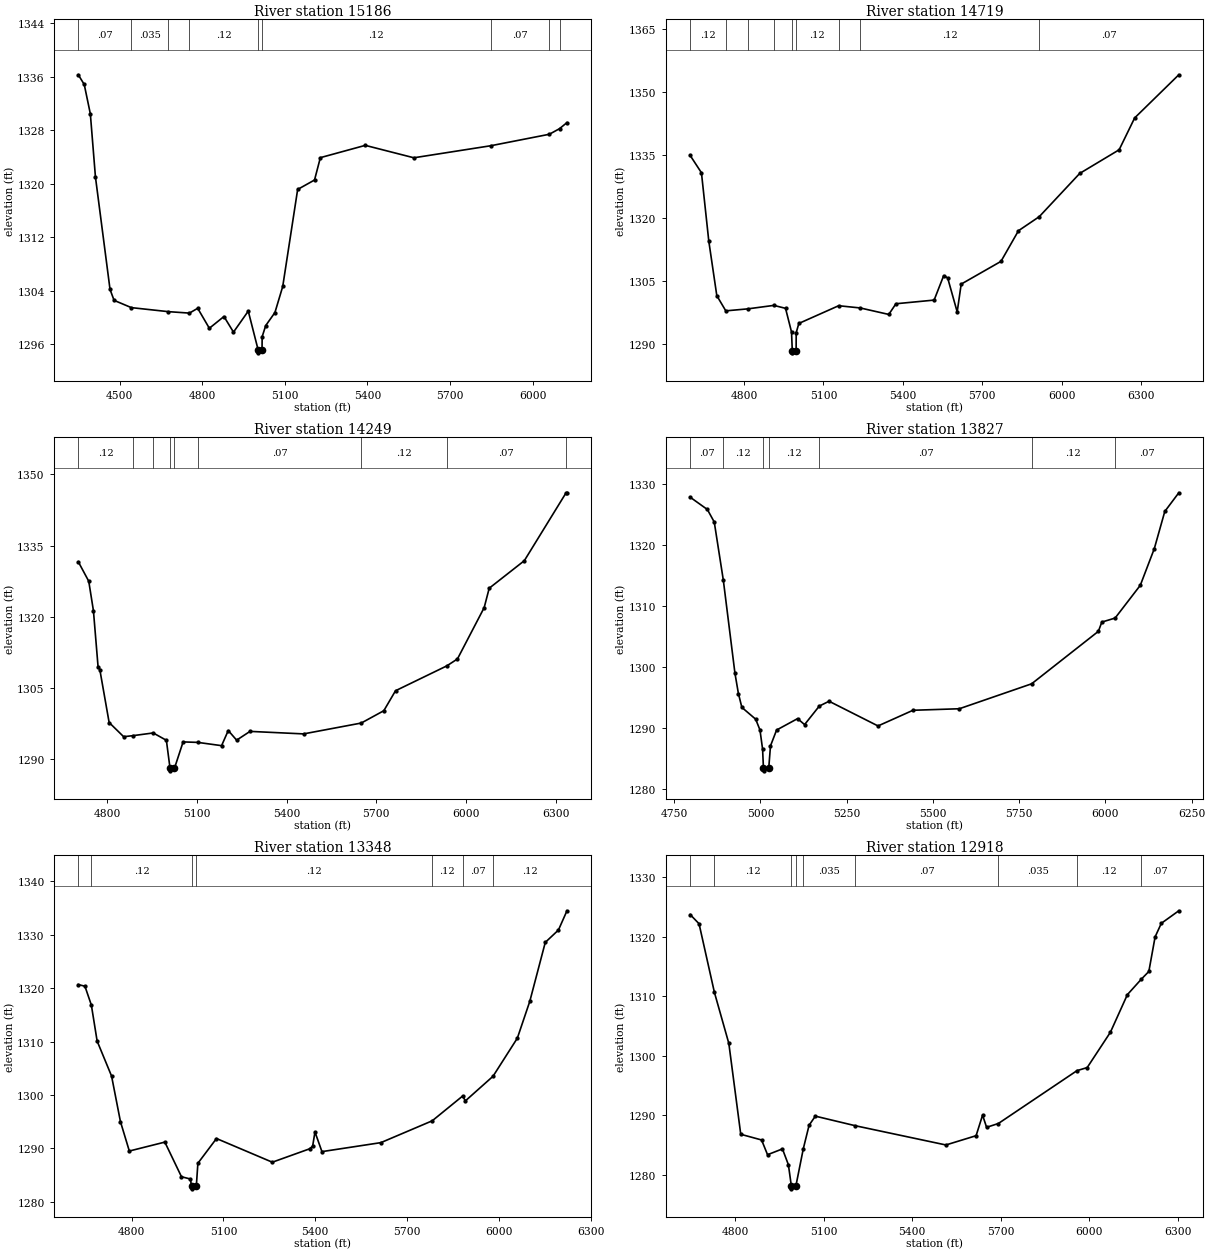
Type RM Length L Ch R = 1 ,15186   ,467,467,467
BEGIN DESCRIPTION:
RAWLS CREEK 31.0
END DESCRIPTION:
XS GIS Cut Line= 4
      2111424.97     13901674.99        2110825.       13901425.
      2110660.22      13901466.2      2110029.11     13902183.57
#Sta/Elev= 30
  4349.6 1336.32  4371.2 1334.87  4393.4 1330.47  4411.9 1321.02  4464.9 1304.18
  4479.6 1302.54  4542.4 1301.45  4676.3 1300.85  4753.3 1300.63  4783.4 1301.35
  4825.7 1298.36  4878.8 1300.12  4913.4 1297.78  4967.1 1300.93  5002.6 1295.18
  5003.1 1294.68  5017.1 1295.18  5017.6  1297.1  5030.5 1298.76    5064 1300.72
  5092.3 1304.62  5146.5 1319.15  5207.8 1320.56    5229 1323.91  5392.2 1325.75
  5568.7 1323.89  5847.6 1325.69  6060.7 1327.41  6097.9 1328.25  6124.9 1329.16
#Mann= 9 ,-1 , 0
  4349.6     .07       0  4542.4    .035       0  4676.3     .07       0
  4753.3     .12       0  5002.6     .05       0  5017.1     .12       0
  5847.6     .07       0  6060.7     .12       0  6097.9     .07       0
Bank Sta=5002.6,5017.1
XS Rating Curve= 0 ,0
Exp/Cntr=0.3,0.1

Type RM Length L Ch R = 1 ,14719   ,470,470,470
BEGIN DESCRIPTION:
RAWLS CREEK 30.0
END DESCRIPTION:
XS GIS Cut Line= 3
      2111474.99       13901225.        2111075.       13901175.
      2109875.02     13900375.01
#Sta/Elev= 30
  4596.5 1334.84  4639.3 1330.71    4667 1314.47  4697.3 1301.49  4731.2 1297.88
  4813.8 1298.35  4912.7 1299.18  4956.8 1298.48  4979.4 1292.86  4982.3  1288.4
  4982.8  1287.9  4996.8  1288.4  4997.1  1292.7  5007.1 1294.89  5157.4  1299.1
  5238.8 1298.57  5346.6 1297.03  5373.7 1299.57  5517.9 1300.44    5554 1306.26
    5569 1305.71    5605 1297.63  5620.1 1304.24  5770.3 1309.64  5836.4 1316.93
  5914.9 1320.27  6067.7 1330.55  6216.5 1336.17  6275.1 1343.74  6441.8    1354
#Mann= 9 ,-1 , 0
  4596.5     .12       0  4731.2     .07       0  4813.8    .035       0
  4912.7     .12       0  4982.3     .05       0  4996.8     .12       0
  5157.4     .07       0  5238.8     .12       0  5914.9     .07       0
Bank Sta=4982.3,4996.8
XS Rating Curve= 0 ,0
Exp/Cntr=0.3,0.1

Type RM Length L Ch R = 1 ,14249   ,422,422,422
BEGIN DESCRIPTION:
RAWLS CREEK 29.0
END DESCRIPTION:
XS GIS Cut Line= 3
      2111525.03     13900925.02        2111275.       13900775.
      2110075.02     13900175.01
#Sta/Elev= 30
  4704.1 1331.58  4739.1 1327.47  4754.7 1321.26  4770.2 1309.44  4776.1 1308.83
  4807.2 1297.68  4855.7 1294.69  4885.8  1294.9  4954.5 1295.48  4998.5 1293.93
  5010.8 1287.99  5011.3 1287.49  5025.3 1287.99  5054.4 1293.59  5103.4 1293.49
    5183  1292.8  5205.3 1295.99  5233.3 1293.96    5278 1295.81  5456.9 1295.28
  5649.8 1297.57  5725.2 1300.17  5764.3 1304.38  5935.6 1309.62  5971.2 1311.08
  6060.6 1321.91  6077.4    1326  6194.8 1331.81  6333.9 1346.08  6337.3 1346.13
#Mann= 9 ,-1 , 0
  4704.1     .12       0  4885.8     .07       0  4954.5     .12       0
  5010.8     .05       0  5025.3     .12       0  5103.4     .07       0
  5649.8     .12       0  5935.6     .07       0  6333.9     .12       0
Bank Sta=5010.8,5025.3
XS Rating Curve= 0 ,0
Exp/Cntr=0.3,0.1

Type RM Length L Ch R = 1 ,13827   ,479,479,479
BEGIN DESCRIPTION:
RAWLS CREEK 28.0
END DESCRIPTION:
XS GIS Cut Line= 3
      2111675.01       13900425.        2111475.       13900425.
      2110274.96     13900224.99
#Sta/Elev= 30
    4796 1327.88    4846 1325.86    4866  1323.8  4892.2  1314.3    4926 1298.99
    4936 1295.68    4946 1293.41    4986 1291.48  4998.5 1289.71  5006.1 1286.56
  5008.5 1283.51    5009 1283.01    5024 1283.51    5029 1287.11  5046.7  1289.7
  5107.5 1291.57  5127.8 1290.59  5170.5 1293.63  5198.8 1294.42  5340.7 1290.37
  5442.1 1292.94  5576.4 1293.19    5786 1297.28  5979.4 1305.88  5989.5  1307.4
    6028 1308.06    6101 1313.43  6141.6 1319.44    6172 1325.54  6212.6  1328.6
#Mann= 7 ,-1 , 0
    4796     .07       0  4892.2     .12       0  5008.5     .05       0
    5024     .12       0  5170.5     .07       0    5786     .12       0
    6028     .07       0
Bank Sta=5008.5,5024
XS Rating Curve= 0 ,0
Exp/Cntr=0.3,0.1

Type RM Length L Ch R = 1 ,13348   ,430,430,430
BEGIN DESCRIPTION:
RAWLS CREEK 27.0
END DESCRIPTION:
XS GIS Cut Line= 3
      2111824.98     13900124.99        2111475.       13899975.
      2110275.02       13899775.
#Sta/Elev= 30
  4625.6 1320.65  4647.3 1320.34  4668.3 1316.82  4687.2 1310.08  4734.4 1303.54
  4763.4 1295.02  4792.4 1289.52  4908.5 1291.19  4962.9 1284.71  4991.9 1284.29
  4995.9 1282.95  4996.4 1282.45  5011.4 1282.95  5016.5 1287.23  5077.3 1291.86
  5259.8 1287.43  5381.5 1289.93  5391.6 1290.43  5399.2 1293.09    5422 1289.41
  5614.6 1291.09  5782.4 1295.17  5881.8  1299.8  5890.9  1298.9  5981.2  1303.5
  6060.7 1310.63  6101.3  1317.5    6152 1328.54    6195 1330.85  6222.9 1334.45
#Mann= 7 ,-1 , 0
  4625.6    .035       0  4668.3     .12       0  4995.9     .05       0
  5011.4     .12       0  5782.4     .12       0  5881.8     .07       0
  5981.2     .12       0
Bank Sta=4995.9,5011.4
XS Rating Curve= 0 ,0
Exp/Cntr=0.3,0.1

Type RM Length L Ch R = 1 ,12918   ,651,651,651
BEGIN DESCRIPTION:
RAWLS CREEK 26.0
END DESCRIPTION:
XS GIS Cut Line= 3
        2112075.       13899775.        2111725.       13899725.
      2110624.99       13899025.
#Sta/Elev= 30
  4646.8 1323.75  4677.1  1322.2  4729.2 1310.65  4778.1 1302.07  4818.5 1286.78
  4889.2 1285.82  4909.4 1283.34  4959.9 1284.32  4980.1 1281.66  4990.1  1278.1
  4990.6  1277.6  5005.6  1278.1  5030.7 1284.35  5050.3  1288.3  5071.5 1289.83
  5207.7 1288.21  5514.3 1284.98  5616.7 1286.54  5638.7    1290  5652.3 1287.95
  5692.2 1288.59  5959.1 1297.49  5993.5    1298  6072.2 1303.94  6129.8 1310.27
  6176.5 1312.84  6202.6 1314.17  6223.8 1319.98  6244.9 1322.27  6304.2 1324.38
#Mann= 9 ,-1 , 0
  4646.8     .07       0  4729.2     .12       0  4990.1     .05       0
  5005.6     .12       0  5030.7    .035       0  5207.7     .07       0
  5692.2    .035       0  5959.1     .12       0  6176.5     .07       0
Bank Sta=4990.1,5005.6
XS Rating Curve= 0 ,0
Exp/Cntr=0.3,0.1

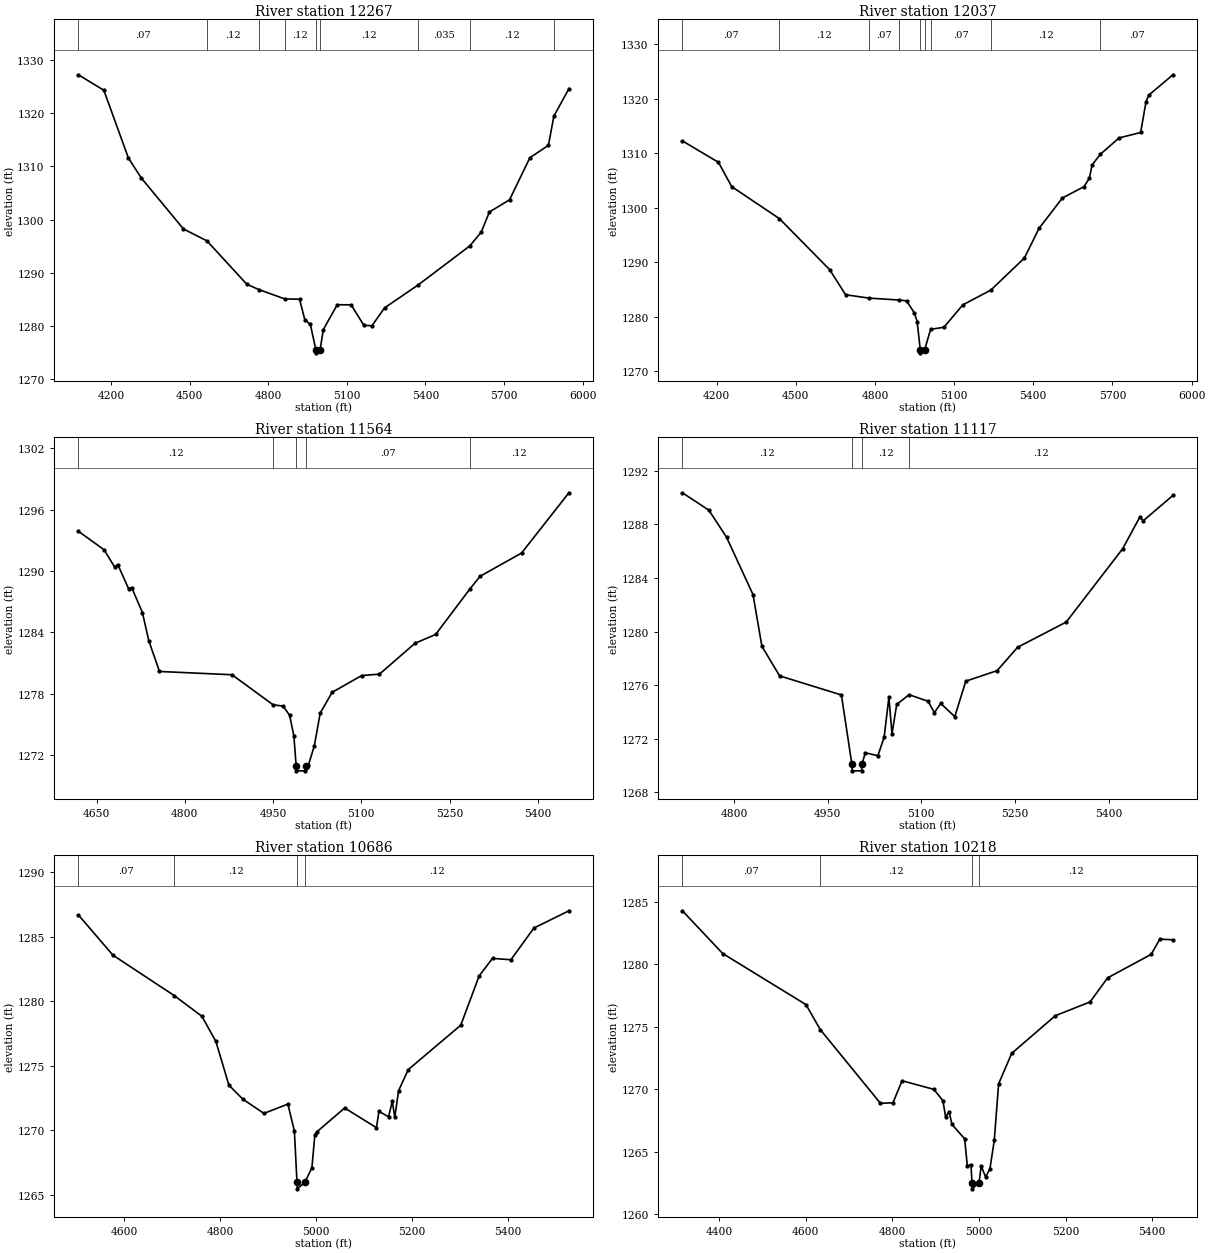
Type RM Length L Ch R = 1 ,12267   ,230,230,230
BEGIN DESCRIPTION:
Rawlins Creek 25.0
END DESCRIPTION:
XS GIS Cut Line= 3
      2112493.36     13899411.56      2111574.41     13899304.97
      2110681.29     13898989.84
#Sta/Elev= 30
  4075.2  1327.2  4172.4 1324.29  4266.1 1311.56  4315.2 1307.81  4476.2 1298.23
  4565.9 1295.99  4717.8 1287.85  4763.9 1286.84  4862.5 1285.09  4919.2 1285.03
  4939.3 1281.21  4960.6 1280.28  4981.9 1275.45  4982.4 1274.95  4997.5 1275.45
  5010.1 1279.33  5063.3 1283.99  5116.3 1283.97  5164.8 1280.12  5195.7 1280.04
  5243.6 1283.39  5373.2 1287.75  5569.3 1295.05  5612.9 1297.64  5643.8 1301.41
  5720.8 1303.71  5798.5 1311.62  5869.2 1313.94  5890.1 1319.44  5947.4 1324.59
#Mann= 9 ,-1 , 0
  4075.2     .07       0  4565.9     .12       0  4763.9     .07       0
  4862.5     .12       0  4981.9     .05       0  4997.5     .12       0
  5373.2    .035       0  5569.3     .12       0  5890.1     .07       0
Bank Sta=4981.9,4997.5
XS Rating Curve= 0 ,0
Exp/Cntr=0.3,0.1

Type RM Length L Ch R = 1 ,12037   ,473,473,473
BEGIN DESCRIPTION:
RAWLS CREEK 24.0
END DESCRIPTION:
XS GIS Cut Line= 3
       2112501.2     13899155.84        2111575.       13899075.
      2110665.19     13898886.73
#Sta/Elev= 30
  4070.2 1312.24  4206.9 1308.31  4257.2 1303.85  4437.8 1297.99  4628.5 1288.62
  4688.7 1284.03  4776.2 1283.42  4892.6 1283.06  4919.6 1282.91  4949.7 1280.67
  4959.8 1279.11  4971.8 1273.88  4972.3 1273.38  4987.8 1273.88  5010.9 1277.69
  5061.2 1278.07  5132.7 1282.17  5238.9 1284.88  5366.2 1290.76  5421.5 1296.19
  5510.5 1301.78  5592.2 1303.85  5612.2 1305.38  5622.8 1307.83    5654 1309.79
    5725 1312.78  5806.7 1313.78  5827.1 1319.41  5837.3 1320.62    5929 1324.36
#Mann= 9 ,-1 , 0
  4070.2     .07       0  4437.8     .12       0  4776.2     .07       0
  4892.6     .12       0  4971.8     .05       0  4987.8     .12       0
  5010.9     .07       0  5238.9     .12       0    5654     .07       0
Bank Sta=4971.8,4987.8
XS Rating Curve= 0 ,0
Exp/Cntr=0.3,0.1

Type RM Length L Ch R = 1 ,11564   ,447,447,447
BEGIN DESCRIPTION:
RAWLS CREEK 23.0
END DESCRIPTION:
XS GIS Cut Line= 3
      2112124.96     13898824.98        2111775.       13898675.
      2111325.02       13898725.
#Sta/Elev= 30
  4619.2 1293.89  4662.7 1292.09  4680.8  1290.4  4686.3 1290.62  4704.4 1288.29
  4709.8 1288.39    4728 1285.95  4738.8  1283.2    4757 1280.19  4880.3 1279.87
  4949.9 1276.94  4967.3  1276.8  4978.2 1275.89  4985.4 1273.88  4989.2 1270.98
  4989.7 1270.48  5004.7 1270.48  5005.2 1270.98    5010 1271.03  5020.1 1272.92
  5030.1 1276.12  5050.3 1278.15  5100.6 1279.79  5130.8 1279.93  5191.1 1282.94
  5226.3 1283.81  5284.3 1288.24  5301.8 1289.49  5372.2 1291.76  5452.7 1297.65
#Mann= 5 ,-1 , 0
  4619.2     .12       0  4949.9     .07       0  4989.2     .05       0
  5005.2     .07       0  5284.3     .12       0
Bank Sta=4989.2,5005.2
XS Rating Curve= 0 ,0
Exp/Cntr=0.3,0.1

Type RM Length L Ch R = 1 ,11117   ,431,431,431
BEGIN DESCRIPTION:
RAWLS CREEK 22.0
END DESCRIPTION:
XS GIS Cut Line= 3
        2112225.       13898525.        2112025.       13898325.
      2111525.04       13898375.
#Sta/Elev= 30
  4717.4 1290.37  4759.8 1289.07  4788.1 1287.05  4830.5 1282.76  4844.7  1278.9
    4873 1276.69    4972 1275.26  4988.7 1270.09  4989.2 1269.59  5004.3 1269.59
  5004.8 1270.09  5010.3 1270.94  5030.4 1270.72  5040.4  1272.1    5048 1275.08
    5053 1272.36  5060.5 1274.55  5080.2 1275.28  5110.8 1274.79  5120.8 1273.93
  5130.9 1274.63  5153.5 1273.64  5171.1 1276.29  5221.3 1277.08    5254 1278.82
  5331.9 1280.71  5422.3 1286.19    5450 1288.58    5455 1288.27  5502.7 1290.17
#Mann= 4 ,-1 , 0
  4717.4     .12       0  4988.7     .05       0  5004.8     .12       0
  5080.2     .12       0
Bank Sta=4988.7,5004.8
XS Rating Curve= 0 ,0
Exp/Cntr=0.3,0.1

Type RM Length L Ch R = 1 ,10686   ,468,468,468
BEGIN DESCRIPTION:
RAWLS CREEK 21.0
END DESCRIPTION:
XS GIS Cut Line= 3
      2112425.01     13898325.01        2112125.       13897925.
      2111625.03     13898074.99
#Sta/Elev= 30
  4504.9 1286.68  4576.8 1283.56  4704.8 1280.42  4762.2 1278.82  4791.4 1276.87
  4818.5 1273.48  4847.6 1272.39  4891.4 1271.29  4941.4 1272.01  4954.9 1269.93
  4960.4 1265.94  4960.9 1265.44  4976.6 1265.94  4991.4 1267.06  4997.6 1269.64
  5001.8 1269.86  5059.7 1271.71  5125.9 1270.18  5131.1 1271.45  5151.1 1271.03
  5158.9 1272.22  5164.1 1270.99    5172 1273.04    5192 1274.68  5301.6 1278.13
  5339.9 1281.95  5367.7 1283.31    5406  1283.2  5453.9 1285.66  5526.9    1287
#Mann= 4 ,-1 , 0
  4504.9     .07       0  4704.8     .12       0  4960.4     .05       0
  4976.6     .12       0
Bank Sta=4960.4,4976.6
XS Rating Curve= 0 ,0
Exp/Cntr=0.3,0.1

Type RM Length L Ch R = 1 ,10218   ,473,473,473
BEGIN DESCRIPTION:
RAWLS CREEK 20.0
END DESCRIPTION:
XS GIS Cut Line= 3
      2112624.97     13898074.96        2112225.       13897525.
        2111775.       13897475.
#Sta/Elev= 30
  4315.1 1284.29  4408.2 1280.87  4600.6 1276.78  4633.6 1274.78  4772.6 1268.88
  4801.5 1268.93  4822.4 1270.69  4895.8    1270  4916.7  1269.1  4922.9 1267.82
  4931.4 1268.19  4937.6 1267.19  4966.9 1266.05  4973.1 1263.89  4981.6 1263.96
  4983.9 1262.54  4984.4 1262.04  5000.2 1262.54  5005.2 1263.87  5015.3 1262.99
  5025.3 1263.63  5035.4 1265.93  5045.4 1270.44  5075.6 1272.88  5176.2 1275.89
  5256.7    1277    5297 1278.92  5397.6  1280.8  5417.7 1282.02  5447.9 1281.97
#Mann= 4 ,-1 , 0
  4315.1     .07       0  4633.6     .12       0  4983.9     .05       0
  5000.2     .12       0
Bank Sta=4983.9,5000.2
XS Rating Curve= 0 ,0
Exp/Cntr=0.3,0.1

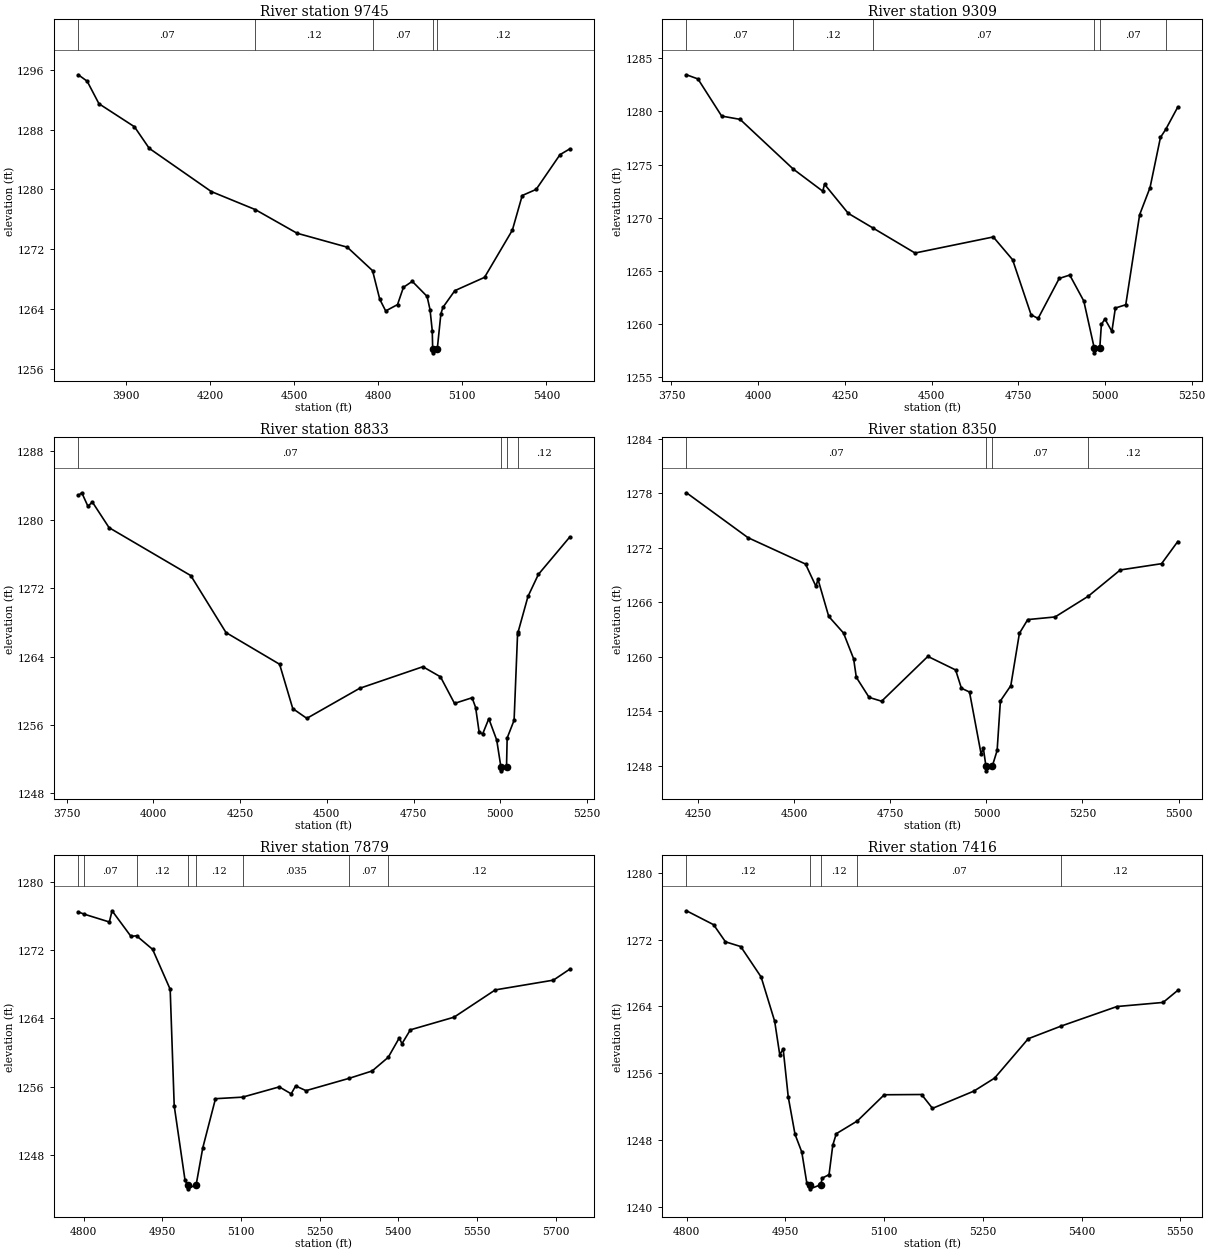
Type RM Length L Ch R = 1 ,9745    ,436,436,436
BEGIN DESCRIPTION:
RAWLS CREEK 19.0
END DESCRIPTION:
XS GIS Cut Line= 3
      2112924.99     13898374.96        2112525.       13897175.
      2112170.54     13896840.85
#Sta/Elev= 30
  3730.4 1295.34    3762 1294.48  3804.1 1291.46  3930.6 1288.38  3983.3 1285.49
  4204.7  1279.7  4361.3 1277.29  4510.4 1274.12  4689.6 1272.25  4779.7 1269.11
  4805.5 1265.27  4826.6 1263.71  4868.8 1264.56  4889.9 1266.88  4921.5 1267.67
  4974.2 1265.66  4984.7 1263.89  4992.6 1261.09  4994.2  1258.6  4994.7  1258.1
  5010.5  1258.6  5023.4 1263.32  5030.7 1264.19  5073.2 1266.43  5179.1 1268.21
  5278.3 1274.53  5313.5 1279.17  5363.2 1279.99  5448.2 1284.64  5482.4  1285.4
#Mann= 5 ,-1 , 0
  3730.4     .07       0  4361.3     .12       0  4779.7     .07       0
  4994.2     .05       0  5010.5     .12       0
Bank Sta=4994.2,5010.5
XS Rating Curve= 0 ,0
Exp/Cntr=0.3,0.1

Type RM Length L Ch R = 1 ,9309    ,476,476,476
BEGIN DESCRIPTION:
RAWLS CREEK 18.0
END DESCRIPTION:
XS GIS Cut Line= 3
      2112975.01     13898025.04        2112775.       13896825.
        2112775.     13896624.99
#Sta/Elev= 30
  3793.3 1283.44  3826.3 1283.05  3894.7 1279.56  3947.9 1279.25  4101.1 1274.58
  4186.2  1272.5  4191.3 1273.15  4259.7 1270.42  4332.1 1269.02  4452.3 1266.69
  4677.9  1268.2  4733.6 1266.06  4786.9 1260.89  4807.1 1260.54    4868  1264.3
  4898.4 1264.62  4938.9 1262.18  4968.7 1257.81  4969.2 1257.31  4985.1 1257.81
  4989.6 1259.98  4999.8 1260.49  5019.9 1259.33  5029.9 1261.52  5059.9 1261.83
  5099.9 1270.29  5129.9 1272.84  5159.9 1277.55  5175.2 1278.31  5209.9 1280.41
#Mann= 6 ,-1 , 0
  3793.3     .07       0  4101.1     .12       0  4332.1     .07       0
  4968.7     .05       0  4985.1     .07       0  5175.2     .12       0
Bank Sta=4968.7,4985.1
XS Rating Curve= 0 ,0
Exp/Cntr=0.3,0.1

Type RM Length L Ch R = 1 ,8833    ,483,483,483
BEGIN DESCRIPTION:
RAWLS CREEK 17.0
END DESCRIPTION:
XS GIS Cut Line= 3
      2113025.01     13897974.97        2113225.       13896775.
        2113225.     13896575.02
#Sta/Elev= 30
  3783.4 1282.85  3793.5 1283.16  3811.2 1281.58  3823.9 1282.08  3872.1 1279.08
  4107.8 1273.47  4209.2 1266.81  4363.8  1263.1  4401.8 1257.91  4442.3 1256.77
  4594.4 1260.28  4776.9 1262.81  4827.6 1261.63  4868.1 1258.52  4918.8 1259.18
    4929 1258.04  4939.1 1255.16  4949.2 1254.94    4967 1256.73  4989.8 1254.23
  5001.7 1251.13  5002.2 1250.63  5018.1 1251.13  5019.9 1254.47  5039.9 1256.55
  5049.9 1266.63  5051.4 1266.86  5079.9 1271.03  5109.9 1273.61  5199.9 1277.96
#Mann= 4 ,-1 , 0
  3783.4     .07       0  5001.7     .05       0  5018.1     .07       0
  5051.4     .12       0
Bank Sta=5001.7,5018.1
XS Rating Curve= 0 ,0
Exp/Cntr=0.3,0.1

Type RM Length L Ch R = 1 ,8350    ,471,471,471
BEGIN DESCRIPTION:
RAWLS CREEK 16.0
END DESCRIPTION:
XS GIS Cut Line= 5
      2113094.18     13897792.21      2113259.01     13897234.48
        2113425.       13897125.      2113576.72     13897015.73
      2113690.66      13896725.7
#Sta/Elev= 30
  4219.1 1278.03  4379.3 1273.09    4529 1270.19  4556.1 1267.74  4561.4 1268.51
  4589.4 1264.43  4627.9  1262.6  4654.2 1259.77  4661.2 1257.73  4694.5 1255.52
  4727.1  1255.1  4847.5 1260.03  4919.7 1258.54  4934.8 1256.53  4955.9 1256.11
    4986 1249.31    4992 1249.91  4998.7 1247.94  4999.2 1247.44  5015.1 1247.94
  5027.8 1249.68  5036.3 1255.13  5063.4 1256.81  5085.8 1262.57  5107.5 1264.08
  5178.7 1264.37  5264.7 1266.64  5348.4 1269.54  5455.9 1270.23  5498.1 1272.67
#Mann= 4 ,-1 , 0
  4219.1     .07       0  4998.7     .05       0  5015.1     .07       0
  5264.7     .12       0
Bank Sta=4998.7,5015.1
XS Rating Curve= 0 ,0
Exp/Cntr=0.3,0.1

Type RM Length L Ch R = 1 ,7879    ,463,463,463
BEGIN DESCRIPTION:
RAWLS CREEK 15.0
END DESCRIPTION:
XS GIS Cut Line= 3
      2113475.01     13897724.97        2113525.       13897525.
      2113729.57     13896823.54
#Sta/Elev= 30
    4790 1276.46  4800.4 1276.21  4849.2 1275.28  4854.4 1276.59  4890.5 1273.59
    4901 1273.67  4931.7 1272.08  4965.2 1267.41  4972.9 1253.79  4993.5 1245.09
  4998.3 1244.58  4998.8 1244.08  5014.8 1244.58  5027.4 1248.88  5051.6 1254.62
  5103.2  1254.8  5173.2    1256  5195.9 1255.19  5204.5 1256.11  5224.2 1255.56
  5306.4    1257  5350.3 1257.86    5381 1259.46    5402 1261.72  5407.2 1261.05
  5423.2 1262.67  5506.5 1264.15  5585.1 1267.34  5695.9 1268.48  5726.8 1269.75
#Mann= 8 ,-1 , 0
    4790     .12       0  4800.4     .07       0    4901     .12       0
  4998.3     .05       0  5014.8     .12       0  5103.2    .035       0
  5306.4     .07       0    5381     .12       0
Bank Sta=4998.3,5014.8
XS Rating Curve= 0 ,0
Exp/Cntr=0.3,0.1

Type RM Length L Ch R = 1 ,7416    ,430,430,430
BEGIN DESCRIPTION:
RAWLS CREEK 14.0
END DESCRIPTION:
XS GIS Cut Line= 3
      2113925.01     13897674.97        2113975.       13897475.
      2113813.08     13896959.46
#Sta/Elev= 30
  4799.8 1275.46    4841 1273.79    4859 1271.74  4882.2 1271.17  4913.2 1267.52
  4933.8 1262.21  4941.5  1258.2  4946.7 1258.89  4954.4 1253.15  4964.7 1248.66
    4975 1246.53  4982.7 1242.78  4987.3 1242.62  4987.8 1242.12  5003.9 1242.62
  5005.9  1243.4  5016.4 1243.82  5022.1 1247.36  5027.4 1248.73  5059.4 1250.26
  5100.3  1253.4    5157 1253.43  5173.6 1251.77  5236.5 1253.84    5268  1255.4
  5319.1 1260.12  5369.2 1261.64  5453.9 1263.98    5524 1264.47  5546.3 1265.92
#Mann= 5 ,-1 , 0
  4799.8     .12       0  4987.3     .05       0  5003.9     .12       0
  5059.4     .07       0  5369.2     .12       0
Bank Sta=4987.3,5003.9
XS Rating Curve= 0 ,0
Exp/Cntr=0.3,0.1

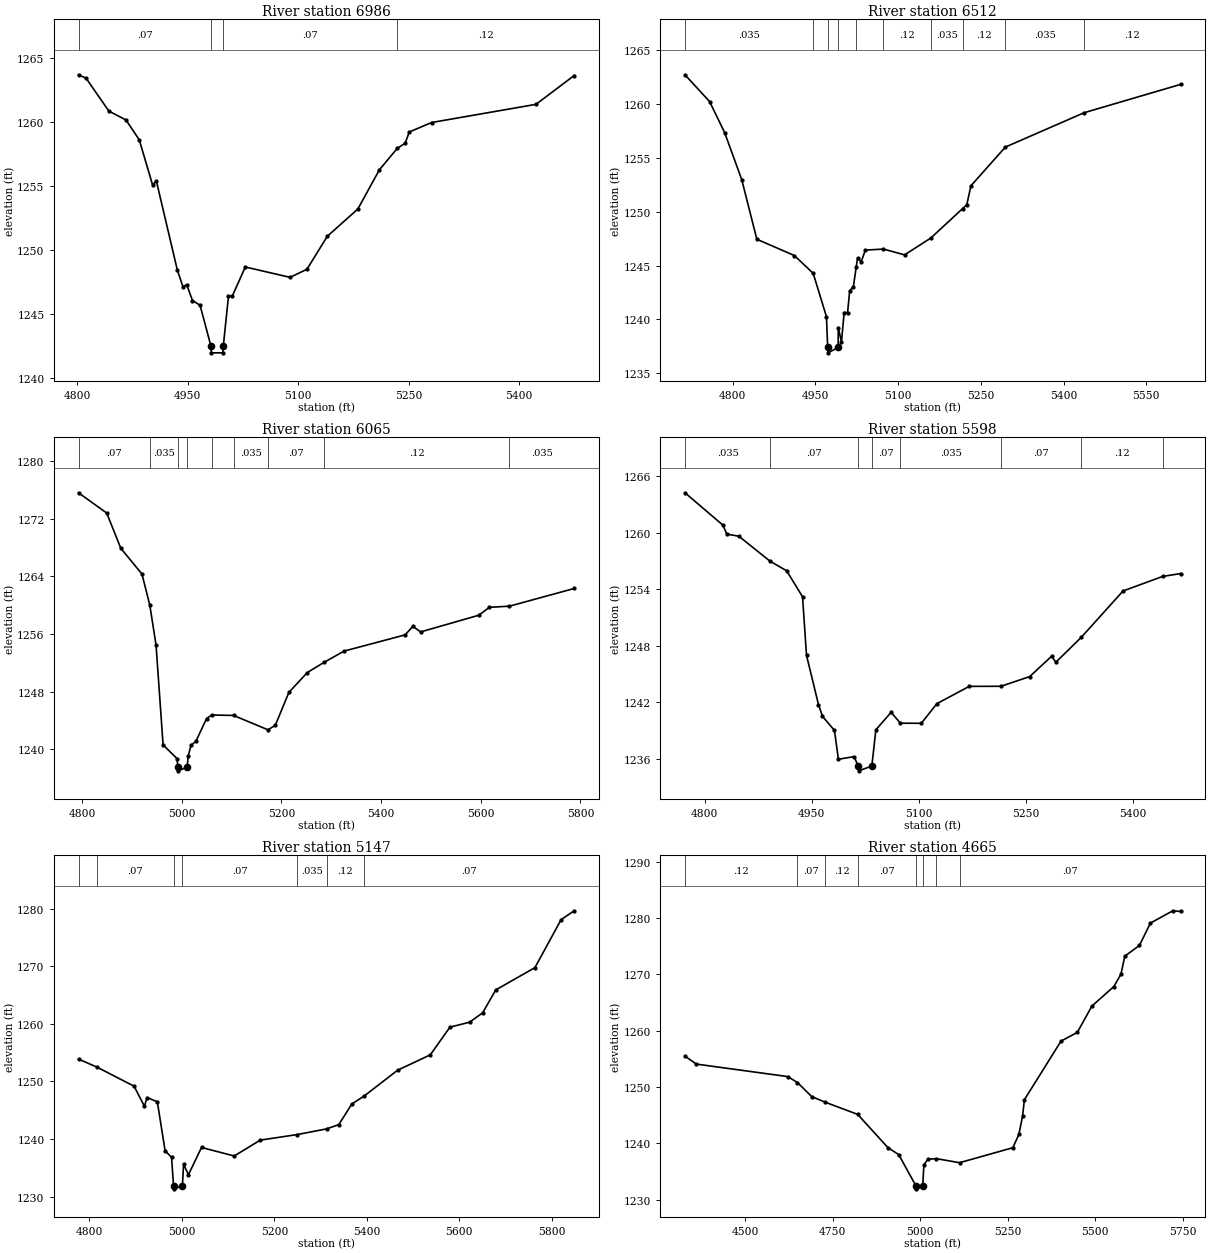
Type RM Length L Ch R = 1 ,6986    ,474,474,474
BEGIN DESCRIPTION:
RAWLS CREEK 13.0
END DESCRIPTION:
XS GIS Cut Line= 3
      2114325.01     13897574.96        2114375.       13897375.
      2114305.96     13896913.75
#Sta/Elev= 30
    4802 1263.68  4812.3 1263.41  4843.2 1260.84  4866.4 1260.15  4884.4  1258.6
  4902.5 1255.07  4907.6 1255.39    4936 1248.44  4943.7 1247.11  4948.8 1247.28
  4956.6 1246.04  4966.9 1245.67  4981.8 1242.45  4982.3 1241.95  4997.9 1241.95
  4998.4 1242.45  5005.5 1246.38  5010.6 1246.38  5028.3 1248.66    5089 1247.85
  5111.9 1248.48  5139.6 1251.06    5181 1253.19  5210.3 1256.26  5234.5 1257.93
  5245.2 1258.33  5250.8 1259.21  5281.1 1259.95  5422.7 1261.37  5474.5 1263.62
#Mann= 4 ,-1 , 0
    4802     .07       0  4981.8     .05       0  4998.4     .07       0
  5234.5     .12       0
Bank Sta=4981.8,4998.4
XS Rating Curve= 0 ,0
Exp/Cntr=0.3,0.1

Type RM Length L Ch R = 1 ,6512    ,447,447,447
BEGIN DESCRIPTION:
RAWLS CREEK 12.0
END DESCRIPTION:
XS GIS Cut Line= 3
      2115025.03     13897525.02        2114775.       13897375.
      2114371.93     13896920.72
#Sta/Elev= 30
  4713.3  1262.7    4758 1260.21  4785.2 1257.34  4816.3 1252.96  4843.6 1247.44
  4911.6 1245.93  4945.8 1244.28  4969.9 1240.25  4972.1  1237.4  4972.6  1236.9
  4991.1  1237.4  4991.3 1239.25  4997.1 1237.92    5002 1240.64  5008.2 1240.64
    5012 1242.66  5018.7 1243.04  5023.9 1244.87  5026.2 1245.68  5032.9 1245.35
  5040.4 1246.43  5073.3 1246.53  5111.5 1245.99  5159.1 1247.55  5216.9 1250.29
  5224.4 1250.65  5231.9  1252.4  5294.3 1255.99  5437.2 1259.18  5612.2 1261.81
#Mann= 10 ,-1 , 0
  4713.3    .035       0  4945.8     .12       0  4972.1     .05       0
  4991.1     .12       0  5023.9    .035       0  5073.3     .12       0
  5159.1    .035       0  5216.9     .12       0  5294.3    .035       0
  5437.2     .12       0
Bank Sta=4972.1,4991.1
XS Rating Curve= 0 ,0
Exp/Cntr=0.3,0.1

Type RM Length L Ch R = 1 ,6065    ,467,467,467
BEGIN DESCRIPTION:
RAWLS CREEK 11.0
END DESCRIPTION:
XS GIS Cut Line= 3
      2115325.01     13897375.01        2115175.       13897225.
      2114503.91     13896822.65
#Sta/Elev= 30
  4792.9 1275.57  4849.5 1272.76  4877.8 1267.87  4920.2 1264.31  4935.9 1260.01
  4948.5 1254.46  4962.6 1240.62  4990.9 1238.69    4992 1237.52  4992.5 1237.02
    5011 1237.52  5012.8 1239.01  5018.6 1240.56  5028.4 1241.11  5049.8 1244.26
  5060.2 1244.76  5104.1  1244.7    5173 1242.71  5187.8 1243.33    5215 1247.89
  5251.9 1250.64  5285.9 1252.07  5325.8 1253.62  5448.3 1255.87  5463.8 1257.05
  5479.4 1256.28    5596 1258.59  5617.4 1259.69  5657.7 1259.85  5787.5  1262.3
#Mann= 9 ,-1 , 0
  4792.9     .07       0  4935.9    .035       0    4992    .035       0
    5011    .035       0  5060.2     .07       0  5104.1    .035       0
    5173     .07       0  5285.9     .12       0  5657.7    .035       0
Bank Sta=4992,5011
XS Rating Curve= 0 ,0
Exp/Cntr=0.3,0.1

Type RM Length L Ch R = 1 ,5598    ,451,451,451
BEGIN DESCRIPTION:
RAWLS CREEK 10.0
END DESCRIPTION:
XS GIS Cut Line= 3
      2115525.01     13897075.02        2115425.       13896875.
      2115025.02     13896625.01
#Sta/Elev= 30
  4772.1 1264.22  4825.2 1260.79  4830.8 1259.83  4847.6 1259.61  4891.5 1256.95
  4914.7 1255.94    4937 1253.18  4942.6 1246.95  4959.4 1241.72    4965 1240.48
  4981.8 1238.98  4987.3 1235.92  5009.3  1236.2  5015.1 1235.19  5015.6 1234.69
  5034.2 1235.19  5039.9 1239.05  5061.2  1240.9  5074.4 1239.75  5103.6 1239.74
  5125.4 1241.82  5170.8 1243.66  5215.4 1243.67  5255.7  1244.7  5286.4 1246.86
  5292.3 1246.22  5328.3 1248.89  5386.6 1253.79  5442.3 1255.34  5467.4 1255.64
#Mann= 8 ,-1 , 0
  4772.1    .035       0  4891.5     .07       0  5015.1     .05       0
  5034.2     .07       0  5074.4    .035       0  5215.4     .07       0
  5328.3     .12       0  5442.3     .07       0
Bank Sta=5015.1,5034.2
XS Rating Curve= 0 ,0
Exp/Cntr=0.3,0.1

Type RM Length L Ch R = 1 ,5147    ,482,482,482
BEGIN DESCRIPTION:
RAWLS CREEK 9.0
END DESCRIPTION:
XS GIS Cut Line= 3
      2115775.02     13896575.01        2115575.       13896475.
      2114974.97     13895874.97
#Sta/Elev= 30
  4776.4  1253.9    4817 1252.47  4896.6 1249.18    4919 1245.69  4924.6 1247.21
  4946.9 1246.47  4963.7 1237.97  4977.7  1236.8    4982 1231.84  4982.5 1231.34
  5001.2 1231.84  5003.6 1235.61  5014.2 1233.79  5042.5 1238.53  5113.2 1237.05
  5169.7 1239.81  5250.1 1240.78  5312.9 1241.76  5339.4  1242.5  5367.7 1246.09
  5393.6 1247.43  5466.7 1251.96  5537.4 1254.63  5579.9 1259.44  5622.3  1260.3
  5650.6 1261.93  5678.9 1265.91  5763.7 1269.79  5820.3 1278.12  5848.6 1279.67
#Mann= 7 ,-1 , 0
  4776.4    .035       0    4817     .07       0    4982     .05       0
  5001.2     .07       0  5250.1    .035       0  5312.9     .12       0
  5393.6     .07       0
Bank Sta=4982,5001.2
XS Rating Curve= 0 ,0
Exp/Cntr=0.3,0.1

Type RM Length L Ch R = 1 ,4665    ,450,450,450
BEGIN DESCRIPTION:
RAWLS CREEK 8.0
END DESCRIPTION:
XS GIS Cut Line= 3
      2116331.97     13896166.78        2115675.       13896025.
      2114962.16     13895812.62
#Sta/Elev= 30
    4328 1255.48  4360.4 1254.06  4621.6 1251.84  4649.4 1250.78    4690 1248.29
  4728.6 1247.29  4821.3 1245.13    4908 1239.21  4938.7 1237.98  4987.9 1232.41
  4988.4 1231.91  5007.1 1232.41  5010.5 1236.18  5021.9 1237.16  5046.4 1237.27
  5112.3 1236.55  5264.5 1239.21  5281.8 1241.57  5292.3  1244.8  5297.6 1247.74
  5402.3 1258.14  5448.8 1259.69  5490.5 1264.37  5553.1 1267.82  5573.4 1270.02
  5584.4 1273.22  5626.2 1275.12  5657.5 1279.09  5721.7 1281.28  5743.9 1281.16
#Mann= 8 ,-1 , 0
    4328     .12       0  4649.4     .07       0  4728.6     .12       0
  4821.3     .07       0  4987.9     .05       0  5007.1     .07       0
  5046.4    .035       0  5112.3     .07       0
Bank Sta=4987.9,5007.1
XS Rating Curve= 0 ,0
Exp/Cntr=0.3,0.1

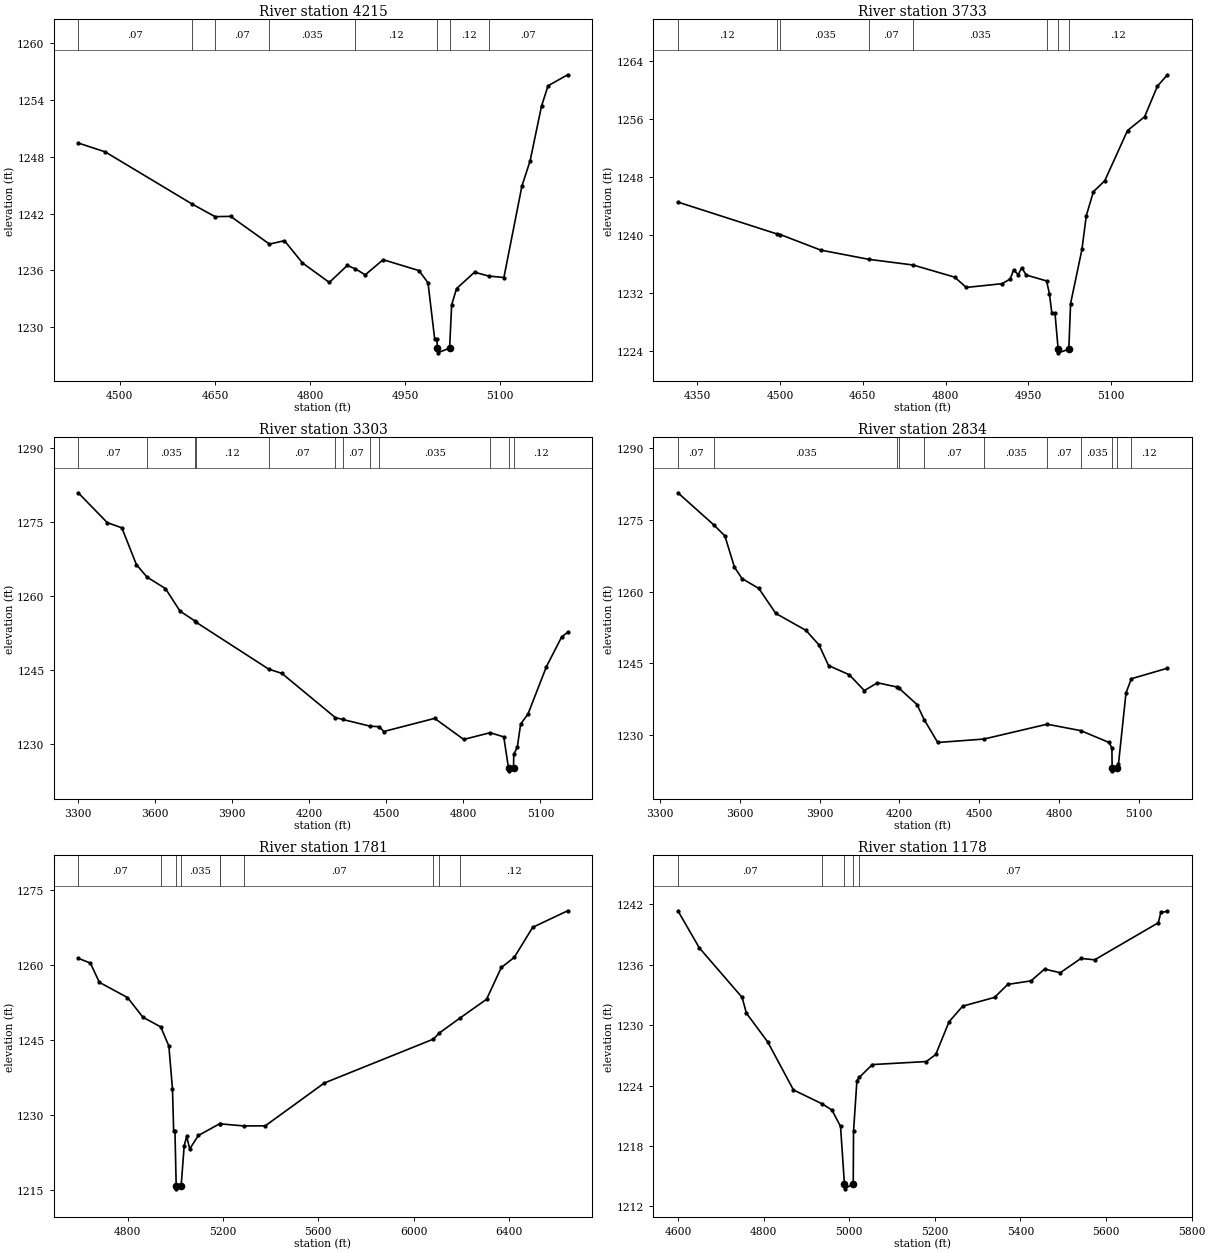
Type RM Length L Ch R = 1 ,4215    ,482,482,482
BEGIN DESCRIPTION:
RAWLS CREEK 7.0
END DESCRIPTION:
XS GIS Cut Line= 3
      2116075.01     13895975.01        2115675.       13895575.
      2115474.95     13895524.99
#Sta/Elev= 30
  4434.3 1249.46  4476.7 1248.53    4614 1243.01  4650.1 1241.68  4674.7 1241.71
  4735.9 1238.78  4759.6 1239.14  4787.9 1236.79  4830.3 1234.73  4858.6 1236.52
  4871.2 1236.17  4886.9 1235.53  4915.1 1237.13  4971.7 1235.98  4985.9 1234.69
  4996.5 1228.72    5000 1228.72  5000.7 1227.79  5001.2 1227.29    5020 1227.79
  5023.2 1232.36  5030.9 1234.08  5059.3 1235.81  5081.8  1235.4  5105.6 1235.25
    5134 1244.91  5146.9 1247.57  5164.9 1253.36  5175.2 1255.51  5206.2 1256.67
#Mann= 8 ,-1 , 0
  4434.3     .07       0    4614    .035       0  4650.1     .07       0
  4735.9    .035       0  4871.2     .12       0  5000.7     .05       0
    5020     .12       0  5081.8     .07       0
Bank Sta=5000.7,5020
XS Rating Curve= 0 ,0
Exp/Cntr=0.3,0.1

Type RM Length L Ch R = 1 ,3733    ,430,430,430
BEGIN DESCRIPTION:
RAWLS CREEK 6.0
END DESCRIPTION:
XS GIS Cut Line= 3
      2116175.02     13895675.02        2115775.       13895125.
      2115574.96     13895074.99
#Sta/Elev= 30
  4315.3 1244.51  4494.6 1240.11  4500.5 1240.03  4573.8 1237.88  4661.3  1236.6
  4741.1 1235.82  4816.5 1234.14  4837.4 1232.72  4902.3 1233.24    4917 1233.89
  4923.1 1235.13  4931.6 1234.49  4937.8 1235.45  4945.9 1234.44  4982.8 1233.62
  4988.1 1231.82  4992.3 1229.21    4998 1229.21  5003.8 1224.19  5004.3 1223.69
  5023.1 1224.19  5026.3  1230.5  5046.9 1237.98  5054.7 1242.62  5067.6 1245.94
  5088.2 1247.46  5129.4 1254.39  5160.3 1256.29  5183.5 1260.51  5201.6 1262.09
#Mann= 8 ,-1 , 0
  4315.3     .12       0  4494.6     .07       0  4500.5    .035       0
  4661.3     .07       0  4741.1    .035       0  4982.8     .12       0
  5003.8     .05       0  5023.1     .12       0
Bank Sta=5003.8,5023.1
XS Rating Curve= 0 ,0
Exp/Cntr=0.3,0.1

Type RM Length L Ch R = 1 ,3303    ,469,469,469
BEGIN DESCRIPTION:
RAWLS CREEK 5.0
END DESCRIPTION:
XS GIS Cut Line= 3
      2117174.97     13895974.97        2115975.       13894775.
      2115774.97     13894724.99
#Sta/Elev= 30
  3302.7 1280.95  3415.8 1274.88  3472.4 1273.83  3528.9 1266.36  3570.1 1263.83
  3642.1 1261.48  3698.6  1256.9    3758 1254.85  3761.2 1254.64  4043.3 1245.12
  4094.6 1244.25  4302.2 1235.28  4330.3  1234.9  4437.4 1233.53  4473.9 1233.41
  4490.6 1232.44  4688.6 1235.11  4801.7 1230.83  4904.4  1232.2  4957.3 1231.35
  4975.9 1224.95  4976.4 1224.45  4995.2 1224.95  4996.2 1227.79    5010 1229.28
  5022.9 1233.96  5051.2 1235.96  5123.4 1245.65  5182.7 1251.69  5205.9  1252.6
#Mann= 12 ,-1 , 0
  3302.7     .07       0  3570.1    .035       0    3758     .07       0
  3761.2     .12       0  4043.3     .07       0  4302.2     .12       0
  4330.3     .07       0  4437.4     .12       0  4473.9    .035       0
  4904.4     .12       0  4975.9     .05       0  4995.2     .12       0
Bank Sta=4975.9,4995.2
XS Rating Curve= 0 ,0
Exp/Cntr=0.3,0.1

Type RM Length L Ch R = 1 ,2834    ,1053,1053,1053
BEGIN DESCRIPTION:
RAWLS CREEK 4.0
END DESCRIPTION:
XS GIS Cut Line= 3
      2117424.98     13895674.97        2116325.       13894475.
      2116174.99     13894324.99
#Sta/Elev= 30
  3367.1 1280.62  3503.3 1273.85  3543.7 1271.61  3579.5 1265.11  3607.9 1262.71
  3671.4 1260.63  3734.9 1255.43  3848.3 1251.89  3897.7 1248.83  3933.4 1244.54
  4011.1 1242.62  4067.9 1239.31  4117.2 1240.94  4190.5 1240.06  4198.6 1239.79
  4265.8  1236.4  4293.6 1233.17  4343.8 1228.47  4517.5 1229.19    4755 1232.29
  4881.9 1230.94  4987.9 1228.47  4998.5 1227.32  4999.4 1223.05  4999.9 1222.55
  5018.8 1223.05  5023.2 1223.97  5051.5 1238.84  5071.8 1241.79  5207.1 1243.98
#Mann= 11 ,-1 , 0
  3367.1     .07       0  3503.3    .035       0  4190.5     .07       0
  4198.6    .035       0  4293.6     .07       0  4517.5    .035       0
    4755     .07       0  4881.9    .035       0  4999.4    .035       0
  5018.8    .035       0  5071.8     .12       0
Bank Sta=4999.4,5018.8
XS Rating Curve= 0 ,0
Exp/Cntr=0.3,0.1

Type RM Length L Ch R = 1 ,1781    ,603,603,603
BEGIN DESCRIPTION:
RAWLS CREEK 3.0
END DESCRIPTION:
XS GIS Cut Line= 3
      2117525.04     13894625.02        2117175.       13894425.
        2115575.       13894025.
#Sta/Elev= 30
  4593.2 1261.31  4644.4 1260.34  4681.8 1256.51  4799.8 1253.48  4864.6 1249.55
  4939.2 1247.62  4973.3  1243.8  4988.4 1235.31  4993.5 1226.76  4998.9 1226.76
  5004.1 1215.82  5004.6 1215.32  5024.7 1215.82  5037.6 1223.91  5047.9 1225.76
  5060.8 1223.28  5096.9 1225.96  5186.7 1228.31  5188.7 1228.28  5289.6 1227.86
  5377.7 1227.89  5625.1 1236.43  6082.7 1245.19  6107.5 1246.41  6193.2 1249.36
  6305.4 1253.13  6367.3 1259.48  6421.4 1261.47  6498.7 1267.48  6645.6 1270.78
#Mann= 10 ,-1 , 0
  4593.2     .07       0  4939.2    .035       0  5004.1    .035       0
  5024.7    .035       0  5186.7     .07       0  5188.7    .035       0
  5289.6     .07       0  6082.7     .12       0  6107.5     .07       0
  6193.2     .12       0
Bank Sta=5004.1,5024.7
XS Rating Curve= 0 ,0
Exp/Cntr=0.3,0.1

Type RM Length L Ch R = 1 ,1178    ,522,522,522
BEGIN DESCRIPTION:
RAWLS CREEK 2.0
END DESCRIPTION:
XS GIS Cut Line= 3
      2117425.03       13893925.      2117021.25      13893924.2
      2116325.02     13894174.99
#Sta/Elev= 30
  4599.5 1241.35  4649.5 1237.67  4749.5 1232.75  4759.5 1231.19  4809.5 1228.32
  4869.5 1223.56  4936.1 1222.19  4959.5 1221.56  4979.5 1219.94  4988.6 1214.24
  4989.1 1213.74  5009.2 1214.24  5009.9 1219.45  5017.8 1224.49  5023.7 1224.82
  5053.8 1226.08    5180 1226.38    5202 1227.08  5233.1 1230.33    5265 1231.88
  5339.4 1232.75  5370.2 1234.04  5424.5 1234.39  5456.3 1235.56    5493  1235.2
  5541.4 1236.62  5573.3 1236.48  5722.1 1240.16    5728 1241.19  5743.3 1241.29
#Mann= 5 ,-1 , 0
  4599.5     .07       0  4936.1     .12       0  4988.6     .05       0
  5009.2     .12       0  5023.7     .07       0
Bank Sta=4988.6,5009.2
XS Rating Curve= 0 ,0
Exp/Cntr=0.3,0.1

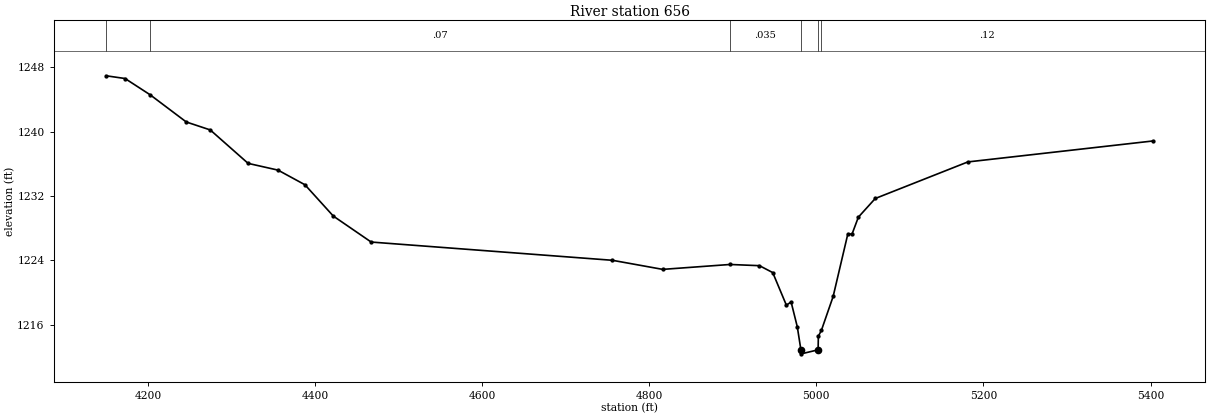
Type RM Length L Ch R = 1 ,656     ,0,0,0
BEGIN DESCRIPTION:
RAWLS CREEK 1.0
END DESCRIPTION:
XS GIS Cut Line= 3
      2117575.01       13893875.        2116825.       13893475.
      2116425.02       13893525.
#Sta/Elev= 30
  4149.9 1246.95  4172.6 1246.61  4202.7 1244.58  4245.9  1241.2  4274.6 1240.21
  4319.9 1236.05  4355.7 1235.21  4387.9 1233.39  4421.9 1229.49  4467.2 1226.26
  4755.9 1223.99  4816.1 1222.86  4896.7 1223.47  4931.9 1223.32  4947.8 1222.46
  4964.1 1218.41  4969.8  1218.8  4977.2 1215.71  4981.5 1212.85    4982 1212.35
  5002.1 1212.85  5002.4 1214.54    5006 1215.26  5020.1 1219.49  5037.7 1227.28
  5042.7 1227.25  5050.3 1229.36  5070.5 1231.68  5181.3 1236.23    5403 1238.84
#Mann= 6 ,-1 , 0
  4149.9     .12       0  4202.7     .07       0  4896.7    .035       0
  4981.5    .035       0  5002.1    .035       0    5006     .12       0
Bank Sta=4981.5,5002.1
XS Rating Curve= 0 ,0
Exp/Cntr=0.3,0.1

Chan Stop Cuts=-1
Use User Specified Reach Order=0
Composite Channel Slope=5