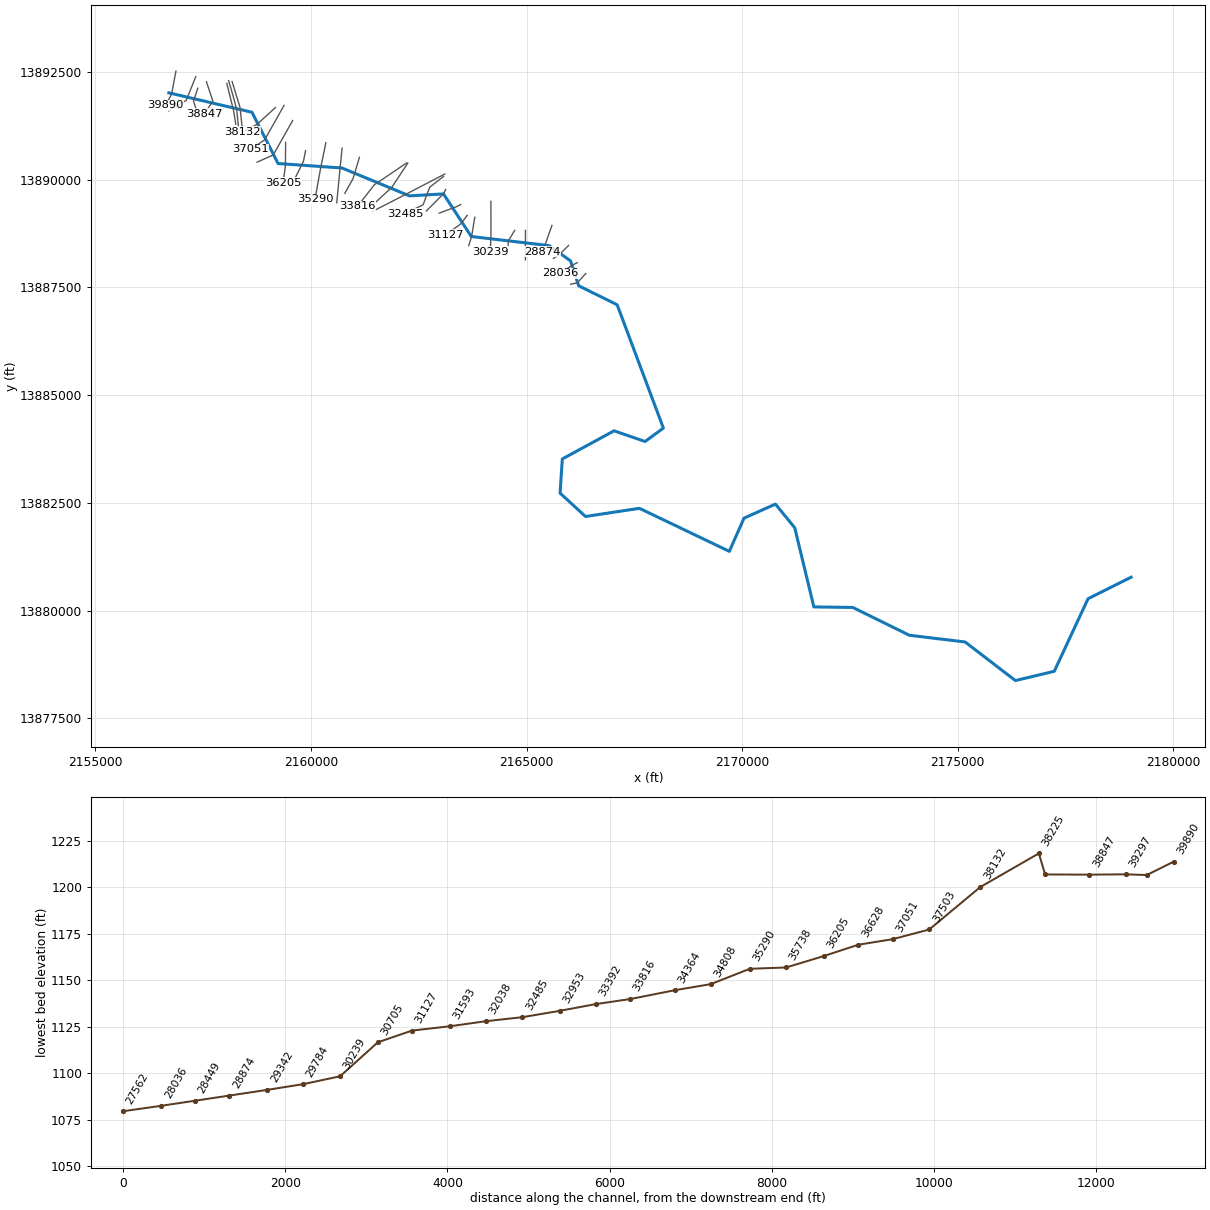
--- Rebecca Creek.prj (project) ---

Proj Title=Rebecca Creek Base Level Engineering
Current Plan=p01
Default Exp/Contr=0.3,0.1
English Units
Geom File=g01
Flow File=f01
Plan File=p01
Y Axis Title=Elevation
X Axis Title(PF)=Main Channel Distance
X Axis Title(XS)=Station
BEGIN DESCRIPTION:
Rebecca Creek
END DESCRIPTION:
DSS Export Rating Curves= 0
DSS Export Rating Curve Sorted= 0
DSS Export Volume Flow Curves= 0
DXF OffsetX= 0
DXF OffsetY= 0
DXF ScaleX= 1
DXF ScaleY= 10

--- Rebecca Creek.p01 (plan) ---

Plan Title=Multiple Run
Short Identifier=Multiple
Geom File=g01
Flow File=f01
Subcritical Flow
K Sum by GR= 0
Std Step Tol= 0.01
Critical Tol= 0.01
Num of Std Step Trials= 20
Max Error Tol= 0.3
Flow Tol Ratio= 0.001
Split Flow NTrial= 30
Split Flow Tol= 0.02
Split Flow Ratio= 0.02
Log Output Level= 0
Friction Slope Method= 1
Unsteady Friction Slope Method= 2
Unsteady Bridges Friction Slope Method= 1
Parabolic Critical Depth
Global Vel Dist=  1 , 1 , 1
Global Log Level= 0
CheckData=True
Encroach Param= -1, 0, 0, 0
BEGIN DESCRIPTION:
Multiple Run
END DESCRIPTION:

--- Rebecca Creek.f01 (steady flow) ---

Flow Title=Multiple
Program Version=4.10
Number of Profiles= 7
Profile Names=10-year,25-year,50-year,1pct_min,100-year,1pct_plu,500-year
River Rch & RM=Rebecca Creek,Reach-1         ,39890
    1074    1823    2536    1710    3413    6809    6114
River Rch & RM=Rebecca Creek,Reach-1         ,37503
    2075    3648    5197    3580    7144   14254   13367
River Rch & RM=Rebecca Creek,Reach-1         ,33816
    3374    6057    8747    6097   12166   24274   23317
River Rch & RM=Rebecca Creek,Reach-1         ,26268
    5024    9157   13362    9400   18755   37422   36611
River Rch & RM=Rebecca Creek,Reach-1         ,19849
    5544   10178   14922   10543   21036   41972   41437
River Rch & RM=Rebecca Creek,Reach-1         ,19195
    5779   10611   15558   10990   21928   43753   43182
River Rch & RM=Rebecca Creek,Reach-1         ,16064
    5853   10714   15674   11045   22038   43971   43181
River Rch & RM=Rebecca Creek,Reach-1         ,7826
    6274   11484   16800   11834   23612   47112   46229
River Rch & RM=Rebecca Creek,Reach-1         ,1171
    6814   12503   18322   12925   25788   51454   50636
Boundary for River Rch & Prof#=Rebecca Creek,Reach-1         , 1
Up Type= 0
Dn Type= 3
Dn Slope=0.002
Boundary for River Rch & Prof#=Rebecca Creek,Reach-1         , 2
Up Type= 0
Dn Type= 3
Dn Slope=0.002
Boundary for River Rch & Prof#=Rebecca Creek,Reach-1         , 3
Up Type= 0
Dn Type= 3
Dn Slope=0.002
Boundary for River Rch & Prof#=Rebecca Creek,Reach-1         , 4
Up Type= 0
Dn Type= 3
Dn Slope=0.002
Boundary for River Rch & Prof#=Rebecca Creek,Reach-1         , 5
Up Type= 0
Dn Type= 3
Dn Slope=0.002
Boundary for River Rch & Prof#=Rebecca Creek,Reach-1         , 6
Up Type= 0
Dn Type= 3
Dn Slope=0.002
Boundary for River Rch & Prof#=Rebecca Creek,Reach-1         , 7
Up Type= 0
Dn Type= 3
Dn Slope=0.002
DSS Import GetInterval= 0
DSS Import GetPeak= 0
DSS Import FillOption= 0

--- Rebecca Creek.g01 (geometry) ---

Geom Title=Existing Conditions
Program Version=4.10

River Reach=Rebecca Creek   ,Reach-1
Reach XY= 30
      2156702.55     13892017.55      2158631.34     13891566.99
      2159236.86     13890376.73      2160719.12     13890273.04
      2162285.43     13889626.05      2163073.54     13889671.46
      2163718.81     13888682.81       2165523.5     13888471.39
      2166019.41     13888119.39      2166211.25      13887538.2
      2167102.08     13887098.51       2168174.3      13884235.7
      2167750.09     13883924.79      2167030.93     13884172.77
      2165830.57     13883519.41      2165778.27     13882726.36
      2166368.33     13882183.96      2167618.95     13882373.33
      2169704.95     13881374.79      2170044.44     13882145.55
      2170773.54     13882471.47      2171221.24     13881923.44
      2171665.19     13880085.51      2172569.07     13880072.77
      2173880.85     13879427.06      2175173.54     13879271.46
      2176340.22     13878375.52      2177242.13     13878591.04
        2178025.       13880275.        2179025.       13880775.

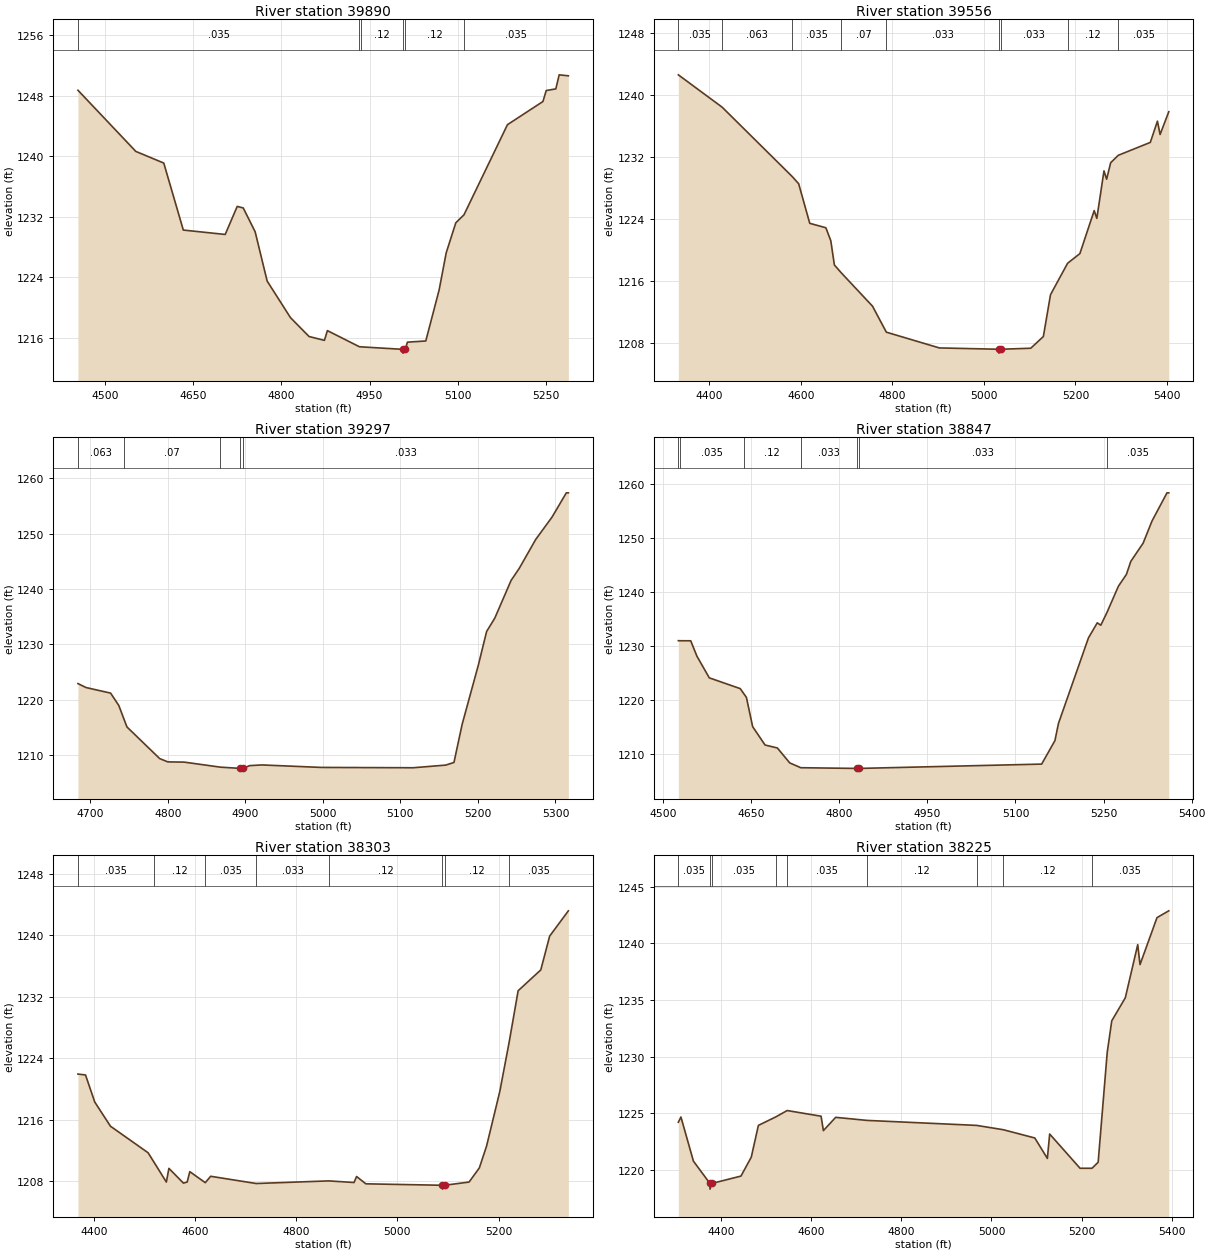
Type RM Length L Ch R = 1 ,39890   ,334,334,334
BEGIN DESCRIPTION:
Rebecca Creek 79.0
END DESCRIPTION:
XS GIS Cut Line= 3
      2156867.32     13892521.04      2156767.68     13891989.65
      2156630.05     13891731.16
#Sta/Elev= 30
  4454.3 1248.74  4552.7 1240.64  4600.2  1239.1  4633.4 1230.23  4704.6 1229.65
    4725 1233.36  4735.2 1233.16  4755.5    1230  4775.9 1223.48  4815.5 1218.64
  4847.1 1216.14  4873.2 1215.63  4878.3 1216.92  4932.5 1214.79  4935.5 1214.77
  5006.6 1214.44  5006.8 1213.94  5010.6 1214.44  5014.3 1215.39  5045.5 1215.55
  5068.2 1222.31  5080.2 1227.22  5096.5 1231.19  5110.4 1232.25  5184.3 1244.18
  5244.6 1247.25  5250.2  1248.7  5266.5 1248.92  5272.2 1250.78  5287.8 1250.65
#Mann= 6 ,-1 , 0
  4454.3    .035       0  4932.5    .033       0  4935.5     .12       0
  5006.6     .05       0  5010.6     .12       0  5110.4    .035       0
Bank Sta=5006.6,5010.6
XS Rating Curve= 0 ,0
Exp/Cntr=0.3,0.1

Type RM Length L Ch R = 1 ,39556   ,259,259,259
BEGIN DESCRIPTION:
Rebecca Creek 78.0
END DESCRIPTION:
XS GIS Cut Line= 3
      2157327.89     13892394.13      2157106.99     13891843.98
      2156695.98     13891599.03
#Sta/Elev= 30
  4332.5 1242.56  4428.2 1238.39  4581.3 1229.45  4595.4 1228.52  4619.6 1223.42
  4654.8 1222.85  4665.6 1221.17  4673.4 1218.05  4688.6 1217.03  4756.7 1212.74
  4786.9 1209.39  4902.7 1207.36  5032.5 1207.19  5032.8 1206.69  5036.5 1207.19
  5102.3 1207.32  5129.9 1208.83  5145.5 1214.22  5182.8 1218.27  5209.7 1219.52
  5240.9 1225.06  5246.7 1224.06  5262.3 1230.18  5268.1 1229.11  5276.9 1231.23
  5293.6 1232.19  5363.5 1233.85  5379.1 1236.59  5384.9 1234.87  5403.8  1237.8
#Mann= 9 ,-1 , 0
  4332.5    .035       0  4428.2    .063       0  4581.3    .035       0
  4688.6     .07       0  4786.9    .033       0  5032.5    .033       0
  5036.5    .033       0  5182.8     .12       0  5293.6    .035       0
Bank Sta=5032.5,5036.5
XS Rating Curve= 0 ,0
Exp/Cntr=0.3,0.1

Type RM Length L Ch R = 1 ,39297   ,450,450,450
BEGIN DESCRIPTION:
Rebecca Creek 77.0
END DESCRIPTION:
XS GIS Cut Line= 3
      2157374.99     13892124.97        2157275.       13891825.
      2157374.99     13891525.03
#Sta/Elev= 30
  4684.2 1222.89  4694.7 1222.17  4726.3 1221.17  4736.9 1218.93  4743.6 1216.45
  4747.4 1215.05  4789.6 1209.33  4800.1 1208.73  4821.2 1208.69  4867.8 1207.78
    4893 1207.56  4893.2 1207.06  4896.7 1207.06    4897 1207.56  4905.5 1208.05
  4921.3 1208.18  4997.8 1207.73  5116.4 1207.67  5158.5 1208.15  5169.1 1208.63
  5179.6  1215.5  5200.7 1226.32  5211.2 1232.31  5221.8 1234.74  5242.8 1241.55
  5253.4 1243.75  5274.5 1248.95  5295.5 1252.98    5314 1257.38  5316.6 1257.38
#Mann= 5 ,-1 , 0
  4684.2    .063       0  4743.6     .07       0  4867.8    .033       0
    4893    .033       0    4897    .033       0
Bank Sta=4893,4897
XS Rating Curve= 0 ,0
Exp/Cntr=0.3,0.1

Type RM Length L Ch R = 1 ,38847   ,544,544,544
BEGIN DESCRIPTION:
Rebecca Creek 76.0
END DESCRIPTION:
XS GIS Cut Line= 3
      2157575.01     13892274.98        2157725.       13891825.
      2157524.99     13891524.98
#Sta/Elev= 30
  4526.1    1231  4529.3 1230.99  4547.2 1230.98  4557.7 1228.15  4578.8 1224.13
  4631.5 1222.14  4637.2 1221.26    4642 1220.52  4652.6 1215.12  4673.7 1211.72
  4694.7 1211.17  4715.8 1208.41  4734.6 1207.52  4829.8 1207.39    4830 1206.89
  4833.8 1207.39  5144.6 1208.19  5167.2 1212.52  5173.2 1215.69  5224.3 1231.52
  5239.3  1234.3  5245.3 1233.86  5255.7 1236.19  5275.3 1241.07  5288.9 1243.25
  5296.4 1245.66  5317.4 1249.03  5332.4  1253.1    5358 1258.33    5361 1258.33
#Mann= 7 ,-1 , 0
  4526.1    .063       0  4529.3    .035       0  4637.2     .12       0
  4734.6    .033       0  4829.8    .033       0  4833.8    .033       0
  5255.7    .035       0
Bank Sta=4829.8,4833.8
XS Rating Curve= 0 ,0
Exp/Cntr=0.3,0.1

Type RM Length L Ch R = 1 ,38303   ,78,78,78
BEGIN DESCRIPTION:
Rebecca Creek 75.0
END DESCRIPTION:
XS GIS Cut Line= 3
      2158047.06     13892237.34      2158206.79     13891598.41
       2158255.4     13891291.12
#Sta/Elev= 30
  4368.4 1221.96  4383.4 1221.84  4401.7 1218.32  4432.7 1215.18  4507.1 1211.73
  4519.6 1210.42  4543.2 1207.92  4548.3  1209.7    4577 1207.78  4584.4 1207.92
  4589.6 1209.27  4620.2 1207.84  4630.8 1208.67  4720.9 1207.73  4864.3 1208.07
  4914.3 1207.86  4919.4 1208.64  4937.7 1207.69  5089.2  1207.5  5089.4    1207
  5093.2  1207.5  5141.8 1207.92  5162.1 1209.76  5176.4  1212.6  5202.6 1219.71
  5221.1 1226.12  5238.8 1232.79  5283.6  1235.5  5301.1 1239.89  5338.1 1243.18
#Mann= 8 ,-1 , 0
  4368.4    .035       0  4519.6     .12       0  4620.2    .035       0
  4720.9    .033       0  4864.3     .12       0  5089.2     .05       0
  5093.2     .12       0  5221.1    .035       0
Bank Sta=5089.2,5093.2
XS Rating Curve= 0 ,0
Exp/Cntr=0.3,0.1

Type RM Length L Ch R = 1 ,38225   ,722,722,722
BEGIN DESCRIPTION:
Rebecca Creek 74.5
END DESCRIPTION:
XS GIS Cut Line= 4
      2158090.16     13892300.55      2158181.31     13891988.06
      2158277.33     13891630.74      2158316.63     13891239.01
#Sta/Elev= 30
  4304.5 1224.22  4310.3 1224.68    4338 1220.79  4374.7 1218.82  4374.9 1218.32
  4378.7 1218.82  4443.6 1219.47  4466.5 1221.14  4482.3 1223.94    4521 1224.69
  4546.2 1225.25  4621.5 1224.75  4626.7 1223.48  4653.9 1224.65  4723.7 1224.38
  4966.9 1223.94  5026.1 1223.56  5096.2 1222.83  5124.1 1221.03  5129.2 1223.18
  5196.7 1220.16  5223.2 1220.16  5236.9 1220.69    5257 1230.36  5267.1 1233.16
  5297.2 1235.19  5324.8 1239.88  5329.9 1238.12  5367.6 1242.26  5393.7 1242.86
#Mann= 9 ,-1 , 0
  4304.5    .035       0  4374.7    .035       0  4378.7    .035       0
    4521     .12       0  4546.2    .035       0  4723.7     .12       0
  4966.9    .035       0  5026.1     .12       0  5223.2    .035       0
Bank Sta=4374.7,4378.7
XS Rating Curve= 0 ,0
Exp/Cntr=0.3,0.1

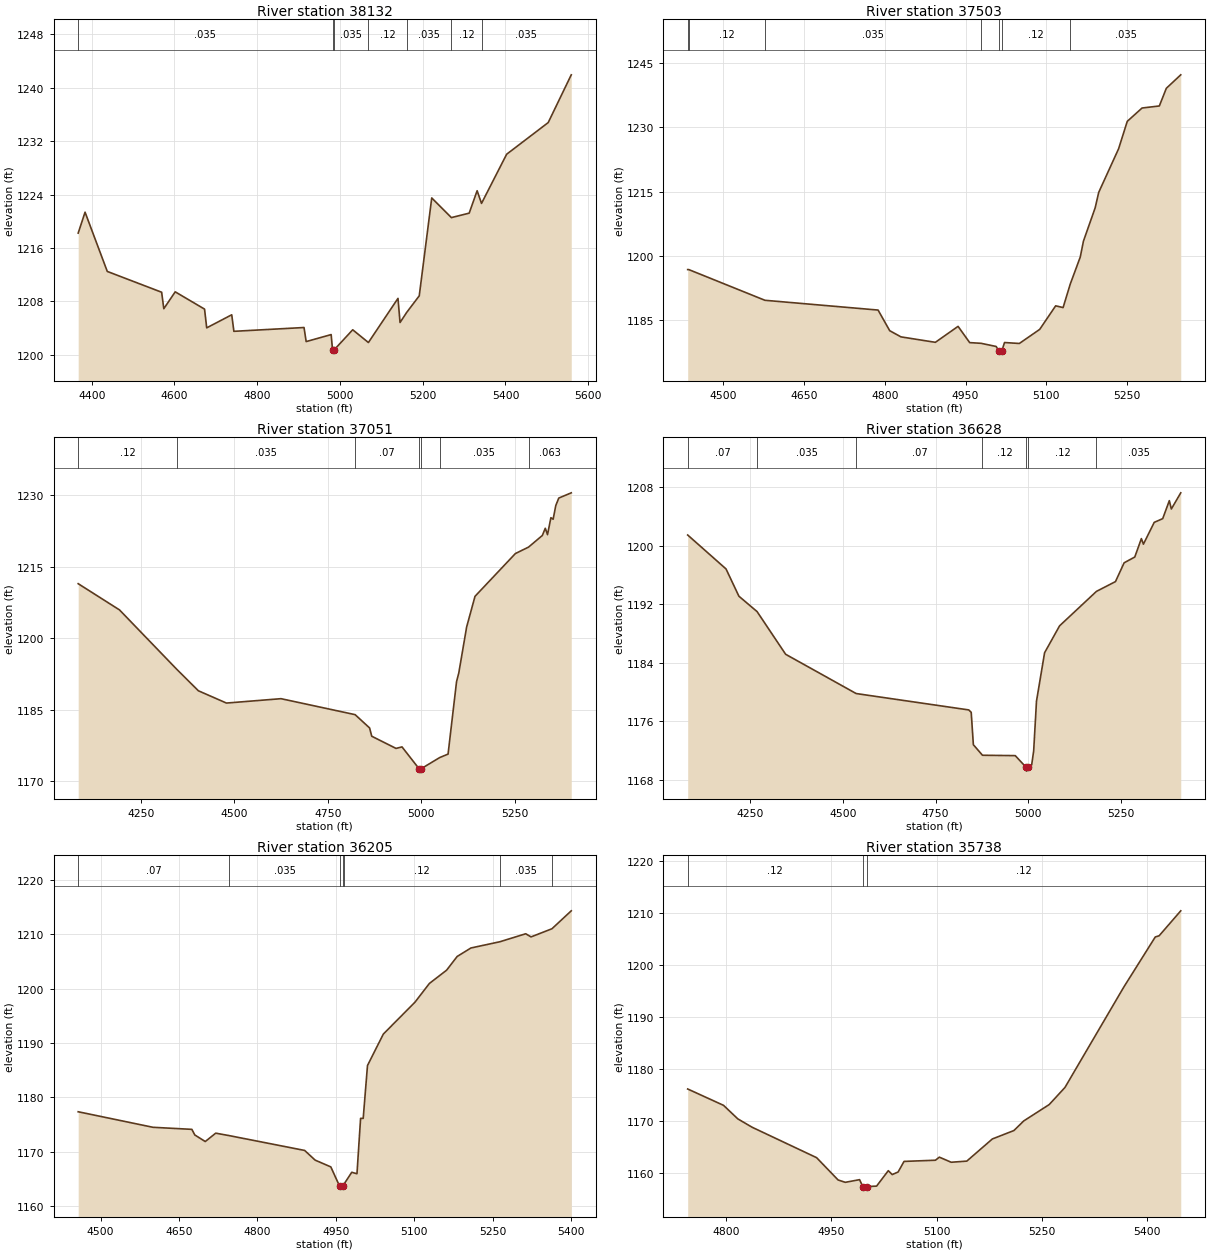
Type RM Length L Ch R = 1 ,38132   ,629,629,629
BEGIN DESCRIPTION:
Rebecca Creek 74.0
END DESCRIPTION:
XS GIS Cut Line= 3
      2158170.62     13892280.85      2158354.95      13891675.6
      2158413.34     13891119.65
#Sta/Elev= 30
  4367.3 1218.22  4383.9 1221.35  4437.6 1212.47    4569 1209.35  4574.2 1206.88
  4601.8 1209.41  4672.7 1206.82  4677.9 1204.01  4738.4 1205.97  4743.6 1203.49
  4913.1 1204.06  4918.3 1201.95  4978.7    1203    4982 1200.72  4982.2 1200.22
    4986 1200.72  5030.8 1203.72  5068.7 1201.81  5140.2 1208.43  5145.2 1204.81
  5161.2 1206.32  5191.6 1208.81  5221.8 1223.49  5269.3 1220.54  5312.3 1221.21
  5331.5 1224.57  5342.1 1222.67  5402.8 1230.04  5503.3 1234.79    5559 1241.95
#Mann= 7 ,-1 , 0
  4367.3    .035       0    4982    .035       0    4986    .035       0
  5068.7     .12       0  5161.2    .035       0  5269.3     .12       0
  5342.1    .035       0
Bank Sta=4982,4986
XS Rating Curve= 0 ,0
Exp/Cntr=0.3,0.1

Type RM Length L Ch R = 1 ,37503   ,452,452,452
BEGIN DESCRIPTION:
Rebecca Creek 73.0
END DESCRIPTION:
XS GIS Cut Line= 3
      2159174.96     13891674.97      2158750.19     13891287.64
      2158451.56      13891122.7
#Sta/Elev= 30
  4433.7 1196.86  4435.7 1196.86  4577.2  1189.7  4787.4 1187.42    4809 1182.61
  4829.9 1181.17  4893.8  1179.9    4936 1183.62  4957.6 1179.83  4978.6 1179.67
  5006.8 1178.93  5011.7 1177.88  5012.2 1177.38  5017.2 1177.88  5022.3 1179.85
  5049.8 1179.63  5087.6 1182.91  5117.3 1188.41  5131.1    1188  5144.4 1193.48
    5163 1199.78  5168.9 1203.49  5190.7 1211.26  5197.3 1214.87  5234.2 1225.02
  5250.3 1231.42  5277.8 1234.53  5309.9 1235.01  5322.9 1239.13  5349.7 1242.27
#Mann= 7 ,-1 , 0
  4433.7    .035       0  4435.7     .12       0  4577.2    .035       0
  4978.6     .12       0  5011.7     .05       0  5017.2     .12       0
  5144.4    .035       0
Bank Sta=5011.7,5017.2
XS Rating Curve= 0 ,0
Exp/Cntr=0.3,0.1

Type RM Length L Ch R = 1 ,37051   ,423,423,423
BEGIN DESCRIPTION:
Rebecca Creek 72.0
END DESCRIPTION:
XS GIS Cut Line= 3
      2159375.01     13891725.02        2158925.       13890925.
      2158590.49     13890702.59
#Sta/Elev= 30
  4082.1 1211.46  4192.7 1205.96  4346.3 1193.48  4403.7 1189.01  4478.9 1186.43
  4624.9 1187.35  4823.3    1184    4862 1181.21  4867.7 1179.48  4932.7 1176.92
  4948.7 1177.24  4994.4 1172.66  4994.8 1172.16  4999.9 1172.66    5050 1175.02
    5072 1175.73  5094.7 1190.92  5100.7 1192.74  5121.7 1202.38  5144.1 1208.81
  5252.2 1217.78  5287.4 1219.13  5324.2 1221.56  5332.2 1223.08  5338.2 1221.74
  5347.2  1225.3  5353.2 1224.97  5360.3 1227.85  5368.3 1229.41  5401.7 1230.51
#Mann= 7 ,-1 , 0
  4082.1     .12       0  4346.3    .035       0  4823.3     .07       0
  4994.4     .05       0  4999.9     .07       0    5050    .035       0
  5287.4    .063       0
Bank Sta=4994.4,4999.9
XS Rating Curve= 0 ,0
Exp/Cntr=0.3,0.1

Type RM Length L Ch R = 1 ,36628   ,423,423,423
BEGIN DESCRIPTION:
Rebecca Creek 71.0
END DESCRIPTION:
XS GIS Cut Line= 3
        2159575.       13891375.        2159125.       13890575.
      2158749.67     13890408.46
#Sta/Elev= 30
  4082.1 1201.47  4185.4 1196.83  4220.1  1193.1    4269    1191    4346 1185.16
    4536 1179.79  4839.3 1177.55    4846 1177.22  4851.8 1172.79  4876.4 1171.35
  4964.6  1171.3  4994.4 1169.68  4994.8 1169.18  4999.9 1169.68  5008.9 1170.03
  5014.3 1171.95  5021.9 1178.75  5043.7 1185.37  5084.1 1189.05  5183.4 1193.76
  5234.7  1195.1    5258 1197.67  5286.7 1198.46  5304.5 1200.98    5310 1200.22
  5339.1  1203.2    5362 1203.71  5379.8 1206.17  5385.2 1205.03  5410.6 1207.24
#Mann= 7 ,-1 , 0
  4082.1     .07       0    4269    .035       0    4536     .07       0
  4876.4     .12       0  4994.4     .05       0  4999.9     .12       0
  5183.4    .035       0
Bank Sta=4994.4,4999.9
XS Rating Curve= 0 ,0
Exp/Cntr=0.3,0.1

Type RM Length L Ch R = 1 ,36205   ,467,467,467
BEGIN DESCRIPTION:
Rebecca Creek 70.0
END DESCRIPTION:
XS GIS Cut Line= 3
      2159412.08      13890867.9      2159406.87     13890326.27
       2159355.6     13889928.72
#Sta/Elev= 30
  4457.3 1177.35  4600.2 1174.49  4674.6 1174.11  4680.2 1173.08  4700.2 1171.87
  4720.2 1173.41  4746.4 1172.95  4890.2 1170.23  4910.2 1168.45  4940.2  1167.2
  4957.2 1163.61  4957.7 1163.11  4963.3 1163.61    4965 1163.97  4980.2 1166.21
  4990.2 1165.94  4997.1 1176.13  5002.1 1176.13  5010.3 1185.86  5040.6 1191.65
  5101.1 1197.52  5128.6 1200.96  5161.6 1203.41  5181.7 1205.93    5208 1207.49
  5263.4 1208.64  5312.8 1210.11  5322.9 1209.53  5362.9 1211.03  5399.8 1214.33
#Mann= 7 ,-1 , 0
  4457.3     .07       0  4746.4    .035       0  4957.2     .05       0
  4963.3    .035       0    4965     .12       0  5263.4    .035       0
  5362.9    .063       0
Bank Sta=4957.2,4963.3
XS Rating Curve= 0 ,0
Exp/Cntr=0.3,0.1

Type RM Length L Ch R = 1 ,35738   ,448,448,448
BEGIN DESCRIPTION:
Rebecca Creek 69.0
END DESCRIPTION:
XS GIS Cut Line= 3
      2159875.01     13890675.03        2159825.       13890425.
        2159625.       13890025.
#Sta/Elev= 30
  4745.5 1176.21  4796.5 1173.07  4816.9 1170.46  4837.3 1168.85  4929.1    1163
  4959.7 1158.71  4969.9 1158.26  4990.3 1158.77  4994.8 1157.45  4995.3 1156.95
  5000.6 1156.95  5001.1 1157.45  5014.5 1157.53  5031.2  1160.5  5036.8 1159.75
  5045.2 1160.25  5053.6 1162.28  5098.3 1162.51  5103.9  1163.1  5120.7 1162.12
    5143 1162.34  5179.4  1166.6  5210.1 1168.22  5224.1 1170.07  5260.4 1173.22
  5282.8 1176.51  5366.6 1195.82  5411.4 1205.45  5416.9 1205.68  5447.7 1210.48
#Mann= 3 ,-1 , 0
  4745.5     .12       0  4994.8     .05       0  5001.1     .12       0
Bank Sta=4994.8,5001.1
XS Rating Curve= 0 ,0
Exp/Cntr=0.3,0.1

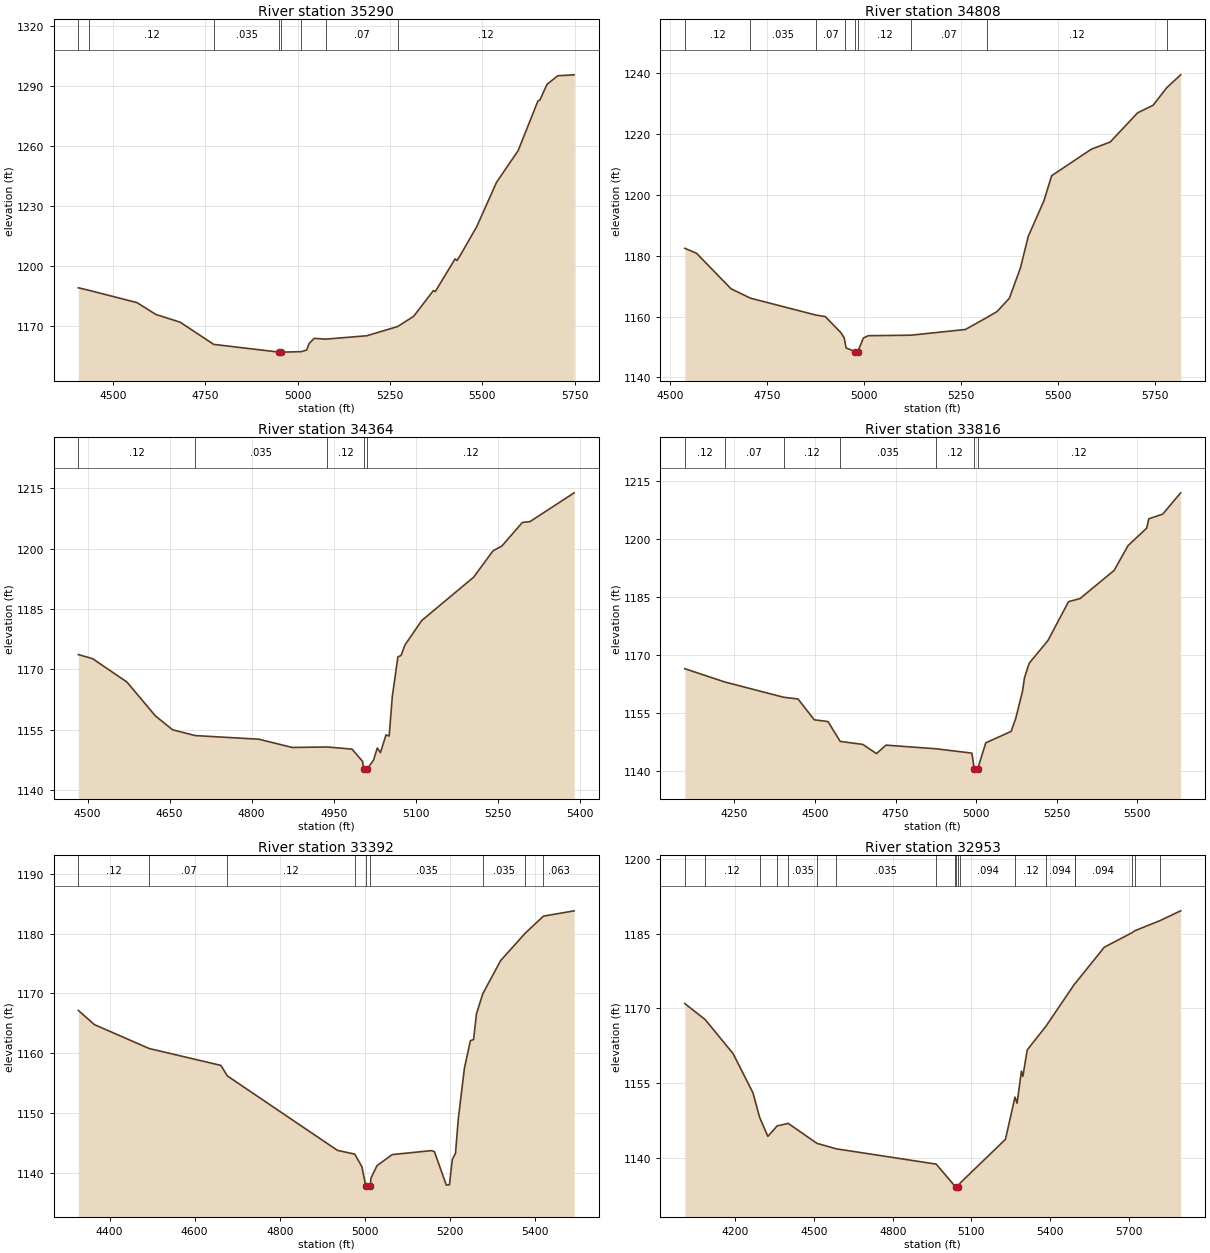
Type RM Length L Ch R = 1 ,35290   ,482,482,482
BEGIN DESCRIPTION:
Rebecca Creek 68.0
END DESCRIPTION:
XS GIS Cut Line= 3
      2160345.37     13890860.45        2160225.       13890275.
      2160092.76     13889542.74
#Sta/Elev= 30
  4406.5 1188.94  4436.2 1187.63  4565.2 1181.52  4616.3 1175.59    4682 1171.72
  4772.9 1160.61    4950 1156.73  4950.5 1156.23  4956.3 1156.73  5009.8 1156.96
  5024.5 1157.78    5031    1161  5044.8 1163.63  5075.4 1163.23  5187.1 1164.92
  5270.6 1169.53  5313.9 1174.66  5367.5 1187.55  5372.5 1187.06  5426.1 1203.42
  5431.2 1202.54  5441.2 1205.53  5484.7 1219.55  5538.2  1241.7  5596.9 1257.64
  5650.4 1282.49  5655.5 1282.89  5674.9 1290.77  5703.9 1295.06  5748.3 1295.52
#Mann= 8 ,-1 , 0
  4406.5     .07       0  4436.2     .12       0  4772.9    .035       0
    4950    .035       0  4956.3    .035       0  5009.8     .12       0
  5075.4     .07       0  5270.6     .12       0
Bank Sta=4950,4956.3
XS Rating Curve= 0 ,0
Exp/Cntr=0.3,0.1

Type RM Length L Ch R = 1 ,34808   ,444,444,444
BEGIN DESCRIPTION:
Rebecca Creek 67.0
END DESCRIPTION:
XS GIS Cut Line= 3
      2160722.63     13890734.76        2160675.       13890275.
      2160597.97     13889464.57
#Sta/Elev= 30
  4538.6 1182.44  4568.8 1180.81  4657.6 1169.13  4707.6 1166.04  4876.1 1160.49
  4900.3 1159.98  4940.5 1154.69  4948.9 1152.99  4951.8 1151.06  4953.9 1149.67
  4977.5 1148.47    4978 1147.97  4983.9 1148.47  4998.3 1152.94  5010.9  1153.7
    5121 1153.87    5261 1155.75  5315.7 1159.65  5342.4 1161.65  5374.1 1166.02
  5402.6 1176.01  5422.7 1186.37  5462.9 1198.02    5483 1206.32  5585.3 1215.04
  5633.7 1217.39    5704 1226.96  5744.2 1229.49  5779.1 1235.24  5814.9 1239.48
#Mann= 9 ,-1 , 0
  4538.6     .12       0  4707.6    .035       0  4876.1     .07       0
  4951.8     .12       0  4977.5     .05       0  4983.9     .12       0
    5121     .07       0  5315.7     .12       0  5779.1    .035       0
Bank Sta=4977.5,4983.9
XS Rating Curve= 0 ,0
Exp/Cntr=0.3,0.1

Type RM Length L Ch R = 1 ,34364   ,548,548,548
BEGIN DESCRIPTION:
Rebecca Creek 66.0
END DESCRIPTION:
XS GIS Cut Line= 3
      2161124.12     13890519.99        2160975.       13890025.
      2160785.54     13889684.42
#Sta/Elev= 30
    4483 1173.69  4509.1 1172.66  4571.8 1166.86    4624 1158.42  4655.3 1154.98
  4696.9 1153.53  4813.2 1152.63    4874 1150.58  4938.6 1150.69  4983.5 1150.16
  5002.8 1147.12  5004.7 1145.19  5005.2 1144.69  5011.2 1145.19  5022.9 1147.46
  5029.7 1150.44  5035.4 1149.29  5045.7 1153.72  5051.4 1153.41  5057.2  1163.3
  5067.4 1173.11  5073.2 1173.46  5080.1 1176.03  5110.9 1182.14  5205.9 1192.93
  5241.3 1199.49  5257.3 1200.65    5295 1206.54  5308.9 1206.75  5389.7 1213.91
#Mann= 5 ,-1 , 0
    4483     .12       0  4696.9    .035       0  4938.6     .12       0
  5004.7     .05       0  5011.2     .12       0
Bank Sta=5004.7,5011.2
XS Rating Curve= 0 ,0
Exp/Cntr=0.3,0.1

Type RM Length L Ch R = 1 ,33816   ,424,424,424
BEGIN DESCRIPTION:
Rebecca Creek 65.0
END DESCRIPTION:
XS GIS Cut Line= 3
      2162217.77      13890389.1      2161468.78     13889882.73
      2161079.29     13889381.97
#Sta/Elev= 30
  4095.9 1166.48  4219.2 1163.06  4402.2 1159.09  4447.3 1158.64  4497.6 1153.25
  4540.2 1152.79  4578.1 1147.66  4648.1 1146.88  4690.7  1144.5  4720.1 1146.69
    4876 1145.74  4986.7 1144.62    4994 1140.46  4994.5 1139.96  5004.5 1140.46
  5029.7 1147.28  5108.4 1150.24  5122.9 1153.64  5143.7 1160.61    5150 1164.16
  5164.5 1167.89  5222.4 1173.74  5286.7 1183.84    5322 1184.62  5427.9 1191.91
  5471.3 1198.34  5529.2 1202.88  5535.5 1205.29    5579  1206.5  5634.4 1212.01
#Mann= 7 ,-1 , 0
  4095.9     .12       0  4219.2     .07       0  4402.2     .12       0
  4578.1    .035       0    4876     .12       0    4994     .05       0
  5004.5     .12       0
Bank Sta=4994,5004.5
XS Rating Curve= 0 ,0
Exp/Cntr=0.3,0.1

Type RM Length L Ch R = 1 ,33392   ,439,439,439
BEGIN DESCRIPTION:
Rebecca Creek 64.0
END DESCRIPTION:
XS GIS Cut Line= 3
      2162246.42     13890386.52        2161875.       13889825.
      2161514.73     13889491.32
#Sta/Elev= 30
  4326.8 1167.14  4364.6 1164.76  4493.4 1160.76  4661.5 1157.94    4677 1156.17
  4935.4 1143.72  4975.8  1143.1  4992.5 1141.02  5001.9 1137.74  5002.4 1137.24
  5012.4 1137.74  5013.9 1139.06  5028.1 1141.17  5063.8 1143.02  5155.7 1143.68
    5163 1143.51  5190.9 1137.92  5198.2 1137.96    5205 1142.21  5212.4 1143.22
  5219.2 1149.09  5233.4 1157.47  5247.5 1162.08  5254.9 1162.27  5261.7 1166.57
  5276.7 1169.95  5318.4 1175.47  5376.2 1180.06  5418.9 1182.91  5491.1  1183.8
#Mann= 9 ,-1 , 0
  4326.8     .12       0  4493.4     .07       0    4677     .12       0
  4975.8    .035       0  5001.9    .035       0  5012.4    .035       0
  5276.7    .035       0  5376.2     .12       0  5418.9    .063       0
Bank Sta=5001.9,5012.4
XS Rating Curve= 0 ,0
Exp/Cntr=0.3,0.1

Type RM Length L Ch R = 1 ,32953   ,468,468,468
BEGIN DESCRIPTION:
Rebecca Creek 63.0
END DESCRIPTION:
XS GIS Cut Line= 3
      2163105.78     13890133.89        2162225.       13889675.
      2161426.12     13889264.11
#Sta/Elev= 30
  4006.6 1170.97  4084.2 1167.76  4190.8 1160.91  4266.8    1153  4291.8 1148.13
  4323.4 1144.26    4359 1146.36  4401.2 1146.87  4510.6 1142.86  4585.1 1141.75
  4965.7 1138.68  5037.6 1134.22  5039.3 1134.15  5039.8 1133.65  5050.1 1134.15
  5057.4  1134.9  5229.8 1143.66  5266.2 1152.15  5274.2 1150.93  5290.7 1157.37
  5296.3 1156.33  5312.9 1161.64  5384.8 1166.44  5493.9 1174.94  5494.7 1174.95
    5607 1182.31  5712.1  1185.2  5723.3 1185.61  5821.2 1187.69  5898.1 1189.62
#Mann= 19 ,-1 , 0
  4006.6    .063       0  4084.2     .12       0  4291.8    .063       0
    4359     .12       0  4401.2    .035       0  4510.6    .063       0
  4585.1    .035       0  4965.7    .094       0  5037.6    .035       0
  5039.3     .05       0  5050.1    .035       0  5057.4    .094       0
  5266.2     .12       0  5384.8    .094       0  5493.9    .063       0
  5494.7    .094       0  5712.1    .063       0  5723.3    .035       0
  5821.2    .063       0
Bank Sta=5039.3,5050.1
XS Rating Curve= 0 ,0
Exp/Cntr=0.3,0.1

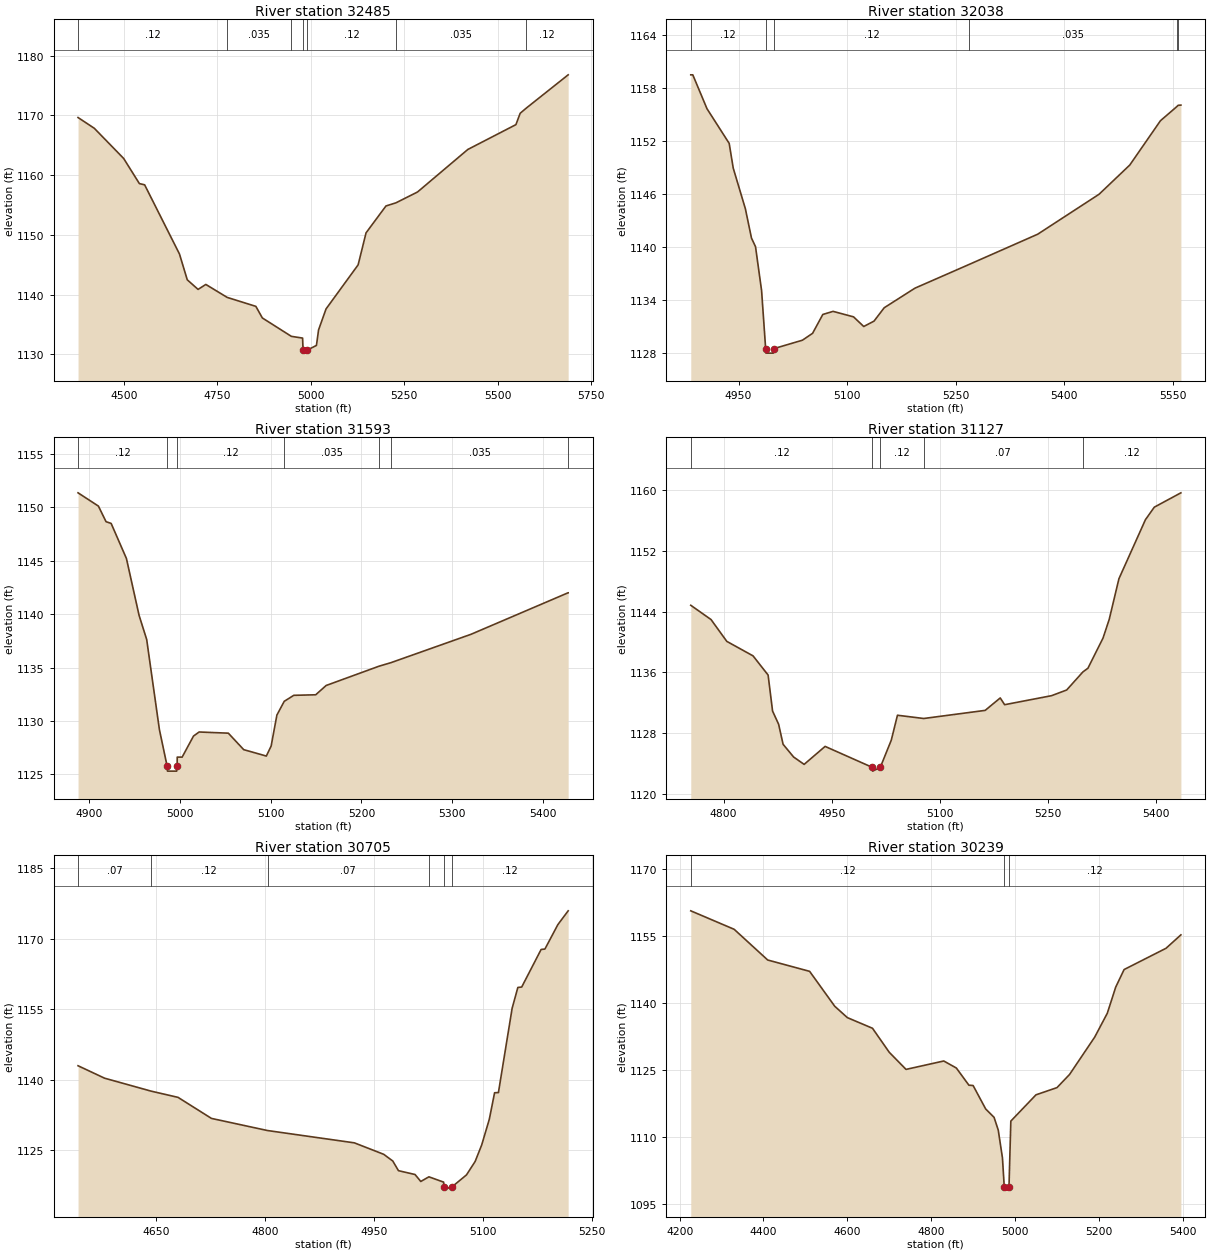
Type RM Length L Ch R = 1 ,32485   ,447,447,447
BEGIN DESCRIPTION:
Rebecca Creek 62.0
END DESCRIPTION:
XS GIS Cut Line= 5
      2163074.54      13890076.6      2162756.83      13889829.2
        2162675.       13889625.      2162603.45     13889420.77
      2162179.95     13889210.03
#Sta/Elev= 30
  4376.9 1169.64  4420.4 1167.84  4499.1 1162.78  4541.1 1158.58  4555.2 1158.37
  4648.4 1146.79  4669.3 1142.47  4698.2 1140.86    4719 1141.69  4776.2 1139.52
  4852.9 1138.02  4870.3 1136.08  4947.9    1133    4978 1132.71  4979.3 1130.69
  4979.8 1130.19  4990.2 1130.69  5015.1 1131.48  5020.8 1134.08  5040.8 1137.59
  5126.7 1144.97  5147.9 1150.33  5201.2 1154.83  5228.1 1155.36  5285.9 1157.18
  5420.3 1164.29  5549.1 1168.45  5560.5 1170.35  5576.5  1171.2    5689 1176.79
#Mann= 7 ,-1 , 0
  4376.9     .12       0  4776.2    .035       0  4947.9     .12       0
  4979.3     .05       0  4990.2     .12       0  5228.1    .035       0
  5576.5     .12       0
Bank Sta=4979.3,4990.2
XS Rating Curve= 0 ,0
Exp/Cntr=0.3,0.1

Type RM Length L Ch R = 1 ,32038   ,445,445,445
BEGIN DESCRIPTION:
Rebecca Creek 61.0
END DESCRIPTION:
XS GIS Cut Line= 3
      2163125.02     13889775.03        2163075.       13889675.
      2162675.02     13889275.02
#Sta/Elev= 30
  4883.9  1159.5  4886.7  1159.5  4906.3 1155.67    4937 1151.75  4942.6 1148.95
  4959.4 1144.35  4967.8 1141.05  4973.4 1140.07  4981.8  1135.1  4987.4 1128.54
  4987.9 1128.04  4997.9 1128.04  4998.4 1128.54  5038.2  1129.5  5052.3 1130.28
  5066.4 1132.41  5080.6 1132.76  5108.9 1132.14    5123 1131.05  5137.2 1131.66
  5151.3 1133.17  5193.7 1135.38  5268.8 1138.07  5363.4 1141.48  5448.3    1146
  5490.7  1149.3  5533.1 1154.31  5555.8 1155.91  5557.5 1156.05  5561.4 1156.08
#Mann= 6 ,-1 , 0
  4883.9     .12       0  4987.4     .05       0  4998.4     .12       0
  5268.8    .035       0  5555.8     .12       0  5557.5    .035       0
Bank Sta=4987.4,4998.4
XS Rating Curve= 0 ,0
Exp/Cntr=0.3,0.1

Type RM Length L Ch R = 1 ,31593   ,466,466,466
BEGIN DESCRIPTION:
Rebecca Creek 60.0
END DESCRIPTION:
XS GIS Cut Line= 3
      2163475.04     13889425.02        2163375.       13889375.
      2162974.96     13889224.98
#Sta/Elev= 30
  4888.3 1151.34  4910.7  1150.1  4919.1 1148.64  4924.7 1148.48  4941.5  1145.2
  4955.4 1139.89  4963.8 1137.62  4977.8 1129.19  4986.2 1125.81  4986.7 1125.31
  4996.8 1125.31  4997.3 1125.81  4997.4 1126.62  5002.8 1126.62  5015.3 1128.59
  5021.5 1128.97  5053.6 1128.86  5070.5 1127.32  5095.4 1126.72  5100.7 1127.66
    5107 1130.55  5115.1 1131.84  5125.6  1132.4  5149.7 1132.45  5161.2 1133.32
  5219.2 1135.12  5232.3 1135.45  5320.6 1138.11  5427.3 1141.99  5427.4 1141.99
#Mann= 7 ,-1 , 0
  4888.3     .12       0  4986.2     .05       0  4997.3     .12       0
  5115.1    .035       0  5219.2     .12       0  5232.3    .035       0
  5427.3     .12       0
Bank Sta=4986.2,4997.3
XS Rating Curve= 0 ,0
Exp/Cntr=0.3,0.1

Type RM Length L Ch R = 1 ,31127   ,422,422,422
BEGIN DESCRIPTION:
Rebecca Creek 59.0
END DESCRIPTION:
XS GIS Cut Line= 3
      2163624.99     13889174.99        2163475.       13888975.
        2163125.       13888725.
#Sta/Elev= 30
  4754.4 1144.86  4782.5 1142.98  4804.4  1140.1  4840.8 1138.19  4861.7 1135.66
  4867.9 1130.91  4876.3 1129.17  4882.5 1126.53  4897.1 1124.85  4911.7 1123.88
  4940.8 1126.25  5006.2 1123.49  5006.7 1122.99  5017.4 1123.49  5032.6 1127.07
  5041.2 1130.36  5077.6 1129.93  5162.9    1131  5183.8 1132.64  5189.9 1131.75
  5255.1 1132.94    5276 1133.69  5298.5 1136.07  5305.5 1136.56  5326.4 1140.53
    5335 1142.99  5348.5 1148.36  5385.3 1156.15  5397.6  1157.8  5434.5 1159.69
#Mann= 5 ,-1 , 0
  4754.4     .12       0  5006.2     .05       0  5017.4     .12       0
  5077.6     .07       0  5298.5     .12       0
Bank Sta=5006.2,5017.4
XS Rating Curve= 0 ,0
Exp/Cntr=0.3,0.1

Type RM Length L Ch R = 1 ,30705   ,466,466,466
BEGIN DESCRIPTION:
Rebecca Creek 58.0
END DESCRIPTION:
XS GIS Cut Line= 3
      2163799.89     13889131.08        2163725.       13888675.
      2163659.56     13888471.45
#Sta/Elev= 30
  4541.8 1142.96  4578.4 1140.31  4642.7 1137.55  4679.7 1136.23  4725.8 1131.75
  4803.1 1129.17  4922.9 1126.55  4963.4 1124.11  4975.9 1122.68  4983.7 1120.63
  5006.6 1119.81  5014.5 1118.33  5025.7 1119.32    5046 1118.19  5046.5  1117.2
    5047  1116.7  5057.7  1117.2  5077.5 1119.72  5089.5 1122.59  5098.5 1126.09
    5109 1131.55  5116.3 1137.21  5121.6 1137.25  5140.5 1155.19  5148.4 1159.62
  5153.7 1159.71  5180.5 1167.71  5185.7 1167.79  5203.6    1173  5217.8 1175.93
#Mann= 6 ,-1 , 0
  4541.8     .07       0  4642.7     .12       0  4803.1     .07       0
  5025.7     .12       0  5046.5     .05       0  5057.7     .12       0
Bank Sta=5046.5,5057.7
XS Rating Curve= 0 ,0
Exp/Cntr=0.3,0.1

Type RM Length L Ch R = 1 ,30239   ,455,455,455
BEGIN DESCRIPTION:
Rebecca Creek 57.0
END DESCRIPTION:
XS GIS Cut Line= 3
      2164173.49     13889498.49        2164175.       13888725.
      2164160.49     13888329.56
#Sta/Elev= 30
  4226.6 1160.57  4330.1 1156.44  4410.1 1149.58  4510.1 1147.05  4570.1 1139.24
  4600.1 1136.71  4660.1 1134.33  4700.1 1128.96  4740.1 1125.14  4830.1 1127.02
  4860.1 1125.45  4890.1 1121.61  4900.1 1121.54  4930.1  1116.3  4950.1 1114.43
  4960.1 1111.57  4970.1 1105.37  4974.4 1098.89  4974.9 1098.39  4985.7 1098.89
  4990.1 1113.59  5050.1 1119.46  5100.2 1121.07  5130.2 1124.01  5190.2 1132.36
  5220.2 1137.68  5240.3 1143.53  5260.3 1147.45  5360.3  1152.2  5395.8  1155.2
#Mann= 3 ,-1 , 0
  4226.6     .12       0  4974.4     .05       0  4985.7     .12       0
Bank Sta=4974.4,4985.7
XS Rating Curve= 0 ,0
Exp/Cntr=0.3,0.1

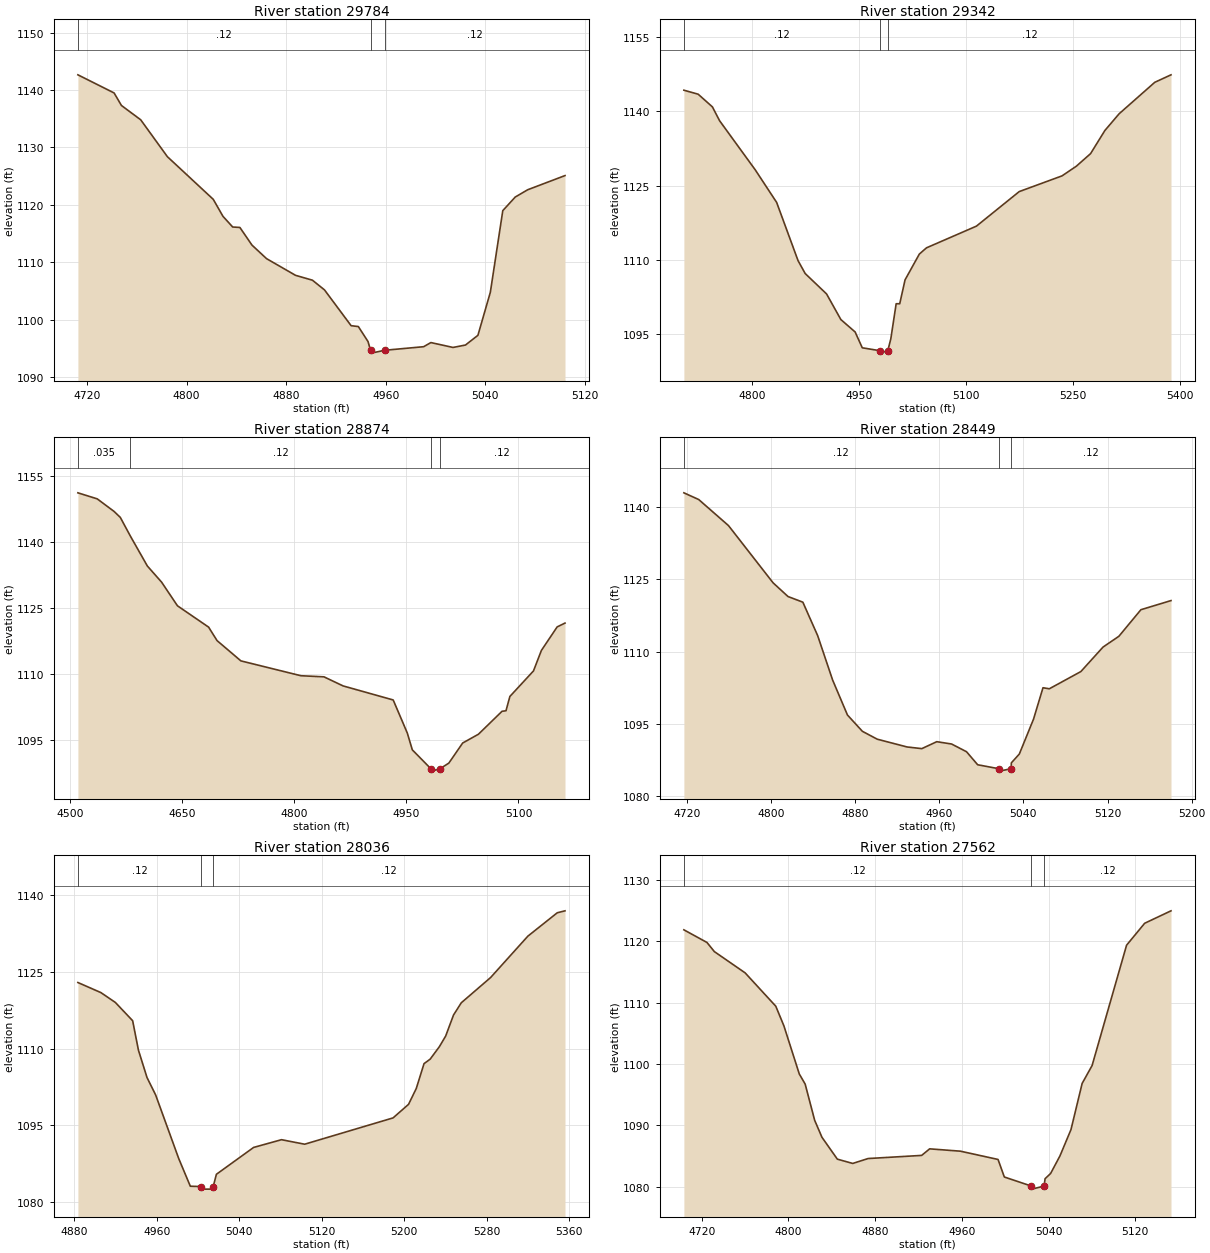
Type RM Length L Ch R = 1 ,29784   ,442,442,442
BEGIN DESCRIPTION:
Rebecca Creek 56.0
END DESCRIPTION:
XS GIS Cut Line= 3
      2164724.98     13888824.97        2164575.       13888575.
        2164575.     13888475.01
#Sta/Elev= 30
  4712.6 1142.66  4741.7  1139.5  4747.6 1137.32  4763.1 1134.82  4784.5  1128.4
  4821.4 1120.96  4829.2    1118    4837 1116.14  4842.8 1116.06  4852.5 1112.99
  4864.2 1110.63  4887.5 1107.72  4901.1 1106.87  4910.8 1105.18  4932.2 1098.94
    4938 1098.79  4945.8 1096.17  4947.8 1094.66  4948.3 1094.16  4959.3 1094.66
  4990.5 1095.28  4996.3    1096  5014.1 1095.15  5024.1 1095.57  5034.1 1097.26
  5044.1 1104.77  5054.1 1118.99  5064.1 1121.36  5074.1 1122.63  5104.1  1125.1
#Mann= 3 ,-1 , 0
  4712.6     .12       0  4947.8     .05       0  4959.3     .12       0
Bank Sta=4947.8,4959.3
XS Rating Curve= 0 ,0
Exp/Cntr=0.3,0.1

Type RM Length L Ch R = 1 ,29342   ,468,468,468
BEGIN DESCRIPTION:
Rebecca Creek 55.0
END DESCRIPTION:
XS GIS Cut Line= 3
        2164975.     13888824.97        2164975.       13888525.
       2164974.4     13888142.27
#Sta/Elev= 30
  4704.6 1144.28  4724.6 1143.47  4744.6  1140.9  4754.6 1138.11  4804.6 1128.17
  4834.6 1121.58  4864.6  1109.8  4874.6 1107.19  4904.6 1103.06  4924.6 1097.88
  4944.6 1095.37  4954.6 1092.17  4978.8 1091.59  4979.3 1091.09  4990.4 1091.59
  4994.6 1093.97  5002.1 1101.08  5007.1 1101.08  5014.6 1105.92  5034.6 1111.13
  5044.6 1112.39  5114.6 1116.78  5174.6 1123.77  5234.6 1126.95  5254.6  1128.9
  5274.6 1131.45  5294.6 1136.12  5314.6 1139.51  5364.6 1145.88  5387.3 1147.39
#Mann= 3 ,-1 , 0
  4704.6     .12       0  4978.8     .05       0  4990.4     .12       0
Bank Sta=4978.8,4990.4
XS Rating Curve= 0 ,0
Exp/Cntr=0.3,0.1

Type RM Length L Ch R = 1 ,28874   ,425,425,425
BEGIN DESCRIPTION:
Rebecca Creek 54.0
END DESCRIPTION:
XS GIS Cut Line= 3
      2165590.01     13888940.62        2165425.       13888475.
        2165375.     13888325.01
#Sta/Elev= 30
  4510.2 1151.18  4536.1 1149.81  4558.6 1146.96    4567  1145.6  4580.2 1141.44
  4603.2 1134.57  4622.3  1130.9  4643.5 1125.54  4685.2  1120.7  4696.5 1117.64
  4728.4 1113.04  4808.8 1109.67  4839.6 1109.42  4865.2 1107.36  4932.3 1104.17
  4951.2 1096.66  4957.9 1092.85    4983 1088.52  4983.5 1088.02  4994.6 1088.52
  5006.8 1089.84  5025.3  1094.4  5046.4 1096.39    5078  1101.6  5083.3 1101.72
  5088.5 1104.96  5120.1 1110.76  5130.7 1115.41  5151.8 1120.75  5162.3 1121.62
#Mann= 4 ,-1 , 0
  4510.2    .035       0  4580.2     .12       0    4983     .05       0
  4994.6     .12       0
Bank Sta=4983,4994.6
XS Rating Curve= 0 ,0
Exp/Cntr=0.3,0.1

Type RM Length L Ch R = 1 ,28449   ,413,413,413
BEGIN DESCRIPTION:
Rebecca Creek 53.0
END DESCRIPTION:
XS GIS Cut Line= 3
      2165974.97     13888474.97        2165775.       13888275.
      2165624.98     13888174.99
#Sta/Elev= 30
  4717.2 1142.91  4731.3 1141.52  4759.6 1136.12    4802 1124.26  4816.2 1121.42
  4830.3 1120.25  4844.4 1113.31  4858.6 1104.12  4872.7 1096.87  4886.9 1093.49
    4901 1091.86  4929.3 1090.25  4943.4  1089.9  4957.6 1091.34  4971.7 1090.86
  4985.9 1089.26  4996.5 1086.56  5016.6 1085.74  5017.1 1085.24  5028.4 1085.74
  5028.5 1086.95  5036.1 1088.78  5049.6 1096.01  5058.6 1102.52  5064.6  1102.3
  5094.6 1105.87  5115.7 1110.95  5130.7 1113.17  5151.7 1118.69  5180.3 1120.58
#Mann= 3 ,-1 , 0
  4717.2     .12       0  5016.6     .05       0  5028.4     .12       0
Bank Sta=5016.6,5028.4
XS Rating Curve= 0 ,0
Exp/Cntr=0.3,0.1

Type RM Length L Ch R = 1 ,28036   ,474,474,474
BEGIN DESCRIPTION:
Rebecca Creek 52.0
END DESCRIPTION:
XS GIS Cut Line= 3
      2166174.97     13888074.98        2166075.       13888025.
      2165775.02     13887825.01
#Sta/Elev= 30
  4883.6 1122.91  4905.9 1120.94  4919.9 1119.02  4936.7 1115.44  4942.3 1109.69
  4950.6 1104.35    4959 1100.93  4981.4 1088.49  4992.6  1083.1    5003 1083.03
  5003.5 1082.53  5014.3 1082.53  5014.8 1083.03  5017.9 1085.43    5054 1090.68
    5081 1092.19  5103.5 1091.31  5189.2 1096.45  5204.2  1099.1  5211.7  1102.2
  5219.2 1107.05  5225.2 1107.94  5234.2  1110.4  5240.2 1112.45  5247.8 1116.55
  5255.3 1118.94  5283.8 1123.89  5319.9 1131.97  5348.4 1136.54  5355.9 1136.92
#Mann= 3 ,-1 , 0
  4883.6     .12       0    5003     .05       0  5014.8     .12       0
Bank Sta=5003,5014.8
XS Rating Curve= 0 ,0
Exp/Cntr=0.3,0.1

Type RM Length L Ch R = 1 ,27562   ,399,399,399
BEGIN DESCRIPTION:
Rebecca Creek 51.0
END DESCRIPTION:
XS GIS Cut Line= 3
      2166375.02     13887825.02      2166180.53      13887609.8
      2166024.95     13887574.99
#Sta/Elev= 30
  4703.5 1121.89  4724.8 1119.83  4731.6 1118.34    4760 1114.87  4788.3 1109.43
  4795.8 1106.22    4810 1098.37  4815.4 1096.73  4824.2 1090.81  4830.9 1088.05
  4845.1 1084.48  4859.3 1083.78  4873.5 1084.58  4922.9 1085.09  4930.3 1086.16
  4958.7 1085.78  4993.4 1084.43  4999.2 1081.57  5024.1 1080.09  5024.6 1079.59
  5035.9 1080.09  5036.8 1081.29  5041.9 1082.14  5050.5    1085  5060.7  1089.3
    5071 1096.83  5080.2 1099.76    5112 1119.38  5128.7 1122.96    5153 1124.99
#Mann= 3 ,-1 , 0
  4703.5     .12       0  5024.1     .05       0  5035.9     .12       0
Bank Sta=5024.1,5035.9
XS Rating Curve= 0 ,0
Exp/Cntr=0.3,0.1