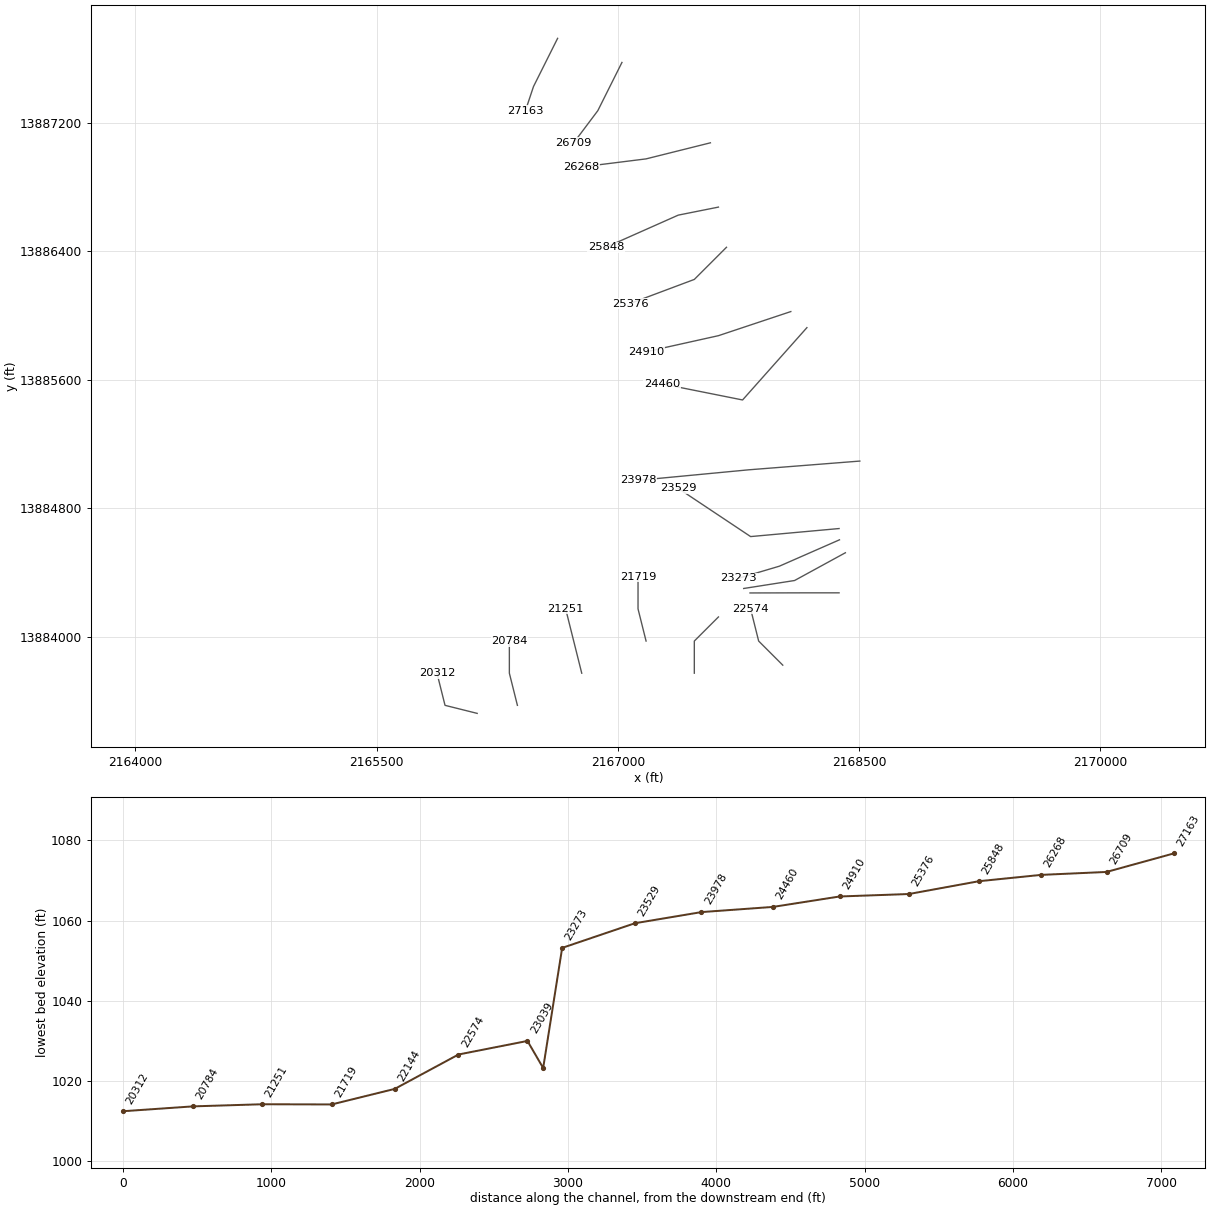
HEC-RAS study Rebecca Creek.prj: Rebecca Creek Base Level Engineering

--- Rebecca Creek.g01 (geometry) --- (continued)

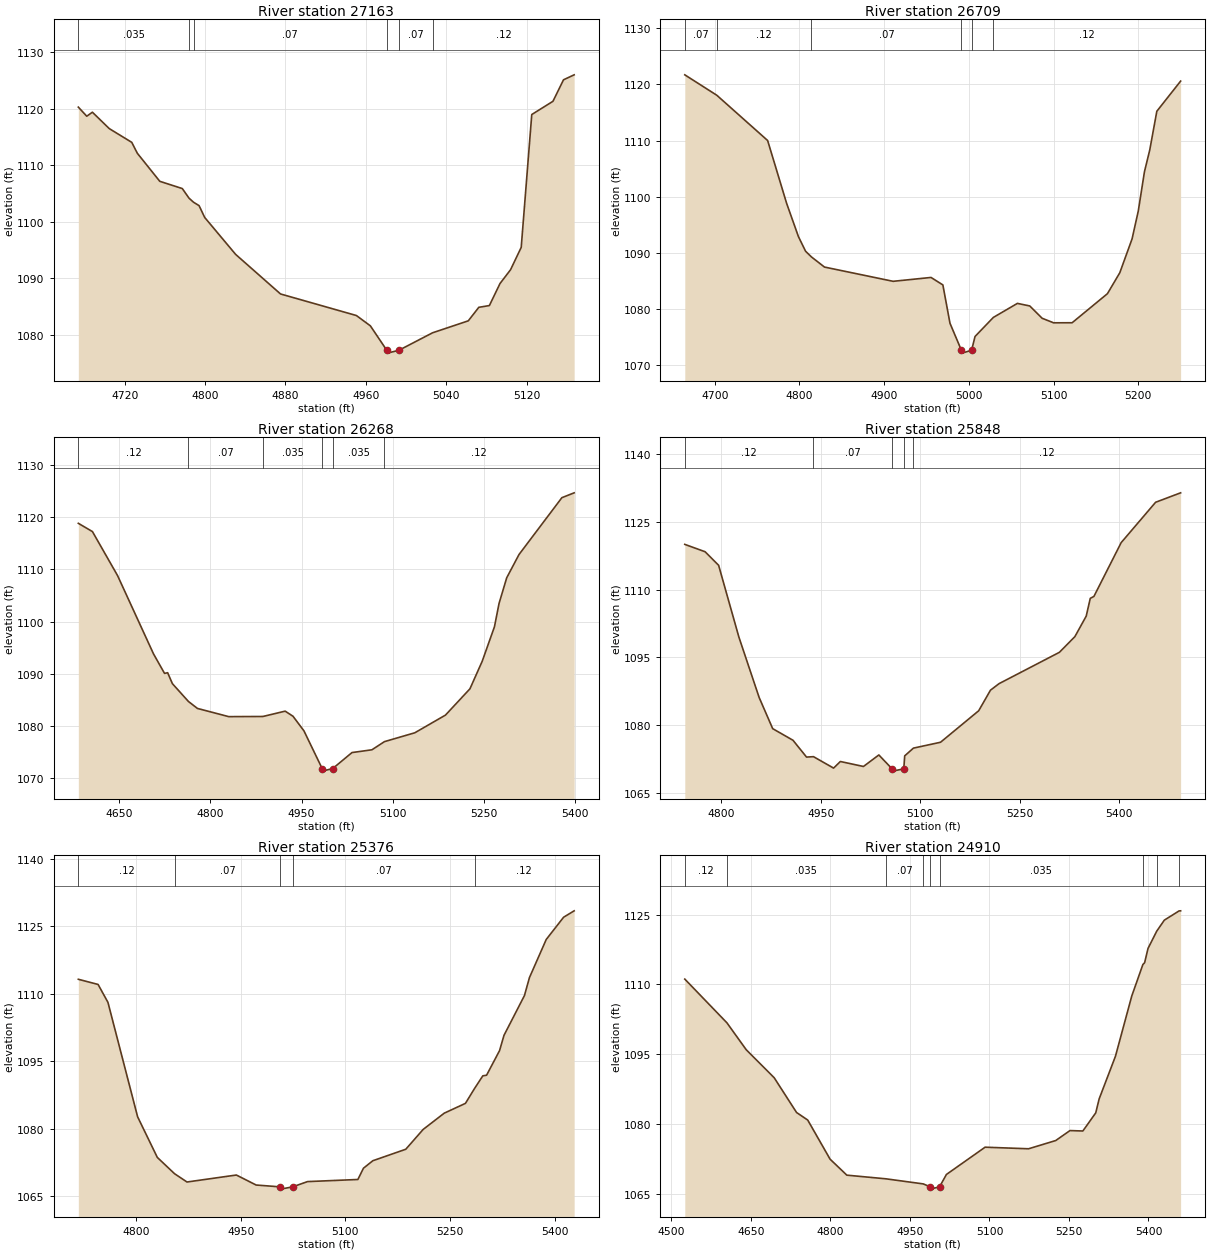
Type RM Length L Ch R = 1 ,27163   ,454,454,454
BEGIN DESCRIPTION:
Rebecca Creek 50.0
END DESCRIPTION:
XS GIS Cut Line= 3
      2166625.02     13887725.04        2166475.       13887425.
      2166424.99     13887274.97
#Sta/Elev= 30
  4673.8 1120.25  4682.2 1118.64  4687.8 1119.35  4704.6 1116.45    4727 1114.02
  4732.5  1112.1  4754.9 1107.13  4777.3 1105.85    4784 1104.15  4788.5 1103.43
    4794 1102.83  4799.6 1100.74  4830.4 1094.21  4875.1 1087.21  4950.6  1083.4
  4964.5 1081.58  4980.9 1077.25  4981.4 1076.75  4992.9 1077.25  5026.5 1080.35
    5062 1082.46  5072.5 1084.85    5083 1085.16  5093.6 1089.06  5104.1  1091.5
  5114.7 1095.45  5125.2 1118.94  5146.3 1121.28  5156.8 1125.08  5167.4 1125.96
#Mann= 6 ,-1 , 0
  4673.8    .035       0    4784     .12       0  4788.5     .07       0
  4980.9     .05       0  4992.9     .07       0  5026.5     .12       0
Bank Sta=4980.9,4992.9
XS Rating Curve= 0 ,0
Exp/Cntr=0.3,0.1

Type RM Length L Ch R = 1 ,26709   ,441,441,441
BEGIN DESCRIPTION:
Rebecca Creek 49.0
END DESCRIPTION:
XS GIS Cut Line= 3
      2167025.01     13887575.02        2166875.       13887275.
      2166725.02     13887075.03
#Sta/Elev= 30
  4664.6  1121.7  4702.4 1118.06  4762.4    1110  4784.8 1098.82  4798.8 1092.87
  4807.2 1090.28  4814.1 1089.27  4829.5 1087.46  4910.6 1084.92  4955.3 1085.61
  4969.3 1084.28  4977.7 1077.45  4991.2 1072.63  4991.7 1072.13  5003.2 1072.63
  5007.3  1075.1  5028.9 1078.49  5057.3 1080.99  5071.9 1080.53  5086.5 1078.34
    5100 1077.53  5121.9 1077.54  5163.6 1082.72  5178.2 1086.45  5192.7 1092.49
    5200 1097.43  5207.3 1104.44  5213.6 1108.34  5221.9 1115.21    5250 1120.58
#Mann= 6 ,-1 , 0
  4664.6     .07       0  4702.4     .12       0  4814.1     .07       0
  4991.2     .05       0  5003.2     .07       0  5028.9     .12       0
Bank Sta=4991.2,5003.2
XS Rating Curve= 0 ,0
Exp/Cntr=0.3,0.1

Type RM Length L Ch R = 1 ,26268   ,420,420,420
BEGIN DESCRIPTION:
Rebecca Creek 48.0
END DESCRIPTION:
XS GIS Cut Line= 3
      2167575.04     13887075.01        2167175.       13886975.
      2166774.96       13886925.
#Sta/Elev= 30
  4582.9 1118.79  4606.1 1117.21  4647.4  1108.8  4706.6 1093.81  4724.7 1090.09
  4729.8 1090.22  4737.6 1088.13    4764 1084.72  4778.8 1083.39  4830.3 1081.82
  4886.5 1081.85  4923.1 1082.87    4936 1081.89    4954  1079.1  4983.9  1071.9
  4984.4  1071.4  5001.4  1071.9    5033 1074.95  5065.8 1075.48  5086.4 1077.04
  5136.3 1078.73  5186.7 1082.11    5227 1087.14  5247.2 1092.42  5267.3    1099
  5274.9 1103.48  5287.5 1108.38  5307.7 1112.82  5378.2 1123.69  5398.4 1124.62
#Mann= 6 ,-1 , 0
  4582.9     .12       0    4764     .07       0  4886.5    .035       0
  4983.9     .05       0  5001.4    .035       0  5086.4     .12       0
Bank Sta=4983.9,5001.4
XS Rating Curve= 0 ,0
Exp/Cntr=0.3,0.1

Type RM Length L Ch R = 1 ,25848   ,472,472,472
BEGIN DESCRIPTION:
Rebecca Creek 47.0
END DESCRIPTION:
XS GIS Cut Line= 3
      2167624.96     13886674.99        2167375.       13886625.
      2166924.96     13886424.98
#Sta/Elev= 30
  4745.1 1120.01  4775.7 1118.38  4796.1 1115.38  4826.6 1099.51  4857.2 1086.11
  4877.6 1079.22  4908.2 1076.65  4928.6 1072.93  4939.1 1073.02  4969.4 1070.49
  4979.6 1071.95  5014.4 1070.85  5037.6  1073.4  5057.6 1070.32  5058.1 1069.82
  5075.2 1070.32  5076.6  1073.2  5089.7 1074.91  5130.6 1076.21  5188.1 1083.18
  5205.9 1087.74  5218.9 1089.19  5309.8 1096.12  5333.1 1099.59  5350.2 1104.13
  5356.3 1108.06  5361.8 1108.49  5402.9  1120.4  5454.8 1129.33  5492.5 1131.42
#Mann= 5 ,-1 , 0
  4745.1     .12       0  4939.1     .07       0  5057.6     .05       0
  5075.2     .07       0  5089.7     .12       0
Bank Sta=5057.6,5075.2
XS Rating Curve= 0 ,0
Exp/Cntr=0.3,0.1

Type RM Length L Ch R = 1 ,25376   ,466,466,466
BEGIN DESCRIPTION:
Rebecca Creek 46.0
END DESCRIPTION:
XS GIS Cut Line= 3
        2167675.       13886425.        2167475.       13886225.
      2167075.04     13886075.01
#Sta/Elev= 30
  4717.6  1113.2  4745.9 1112.05    4760 1108.08  4802.5 1082.68  4830.7 1073.67
  4855.4 1070.05  4873.2 1068.21  4943.9 1069.76  4972.2 1067.54  5006.8 1067.13
  5007.3 1066.63  5024.4 1067.13  5045.8  1068.3  5117.9 1068.77  5125.9 1071.27
  5139.3 1072.93  5186.5 1075.48  5211.4 1079.88  5241.6 1083.49  5271.9 1085.66
    5285 1088.97  5296.8 1091.77  5302.2 1091.91  5320.8 1097.38  5327.1 1100.75
  5356.4 1109.58  5363.6 1113.58  5387.6 1122.03  5412.5 1126.97  5427.6 1128.39
#Mann= 5 ,-1 , 0
  4717.6     .12       0  4855.4     .07       0  5006.8     .05       0
  5024.4     .07       0    5285     .12       0
Bank Sta=5006.8,5024.4
XS Rating Curve= 0 ,0
Exp/Cntr=0.3,0.1

Type RM Length L Ch R = 1 ,24910   ,450,450,450
BEGIN DESCRIPTION:
Rebecca Creek 45.0
END DESCRIPTION:
XS GIS Cut Line= 3
      2168074.99       13886025.        2167625.       13885875.
      2167175.01       13885775.
#Sta/Elev= 30
  4525.3 1111.15  4604.8 1101.75  4641.2 1095.97  4693.9 1089.96  4736.1 1082.49
  4757.2 1080.86  4799.4 1072.45    4831 1069.02  4904.3 1068.24  4975.2 1067.14
  4988.1 1066.52  4988.6 1066.02  5005.9 1066.52  5018.8 1069.17  5091.8 1075.03
  5173.8 1074.69    5225 1076.46  5251.9  1078.6  5276.2 1078.51  5300.5 1082.41
  5306.9  1085.4  5337.7 1094.58  5368.4  1107.5  5389.4 1114.28  5392.7 1114.67
  5399.1 1117.74  5415.6 1121.46  5429.9 1123.82  5457.7  1125.8  5460.6 1125.82
#Mann= 9 ,-1 , 0
  4525.3     .12       0  4604.8    .035       0  4904.3     .07       0
  4975.2    .035       0  4988.1    .035       0  5005.9    .035       0
  5389.4     .07       0  5415.6     .12       0  5457.7    .035       0
Bank Sta=4988.1,5005.9
XS Rating Curve= 0 ,0
Exp/Cntr=0.3,0.1

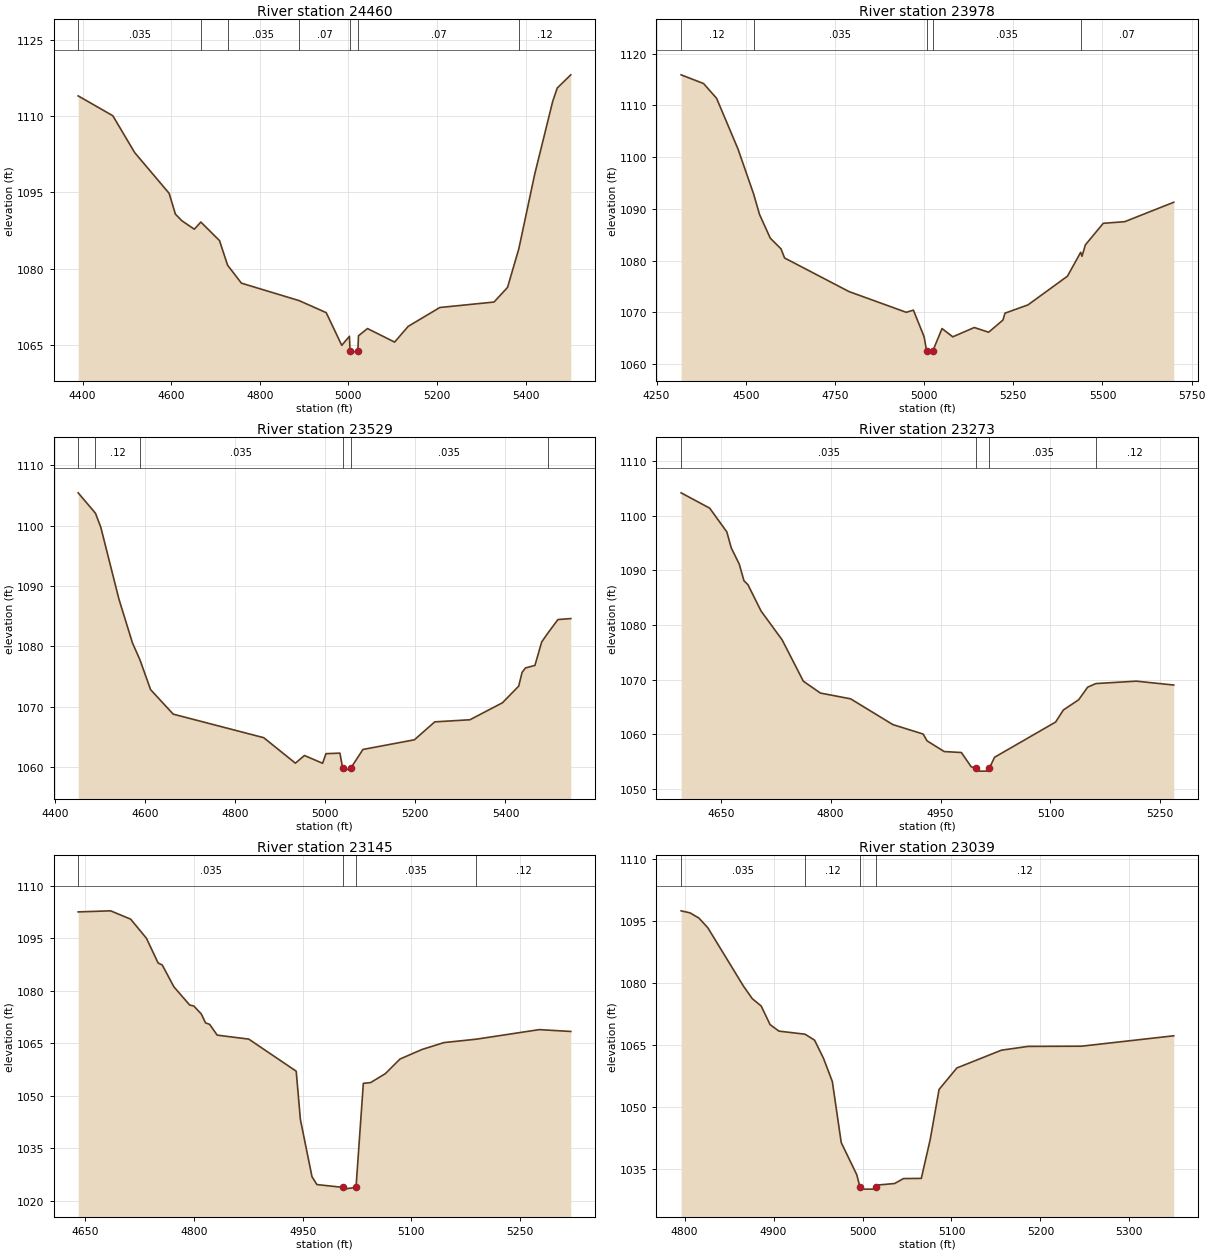
Type RM Length L Ch R = 1 ,24460   ,482,482,482
BEGIN DESCRIPTION:
Rebecca Creek 44.0
END DESCRIPTION:
XS GIS Cut Line= 3
      2168175.02     13885925.03        2167775.       13885475.
      2167275.02       13885575.
#Sta/Elev= 30
  4390.2 1113.99  4468.4 1110.09  4517.8 1102.84  4595.5 1094.84  4609.7 1090.75
    4624 1089.46  4652.4 1087.78  4667.1 1089.19  4709.3 1085.54  4727.4 1080.72
  4758.6 1077.18    4889 1073.74  4950.1 1071.38  4985.2 1064.95  5002.5 1066.73
  5003.8 1063.92  5004.3 1063.42  5021.6 1063.92  5022.9 1066.83  5043.3 1068.25
  5104.5 1065.59  5135.1 1068.68  5206.5 1072.39  5328.9 1073.46  5359.4 1076.34
  5384.9 1083.94  5420.6 1098.55  5461.4 1112.93  5471.6 1115.54  5502.2 1118.13
#Mann= 7 ,-1 , 0
  4390.2    .035       0  4667.1     .07       0  4727.4    .035       0
    4889     .07       0  5003.8     .05       0  5021.6     .07       0
  5384.9     .12       0
Bank Sta=5003.8,5021.6
XS Rating Curve= 0 ,0
Exp/Cntr=0.3,0.1

Type RM Length L Ch R = 1 ,23978   ,449,449,449
BEGIN DESCRIPTION:
Rebecca Creek 43.0
END DESCRIPTION:
XS GIS Cut Line= 3
      2168504.18     13885094.82      2167812.47     13885040.36
      2167128.32      13884975.2
#Sta/Elev= 30
  4318.7 1115.92  4381.6 1114.24  4418.2 1111.38  4478.4 1101.54  4521.7 1092.94
  4538.6 1088.92  4568.7 1084.35  4598.7 1082.29  4608.8 1080.52  4789.3 1074.03
  4949.8 1070.02  4969.9 1070.44    5000 1065.29  5006.7 1062.63  5007.2 1062.13
  5024.7 1062.63  5050.2 1066.88  5080.3 1065.28  5140.6 1067.08  5180.8 1066.17
    5221 1068.52  5226.6 1069.85  5291.3 1071.46  5401.8    1077  5438.9 1081.62
  5442.6 1080.85    5452 1083.05  5502.2 1087.22  5562.5 1087.54  5699.8 1091.29
#Mann= 5 ,-1 , 0
  4318.7     .12       0  4521.7    .035       0  5006.7    .035       0
  5024.7    .035       0  5438.9     .07       0
Bank Sta=5006.7,5024.7
XS Rating Curve= 0 ,0
Exp/Cntr=0.3,0.1

Type RM Length L Ch R = 1 ,23529   ,490,490,490
BEGIN DESCRIPTION:
Rebecca Creek 42.0
END DESCRIPTION:
XS GIS Cut Line= 3
      2168375.03       13884675.        2167825.       13884625.
      2167375.03     13884924.98
#Sta/Elev= 30
  4451.8 1105.45  4490.2 1102.07    4502 1099.75  4542.2 1087.86  4572.3 1080.58
  4588.8  1077.8  4612.5 1072.85  4662.7 1068.79  4863.5 1064.89  4933.8 1060.67
  4953.9 1061.94  4994.1 1060.65  5001.6 1062.24  5032.6 1062.33  5038.7 1059.85
  5039.2 1059.35  5056.7 1059.85  5083.7 1062.94  5197.9 1064.54    5243 1067.51
  5321.1 1067.86  5393.2 1070.67  5429.3 1073.43  5436.8 1075.71  5444.3 1076.44
  5465.3 1076.86  5480.3 1080.75  5493.2 1082.13  5516.4 1084.46  5544.9 1084.62
#Mann= 6 ,-1 , 0
  4451.8    .035       0  4490.2     .12       0  4588.8    .035       0
  5038.7    .035       0  5056.7    .035       0  5493.2     .07       0
Bank Sta=5038.7,5056.7
XS Rating Curve= 0 ,0
Exp/Cntr=0.3,0.1

Type RM Length L Ch R = 1 ,23273   ,128,128,128
BEGIN DESCRIPTION:
Rebecca Creek 41.4
END DESCRIPTION:
XS GIS Cut Line= 3
      2168377.59     13884604.88      2168003.77     13884440.78
      2167750.54     13884365.62
#Sta/Elev= 30
  4595.9 1104.22  4634.9 1101.41  4658.3 1097.06  4664.3 1094.14  4675.2 1091.17
  4681.7 1088.11  4687.1 1087.38    4705 1082.56  4733.8 1077.27  4762.7  1069.7
    4786 1067.52  4827.3 1066.46  4884.9 1061.74  4926.2 1060.01  4931.6 1058.76
    4955  1056.8  4978.4 1056.62  4991.9    1054  4998.5 1053.71    4999 1053.21
    5016 1053.21  5016.5 1053.71  5023.7 1055.75  5107.1 1062.21  5117.6 1064.41
  5138.5 1066.29  5150.8  1068.6    5162 1069.26  5217.2  1069.7  5268.3 1068.99
#Mann= 4 ,-1 , 0
  4595.9    .035       0  4998.5    .035       0  5016.5    .035       0
    5162     .12       0
Bank Sta=4998.5,5016.5
XS Rating Curve= 0 ,0
Exp/Cntr=0.3,0.1

Type RM Length L Ch R = 1 ,23145   ,106,106,106
BEGIN DESCRIPTION:
Rebecca Creek 41.2
END DESCRIPTION:
XS GIS Cut Line= 3
      2168414.27     13884524.38      2168098.39     13884351.69
      2167781.97     13884302.03
#Sta/Elev= 30
    4640 1102.46  4684.8 1102.77  4712.5 1100.39  4734.3 1094.93  4750.4 1087.87
  4756.1  1087.3  4772.2 1081.07    4794 1075.87  4799.7 1075.59  4810.1 1073.29
  4815.9 1070.77  4821.6 1070.34    4832 1067.27  4875.6 1066.13  4941.1 1056.97
  4946.9 1043.16  4962.9 1026.84  4969.7 1024.59  5005.7 1023.79  5006.2 1023.29
  5023.7 1023.79  5033.8  1053.5  5043.9 1053.72  5064.2 1056.27  5084.4 1060.44
  5114.8 1063.17  5145.1 1065.14  5189.7 1066.11  5276.7 1068.84  5320.3 1068.32
#Mann= 4 ,-1 , 0
    4640    .035       0  5005.7    .035       0  5023.7    .035       0
  5189.7     .12       0
Bank Sta=5005.7,5023.7
XS Rating Curve= 0 ,0
Exp/Cntr=0.3,0.1

Type RM Length L Ch R = 1 ,23039   ,465,465,465
BEGIN DESCRIPTION:
Rebecca Creek 41.0
END DESCRIPTION:
XS GIS Cut Line= 3
      2168374.96       13884275.        2168175.       13884275.
      2167821.16      13884274.3
#Sta/Elev= 30
  4796.1 1097.44  4806.1 1096.95  4816.1 1095.69  4826.1 1093.35  4866.1 1079.23
  4876.1 1076.16  4886.1 1074.39  4896.1 1069.88  4906.1  1068.3  4935.4 1067.56
  4946.1 1066.12  4956.1 1061.75  4966.1 1056.09  4976.1  1041.3  4993.6  1033.5
  4997.1 1030.53  4997.6 1030.03  5014.6 1030.03  5015.1 1030.53  5016.1    1031
  5036.1 1031.39  5046.1 1032.59  5066.1 1032.63  5076.1 1042.03  5086.1 1054.18
  5106.1 1059.38  5156.1 1063.68  5186.1  1064.6  5246.1 1064.65  5349.9 1067.17
#Mann= 4 ,-1 , 0
  4796.1    .035       0  4935.4     .12       0  4997.1     .05       0
  5015.1     .12       0
Bank Sta=4997.1,5015.1
XS Rating Curve= 0 ,0
Exp/Cntr=0.3,0.1

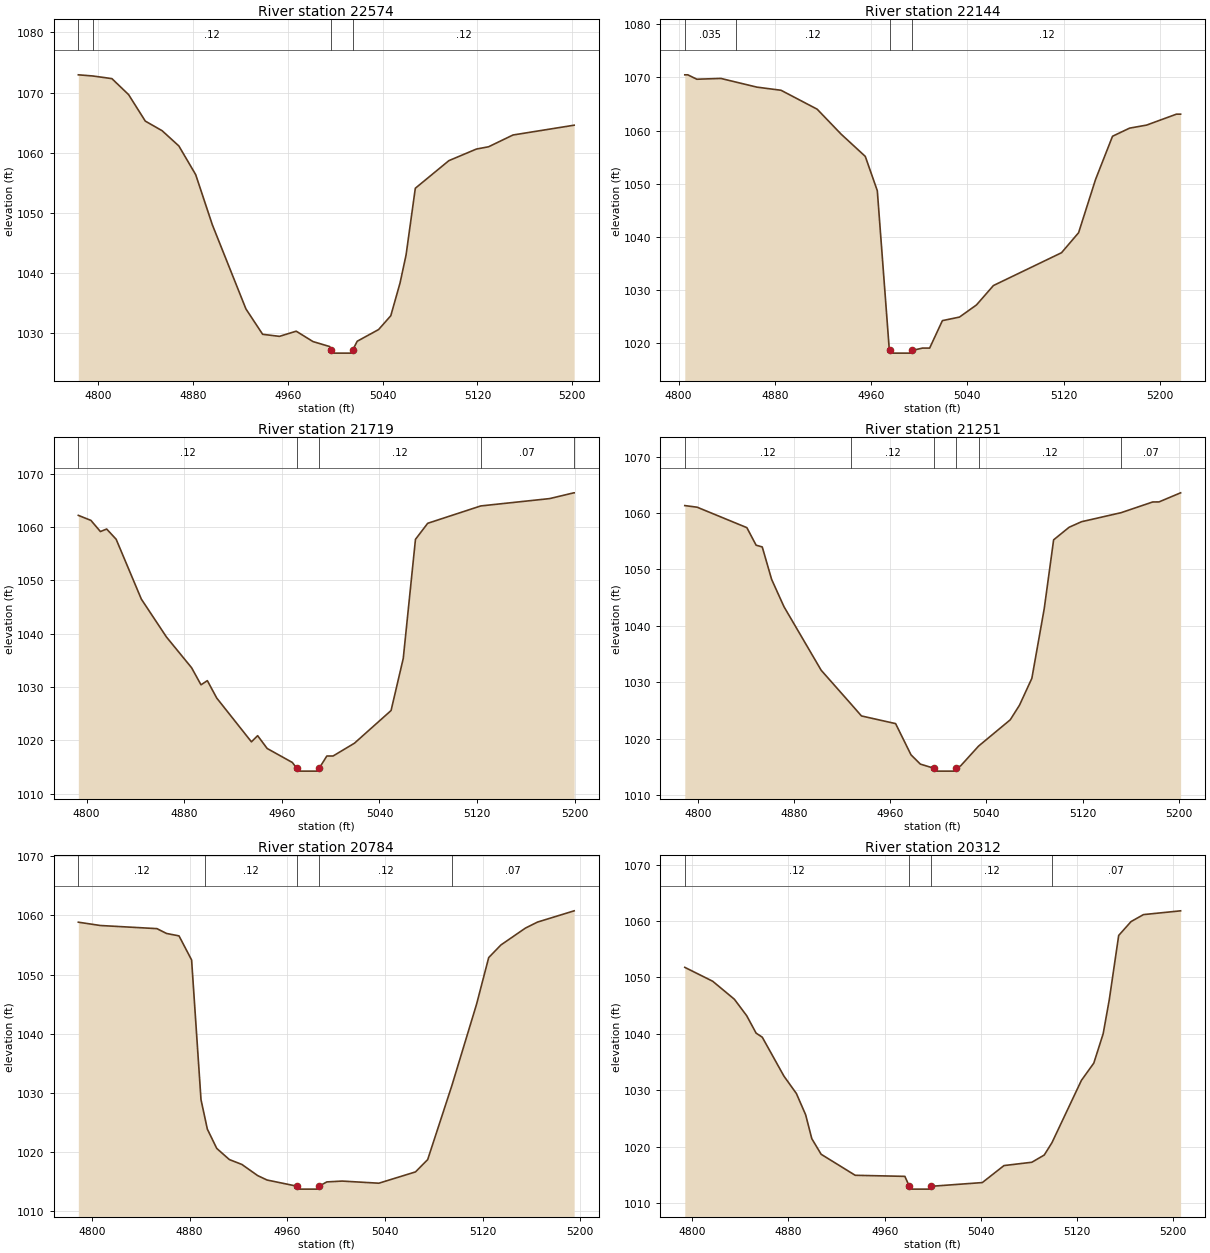
Type RM Length L Ch R = 1 ,22574   ,430,430,430
BEGIN DESCRIPTION:
Rebecca Creek 40.0
END DESCRIPTION:
XS GIS Cut Line= 3
      2168024.98     13883825.02        2167875.       13883975.
      2167824.99     13884175.04
#Sta/Elev= 30
  4783.3 1072.95  4795.4 1072.76  4811.6 1072.32  4825.7 1069.66  4839.8 1065.25
    4854 1063.65  4868.1 1061.12  4882.3 1056.35  4896.4 1047.98  4924.7    1034
  4938.8 1029.78    4953 1029.44  4967.1  1030.3  4981.3 1028.57  4995.4 1027.74
  4996.7 1027.15  4997.2 1026.65  5014.2 1026.65  5014.7 1027.15  5018.6 1028.63
  5036.6 1030.57  5046.9 1032.87  5054.7 1038.31  5059.8 1042.99  5067.6 1054.08
  5095.9 1058.67  5119.1  1060.6  5129.4 1060.98    5150 1062.94  5201.6 1064.57
#Mann= 4 ,-1 , 0
  4783.3    .035       0  4795.4     .12       0  4996.7     .05       0
  5014.7     .12       0
Bank Sta=4996.7,5014.7
XS Rating Curve= 0 ,0
Exp/Cntr=0.3,0.1

Type RM Length L Ch R = 1 ,22144   ,425,425,425
BEGIN DESCRIPTION:
Rebecca Creek 39.0
END DESCRIPTION:
XS GIS Cut Line= 3
        2167475.     13883775.02        2167475.       13883975.
      2167624.99     13884124.99
#Sta/Elev= 30
  4805.1  1070.5  4807.6  1070.5  4815.1 1069.67  4835.1 1069.82  4847.3 1069.15
  4865.1 1068.18  4885.1 1067.59  4915.1 1064.03  4935.1 1059.31  4955.1 1055.14
  4965.1 1048.68  4975.1 1018.62    4976 1018.58  4976.5 1018.08  4993.6 1018.08
  4994.1 1018.58  5002.6 1019.03  5008.6 1019.03  5019.2  1024.2  5033.4 1024.87
  5047.5 1027.15  5061.6 1030.81  5118.2 1036.99  5132.4 1040.76  5146.5 1050.79
  5160.6 1058.93  5174.8 1060.46  5188.9 1061.03  5213.7 1063.09  5217.2 1063.09
#Mann= 4 ,-1 , 0
  4805.1    .035       0  4847.3     .12       0    4976     .05       0
  4994.1     .12       0
Bank Sta=4976,4994.1
XS Rating Curve= 0 ,0
Exp/Cntr=0.3,0.1

Type RM Length L Ch R = 1 ,21719   ,468,468,468
BEGIN DESCRIPTION:
Rebecca Creek 38.0
END DESCRIPTION:
XS GIS Cut Line= 3
      2167175.01     13883974.97        2167125.       13884175.
        2167125.     13884375.01
#Sta/Elev= 30
  4793.3 1062.21  4803.6 1061.27  4811.4 1059.17  4816.5 1059.65  4824.3 1057.72
  4844.9  1046.5  4865.5 1039.38  4886.1 1033.61  4893.8 1030.41    4899 1031.19
  4906.7 1027.92  4935.1 1019.71  4940.2 1020.86    4948 1018.46  4968.6 1015.84
  4972.4 1014.71  4972.9 1014.21    4990 1014.21  4990.5 1014.71  4996.9 1017.05
    5002 1017.05  5019.5 1019.45  5049.5 1025.58  5059.5 1035.37  5069.5 1057.71
  5079.5 1060.72    5123 1063.98  5179.5 1065.36  5199.2 1066.44  5199.5 1066.44
#Mann= 5 ,-1 , 0
  4793.3     .12       0  4972.4     .05       0  4990.5     .12       0
    5123     .07       0  5199.2    .035       0
Bank Sta=4972.4,4990.5
XS Rating Curve= 0 ,0
Exp/Cntr=0.3,0.1

Type RM Length L Ch R = 1 ,21251   ,467,467,467
BEGIN DESCRIPTION:
Rebecca Creek 37.0
END DESCRIPTION:
XS GIS Cut Line= 3
        2166775.     13883774.98        2166725.       13883975.
      2166675.01     13884174.97
#Sta/Elev= 30
  4789.2 1061.32  4799.5 1061.03  4840.8 1057.41  4848.5  1054.3  4853.6 1053.99
  4861.4 1048.24  4871.7 1043.39  4902.6 1032.14  4927.6 1026.11  4936.1 1024.04
  4964.5 1022.68  4977.3 1017.15  4985.1  1015.5  4996.6 1014.76  4997.1 1014.26
  5014.2 1014.26  5014.7 1014.76  5018.6  1015.2  5033.5  1018.7  5059.8 1023.35
  5067.5 1025.94  5077.8 1030.71  5088.1 1043.07  5095.9 1055.25  5108.8 1057.48
  5119.1 1058.46    5152 1060.06  5178.3 1061.96  5183.5 1061.97  5201.5 1063.58
#Mann= 6 ,-1 , 0
  4789.2     .12       0  4927.6     .12       0  4996.6     .05       0
  5014.7     .12       0  5033.5     .12       0    5152     .07       0
Bank Sta=4996.6,5014.7
XS Rating Curve= 0 ,0
Exp/Cntr=0.3,0.1

Type RM Length L Ch R = 1 ,20784   ,472,472,472
BEGIN DESCRIPTION:
Rebecca Creek 36.0
END DESCRIPTION:
XS GIS Cut Line= 3
        2166375.     13883574.99        2166325.       13883775.
        2166325.     13883975.04
#Sta/Elev= 30
  4788.8 1058.85  4806.8 1058.29  4853.2 1057.76    4861 1056.95  4871.3 1056.53
  4881.6 1052.46  4889.3 1028.85  4892.5 1025.79  4894.5 1023.87  4902.2 1020.61
  4912.5 1018.73  4922.8  1017.9  4935.7 1016.02  4943.4 1015.27  4967.8 1014.23
  4968.3 1013.73  4985.5 1013.73    4986 1014.23  4992.4 1014.95    5005 1015.09
    5035 1014.73    5065 1016.64    5075 1018.72  5094.8 1031.22    5115 1044.95
    5125 1052.87    5135    1055    5155 1057.84    5165 1058.87    5195 1060.77
#Mann= 5 ,-1 , 0
  4788.8     .12       0  4892.5     .12       0  4967.8     .05       0
    4986     .12       0  5094.8     .07       0
Bank Sta=4967.8,4986
XS Rating Curve= 0 ,0
Exp/Cntr=0.3,0.1

Type RM Length L Ch R = 1 ,20312   ,463,463,463
BEGIN DESCRIPTION:
Rebecca Creek 35.0
END DESCRIPTION:
XS GIS Cut Line= 3
      2166124.99       13883525.        2165925.       13883575.
        2165875.       13883775.
#Sta/Elev= 30
  4793.8 1051.79    4817 1049.33    4835 1046.15  4845.3 1043.22  4853.1 1040.14
  4858.2 1039.43  4876.3 1032.51  4886.6 1029.45  4894.3 1025.68  4899.4 1021.46
  4907.2 1018.69  4935.5 1014.97  4976.8 1014.78  4980.5 1013.02    4981 1012.52
  4998.2 1012.52  4998.7 1013.02  5041.2 1013.68  5059.2 1016.69  5082.4 1017.28
  5092.7 1018.56  5099.1 1020.74  5123.6 1031.78  5133.9 1034.83  5141.7 1040.04
  5146.8 1046.09  5154.6 1057.44  5164.9  1059.9  5175.2 1061.13  5206.1  1061.8
#Mann= 4 ,-1 , 0
  4793.8     .12       0  4980.5     .05       0  4998.7     .12       0
  5099.1     .07       0
Bank Sta=4980.5,4998.7
XS Rating Curve= 0 ,0
Exp/Cntr=0.3,0.1