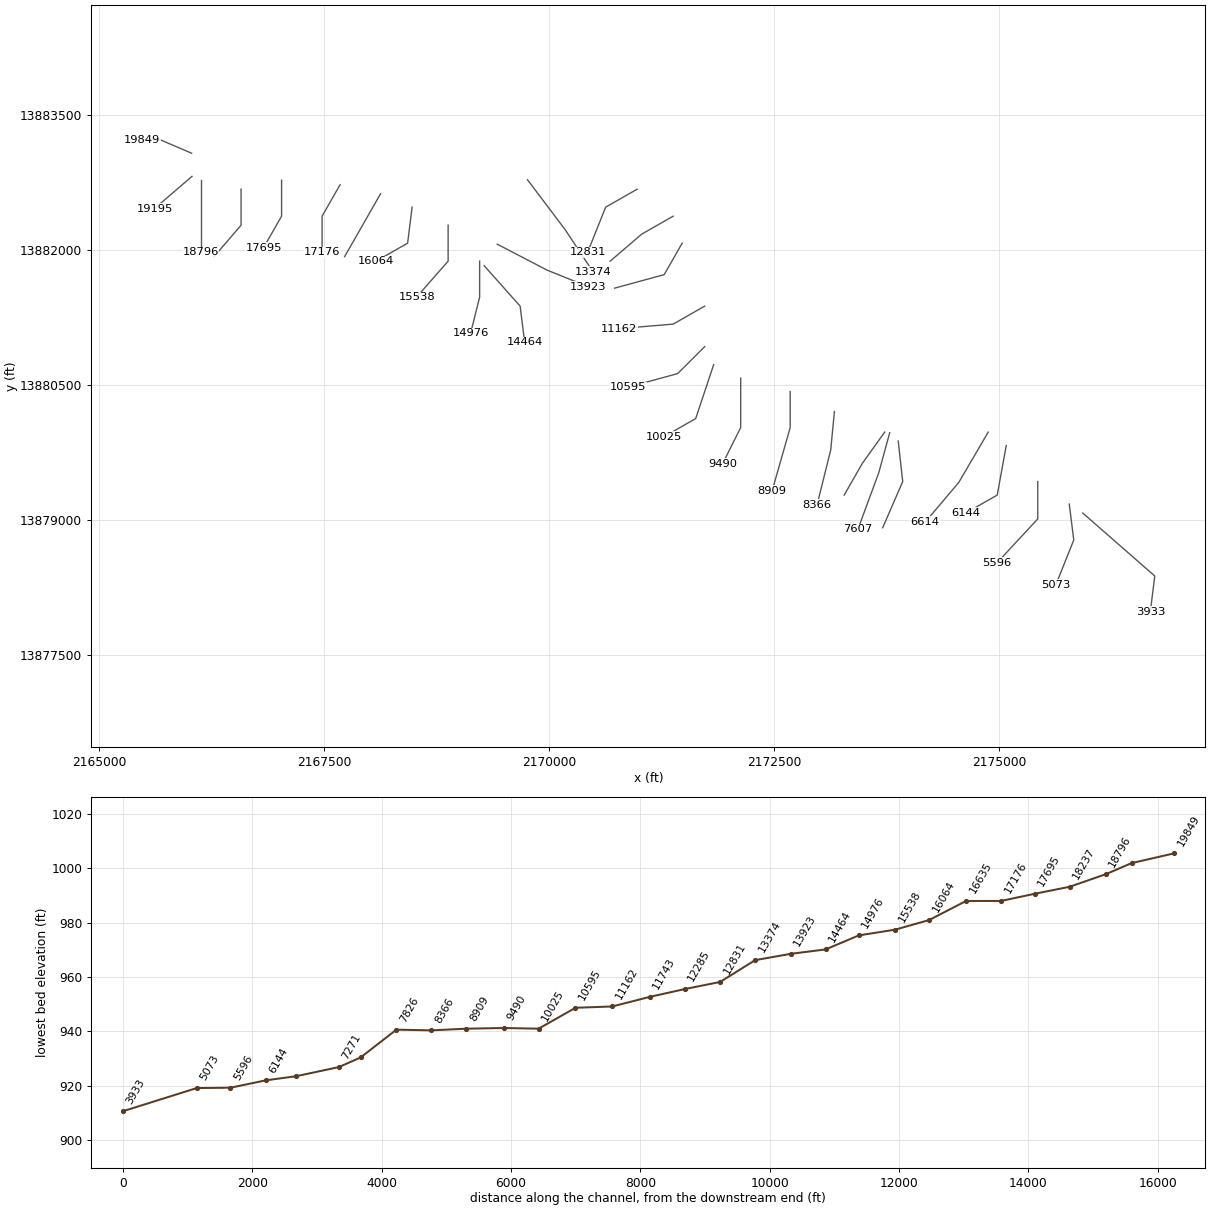
HEC-RAS study Rebecca Creek.prj: Rebecca Creek Base Level Engineering

--- Rebecca Creek.g01 (geometry) --- (continued)

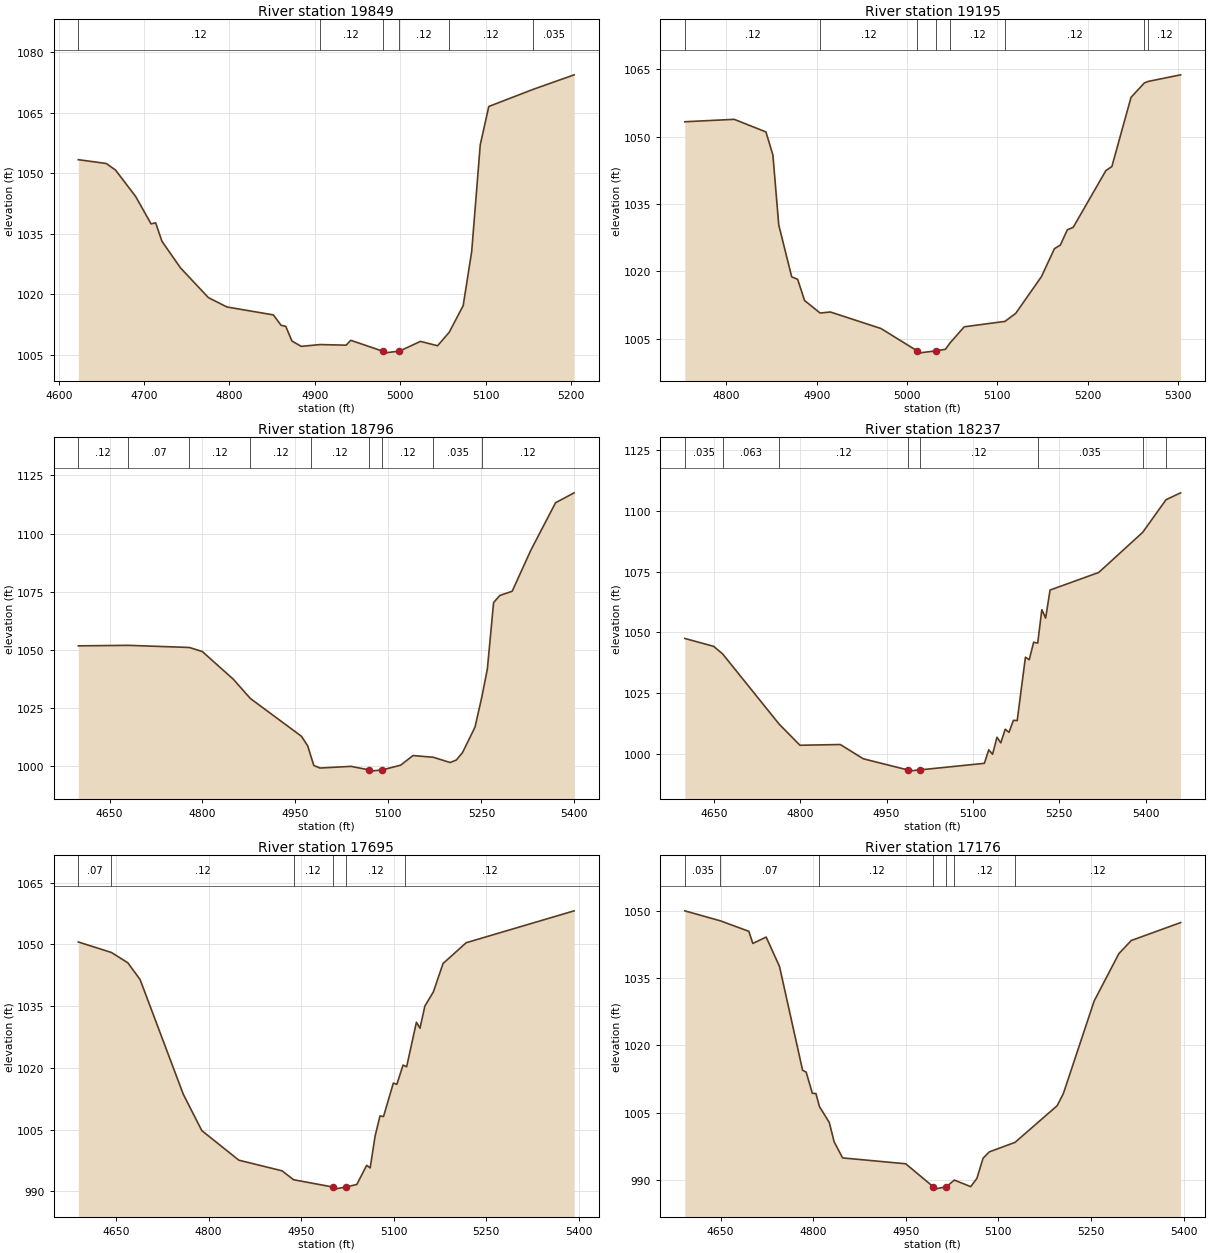
Type RM Length L Ch R = 1 ,19849   ,654,654,654
BEGIN DESCRIPTION:
Rebecca Creek 34.0
END DESCRIPTION:
XS GIS Cut Line= 3
      2166024.98     13883075.01        2165675.       13883225.
      2165474.97       13883225.
#Sta/Elev= 30
    4623 1053.33  4655.6 1052.39  4666.5 1050.78  4690.1 1044.23  4708.2 1037.43
  4713.6 1037.68  4720.9 1033.14  4742.7 1026.52  4775.3 1019.17  4797.1 1016.84
  4851.5 1014.88  4860.5  1012.3    4866 1012.05  4873.2 1008.41  4884.1 1007.09
  4906.3 1007.53  4936.7 1007.38  4942.1 1008.59  4979.3 1005.91  4979.8 1005.41
  4999.2 1005.91  5023.8 1008.32  5043.8 1007.24  5057.4 1010.56  5073.8 1017.18
  5083.8 1030.62  5093.8 1057.01  5103.8 1066.51    5156 1070.77  5203.8 1074.35
#Mann= 6 ,-1 , 0
    4623     .12       0  4906.3     .12       0  4979.3     .05       0
  4999.2     .12       0  5057.4     .12       0    5156    .035       0
Bank Sta=4979.3,4999.2
XS Rating Curve= 0 ,0
Exp/Cntr=0.3,0.1

Type RM Length L Ch R = 1 ,19195   ,399,399,399
BEGIN DESCRIPTION:
Rebecca Creek 33.1
END DESCRIPTION:
XS GIS Cut Line= 2
      2166029.48     13882817.33      2165613.39     13882459.49
#Sta/Elev= 30
    4754 1053.31  4808.7 1053.85  4843.8 1051.05  4851.5 1045.93    4858 1030.36
  4872.3 1018.82  4878.9 1018.26  4886.6 1013.54  4903.8 1010.76  4915.1 1010.99
  4971.1 1007.32  5011.2 1002.34  5011.7 1001.84  5031.8 1002.34  5042.4 1002.69
  5047.6 1004.11  5063.3  1007.7  5108.4  1008.9  5120.3 1010.69  5148.8 1018.88
  5163.1 1025.07  5169.7 1025.89  5177.4 1029.27  5183.9 1029.82  5220.1 1042.46
  5226.7 1043.35  5247.9 1058.73  5262.7 1061.96  5267.1 1062.29  5302.8 1063.75
#Mann= 8 ,-1 , 0
    4754     .12       0  4903.8     .12       0  5011.2     .05       0
  5031.8     .12       0  5047.6     .12       0  5108.4     .12       0
  5262.7     .12       0  5267.1     .12       0
Bank Sta=5011.2,5031.8
XS Rating Curve= 0 ,0
Exp/Cntr=0.3,0.1

Type RM Length L Ch R = 1 ,18796   ,559,559,559
BEGIN DESCRIPTION:
Rebecca Creek 33.0
END DESCRIPTION:
XS GIS Cut Line= 3
        2166125.     13882774.99        2166125.       13882375.
        2166125.     13881974.99
#Sta/Elev= 30
  4599.7 1051.67  4680.5 1051.89  4778.9 1050.97  4799.7 1049.23  4849.7 1037.33
  4877.2 1029.04  4959.7 1012.77  4969.7 1008.67  4975.6 1003.67  4979.7 1000.19
  4989.7   999.1  5039.7  999.82  5069.3  998.27  5069.8  997.77    5090  998.27
  5119.7 1000.33  5139.7 1004.48  5172.3 1003.74  5199.7 1001.47  5209.7 1002.57
  5219.7 1005.81  5239.7 1016.68  5250.9 1029.85  5259.7 1041.79  5269.7 1070.29
  5279.7 1073.34  5299.7 1075.16  5329.7 1092.76  5369.7 1113.25  5399.7 1117.51
#Mann= 9 ,-1 , 0
  4599.7     .12       0  4680.5     .07       0  4778.9     .12       0
  4877.2     .12       0  4975.6     .12       0  5069.3     .05       0
    5090     .12       0  5172.3    .035       0  5250.9     .12       0
Bank Sta=5069.3,5090
XS Rating Curve= 0 ,0
Exp/Cntr=0.3,0.1

Type RM Length L Ch R = 1 ,18237   ,542,542,542
BEGIN DESCRIPTION:
Rebecca Creek 32.0
END DESCRIPTION:
XS GIS Cut Line= 3
        2166575.     13882674.97        2166575.       13882275.
      2166274.97     13881924.96
#Sta/Elev= 30
  4599.6 1047.55  4649.6 1044.32  4665.1 1041.27  4763.5  1012.4  4799.6 1003.75
  4869.6 1004.05  4909.6   998.2  4986.7  993.64  4987.2  993.14  5007.5  993.64
  5119.8  996.34  5127.4 1001.87    5134 1000.04  5141.7 1007.05  5148.3 1004.73
    5156 1010.33  5162.6 1009.05  5170.2 1013.97  5176.8 1013.86  5191.1 1039.86
  5197.7 1038.83  5205.4 1046.01  5212.4 1045.64  5219.6 1059.35  5226.2  1055.9
  5233.9  1067.4  5318.4 1074.61  5394.8 1091.09  5435.3 1104.46  5460.6 1107.27
#Mann= 8 ,-1 , 0
  4599.6    .035       0  4665.1    .063       0  4763.5     .12       0
  4986.7     .05       0  5007.5     .12       0  5212.4    .035       0
  5394.8     .12       0  5435.3    .035       0
Bank Sta=4986.7,5007.5
XS Rating Curve= 0 ,0
Exp/Cntr=0.3,0.1

Type RM Length L Ch R = 1 ,17695   ,519,519,519
BEGIN DESCRIPTION:
Rebecca Creek 31.0
END DESCRIPTION:
XS GIS Cut Line= 3
        2167025.     13882775.04        2167025.       13882375.
      2166825.02     13882025.04
#Sta/Elev= 30
  4589.1  1050.6  4642.7 1048.05  4669.1 1045.57  4689.1 1041.49  4759.1 1013.61
  4789.1 1004.78  4849.1  997.59  4919.1  995.01  4937.8  992.84  5001.8  991.06
  5002.3  990.56  5022.6  991.06  5040.2   991.7  5056.1  996.34  5061.8  995.72
  5069.8 1003.45  5077.7 1008.35  5083.4 1008.19  5099.3 1016.32    5105 1016.02
  5115.1 1020.69  5118.5 1020.46  5120.9  1020.3  5136.7 1031.11  5142.5 1029.65
  5150.4 1035.03  5164.1 1038.46  5179.9 1045.38  5217.3 1050.42  5392.2 1058.17
#Mann= 6 ,-1 , 0
  4589.1     .07       0  4642.7     .12       0  4937.8     .12       0
  5001.8     .05       0  5022.6     .12       0  5118.5     .12       0
Bank Sta=5001.8,5022.6
XS Rating Curve= 0 ,0
Exp/Cntr=0.3,0.1

Type RM Length L Ch R = 1 ,17176   ,541,541,541
BEGIN DESCRIPTION:
Rebecca Creek 30.0
END DESCRIPTION:
XS GIS Cut Line= 3
      2167675.02     13882725.03        2167475.       13882375.
        2167475.     13881975.05
#Sta/Elev= 30
    4592 1050.06  4649.3 1047.84  4695.7 1045.49  4702.2 1042.78  4723.8  1044.2
  4745.4 1037.64  4782.8 1014.47  4788.6 1014.06  4798.6 1009.31  4804.4 1009.27
  4810.1 1006.36    4826 1002.82  4833.9  998.49  4847.6   994.9  4949.8  993.59
  4994.7  988.43  4995.2  987.93  5015.6  988.43  5028.5  989.95  5055.1  988.49
  5065.1  990.31  5075.1  994.82  5085.1  996.24  5126.9  998.37  5195.1 1006.55
  5205.1 1009.24  5255.1 1029.94  5295.1 1040.51  5315.1 1043.43  5395.1 1047.44
#Mann= 7 ,-1 , 0
    4592    .035       0  4649.3     .07       0  4810.1     .12       0
  4994.7     .05       0  5015.6     .12       0  5028.5     .12       0
  5126.9     .12       0
Bank Sta=4994.7,5015.6
XS Rating Curve= 0 ,0
Exp/Cntr=0.3,0.1

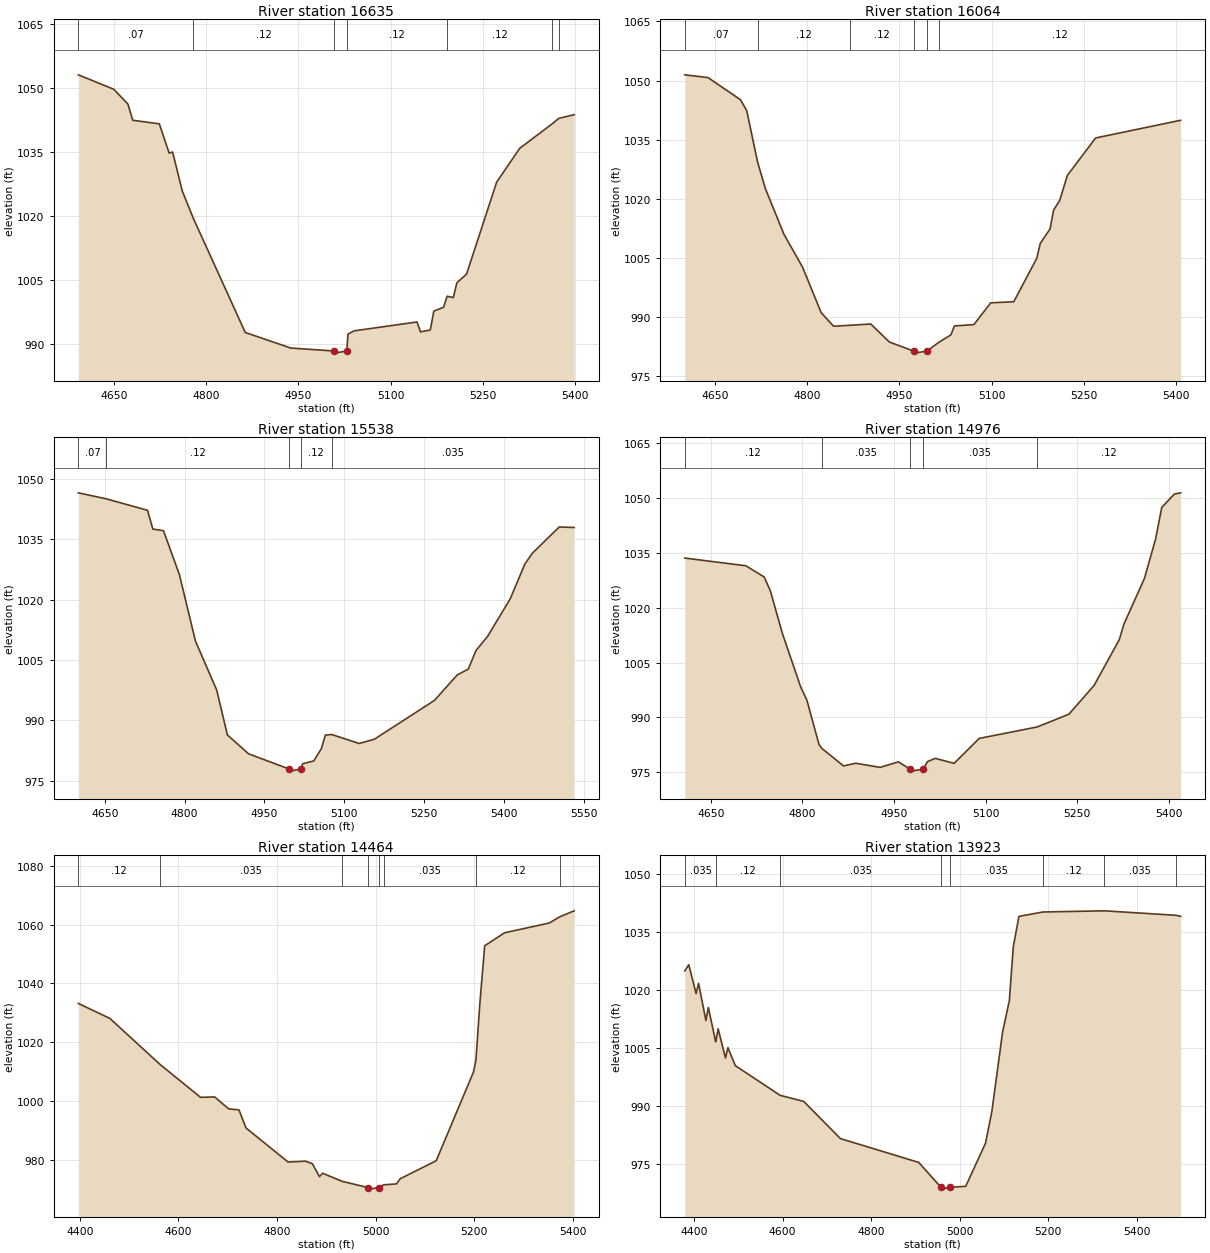
Type RM Length L Ch R = 1 ,16635   ,571,571,571
BEGIN DESCRIPTION:
Rebecca Creek 29.0
END DESCRIPTION:
XS GIS Cut Line= 3
      2168124.99     13882624.99        2167925.       13882275.
        2167725.     13881925.01
#Sta/Elev= 30
  4592.3 1053.13  4649.9 1049.75  4672.9 1046.28  4680.8 1042.48    4724 1041.65
  4739.9  1034.8  4745.6 1035.03  4761.4 1025.88    4779  1019.6  4863.7  992.76
  4937.8  989.11    5008  988.42  5008.5  987.92  5028.9  988.42  5030.7  992.38
  5040.7  993.14    5143  995.22  5148.7   992.9  5164.6  993.34  5170.3  997.76
  5186.2  998.67  5191.9 1001.25    5202 1000.94  5207.8 1004.38  5223.6 1006.46
  5272.5 1027.99    5310 1035.91  5362.5 1041.62  5373.6 1042.93  5398.5 1043.79
#Mann= 7 ,-1 , 0
  4592.3     .07       0    4779     .12       0    5008     .05       0
  5028.9     .12       0  5191.9     .12       0  5362.5     .12       0
  5373.6    .035       0
Bank Sta=5008,5028.9
XS Rating Curve= 0 ,0
Exp/Cntr=0.3,0.1

Type RM Length L Ch R = 1 ,16064   ,526,526,526
BEGIN DESCRIPTION:
Rebecca Creek 28.0
END DESCRIPTION:
XS GIS Cut Line= 3
        2168475.     13882475.02        2168425.       13882075.
      2168075.04     13881875.02
#Sta/Elev= 30
  4601.2 1051.44    4639 1050.74  4691.9 1045.11    4702  1042.3  4719.6 1029.31
  4732.2 1022.62  4762.5    1011  4792.7 1002.69  4822.9  991.18  4843.1  987.73
  4870.2  987.97  4903.6  988.29  4933.8  983.73  4973.6  981.41  4974.1  980.91
  4994.7  981.41  5014.9  983.72  5033.8  985.53  5039.6   987.8  5071.3  988.14
  5098.6  993.66  5136.1  993.93  5173.5 1004.95  5179.3 1008.75  5195.1 1012.37
  5200.9 1017.14  5210.9 1019.65  5223.2 1025.94  5269.2 1035.44  5407.4 1039.92
#Mann= 6 ,-1 , 0
  4601.2     .07       0  4719.6     .12       0  4870.2     .12       0
  4973.6     .05       0  4994.7     .12       0  5014.9     .12       0
Bank Sta=4973.6,4994.7
XS Rating Curve= 0 ,0
Exp/Cntr=0.3,0.1

Type RM Length L Ch R = 1 ,15538   ,562,562,562
BEGIN DESCRIPTION:
Rebecca Creek 27.0
END DESCRIPTION:
XS GIS Cut Line= 3
        2168875.     13882275.02        2168875.       13881875.
      2168525.02     13881475.02
#Sta/Elev= 30
  4600.3 1046.54  4652.9 1045.04  4730.3  1042.2  4740.3 1037.53  4760.3 1037.13
  4790.3 1026.16  4820.3 1009.71  4860.3  997.51  4880.3  986.37  4920.3  981.66
  4996.9  977.87  4997.4  977.37    5018  977.87  5021.7   979.2  5042.6   979.9
  5056.8  982.93  5064.4  986.33  5076.3  986.47    5128  984.24  5156.4  985.29
  5269.4  994.95  5312.1 1001.28    5333 1002.74  5347.2  1007.3    5369 1010.83
  5411.8 1020.22  5439.3 1028.87  5453.5 1031.56  5503.8 1038.05  5531.8 1037.92
#Mann= 5 ,-1 , 0
  4600.3     .07       0  4652.9     .12       0  4996.9     .05       0
    5018     .12       0  5076.3    .035       0
Bank Sta=4996.9,5018
XS Rating Curve= 0 ,0
Exp/Cntr=0.3,0.1

Type RM Length L Ch R = 1 ,14976   ,512,512,512
BEGIN DESCRIPTION:
Rebecca Creek 26.0
END DESCRIPTION:
XS GIS Cut Line= 3
        2169225.     13881874.98        2169225.       13881475.
        2169125.     13881074.99
#Sta/Elev= 30
  4607.3 1033.61  4707.3 1031.51  4737.3 1028.44  4747.3 1024.72  4767.3 1012.91
  4797.3  998.25  4807.3   994.7  4827.3   982.5  4831.6  981.52  4867.3  976.68
  4887.3  977.42  4927.3  976.29  4957.3   977.8  4976.7  975.76  4977.2  975.26
  4997.9  975.76  5004.8  977.85  5017.6  978.76  5048.5  977.39  5089.7  984.22
  5184.7  987.36  5236.6  990.85  5277.9  998.74  5319.1 1011.26  5326.8 1015.55
  5360.3 1028.03  5378.4 1038.71  5388.7 1047.48  5409.3 1051.14  5419.6 1051.48
#Mann= 5 ,-1 , 0
  4607.3     .12       0  4831.6    .035       0  4976.7    .035       0
  4997.9    .035       0  5184.7     .12       0
Bank Sta=4976.7,4997.9
XS Rating Curve= 0 ,0
Exp/Cntr=0.3,0.1

Type RM Length L Ch R = 1 ,14464   ,541,541,541
BEGIN DESCRIPTION:
Rebecca Creek 25.0
END DESCRIPTION:
XS GIS Cut Line= 3
      2169275.01     13881824.99        2169675.       13881375.
        2169725.     13880974.97
#Sta/Elev= 30
  4397.1 1033.22  4461.1 1028.12  4563.2 1012.42    4645  1001.3  4673.5 1001.44
  4701.9  997.39  4722.8  997.03    4737   990.9  4822.3  979.32  4857.4  979.61
  4871.6  978.75  4885.9  974.37  4892.5  975.49  4932.5  972.73  4985.2  970.61
  4985.7  970.11  5006.4  970.61  5015.9  971.57    5042  971.88  5049.6  973.64
  5122.6  979.75  5198.2  1009.9  5202.4 1013.35  5203.2 1014.01  5210.8 1032.53
  5220.9  1052.8  5261.2 1057.23  5351.9 1060.55  5373.5 1062.69  5402.3 1064.69
#Mann= 8 ,-1 , 0
  4397.1     .12       0  4563.2    .035       0  4932.5     .12       0
  4985.2     .05       0  5006.4     .12       0  5015.9    .035       0
  5202.4     .12       0  5373.5    .035       0
Bank Sta=4985.2,5006.4
XS Rating Curve= 0 ,0
Exp/Cntr=0.3,0.1

Type RM Length L Ch R = 1 ,13923   ,549,549,549
BEGIN DESCRIPTION:
Rebecca Creek 24.0
END DESCRIPTION:
XS GIS Cut Line= 3
      2169420.91     13882063.57        2169975.       13881775.
      2170433.47      13881589.8
#Sta/Elev= 30
  4379.4 1024.87  4388.4 1026.48  4404.9 1019.03  4410.5 1021.67    4427 1012.06
  4432.6 1015.41  4449.1 1006.55  4450.8 1007.57  4454.7 1009.91  4471.2 1002.38
  4476.8 1005.04  4493.3  1000.4  4594.6  992.72  4647.9  991.14  4730.7  981.54
  4907.5  975.38  4957.5  968.98    4958  968.48  4978.8  968.98  5013.5   969.2
  5058.1  980.32  5072.6  988.58  5096.7 1009.05    5112 1017.21  5120.8 1031.03
  5133.6 1038.97  5188.2  1040.1  5326.6  1040.4  5487.3 1039.25  5498.6 1038.98
#Mann= 8 ,-1 , 0
  4379.4    .035       0  4450.8     .12       0  4594.6    .035       0
  4957.5    .035       0  4978.8    .035       0  5188.2     .12       0
  5326.6    .035       0  5487.3    .063       0
Bank Sta=4957.5,4978.8
XS Rating Curve= 0 ,0
Exp/Cntr=0.3,0.1

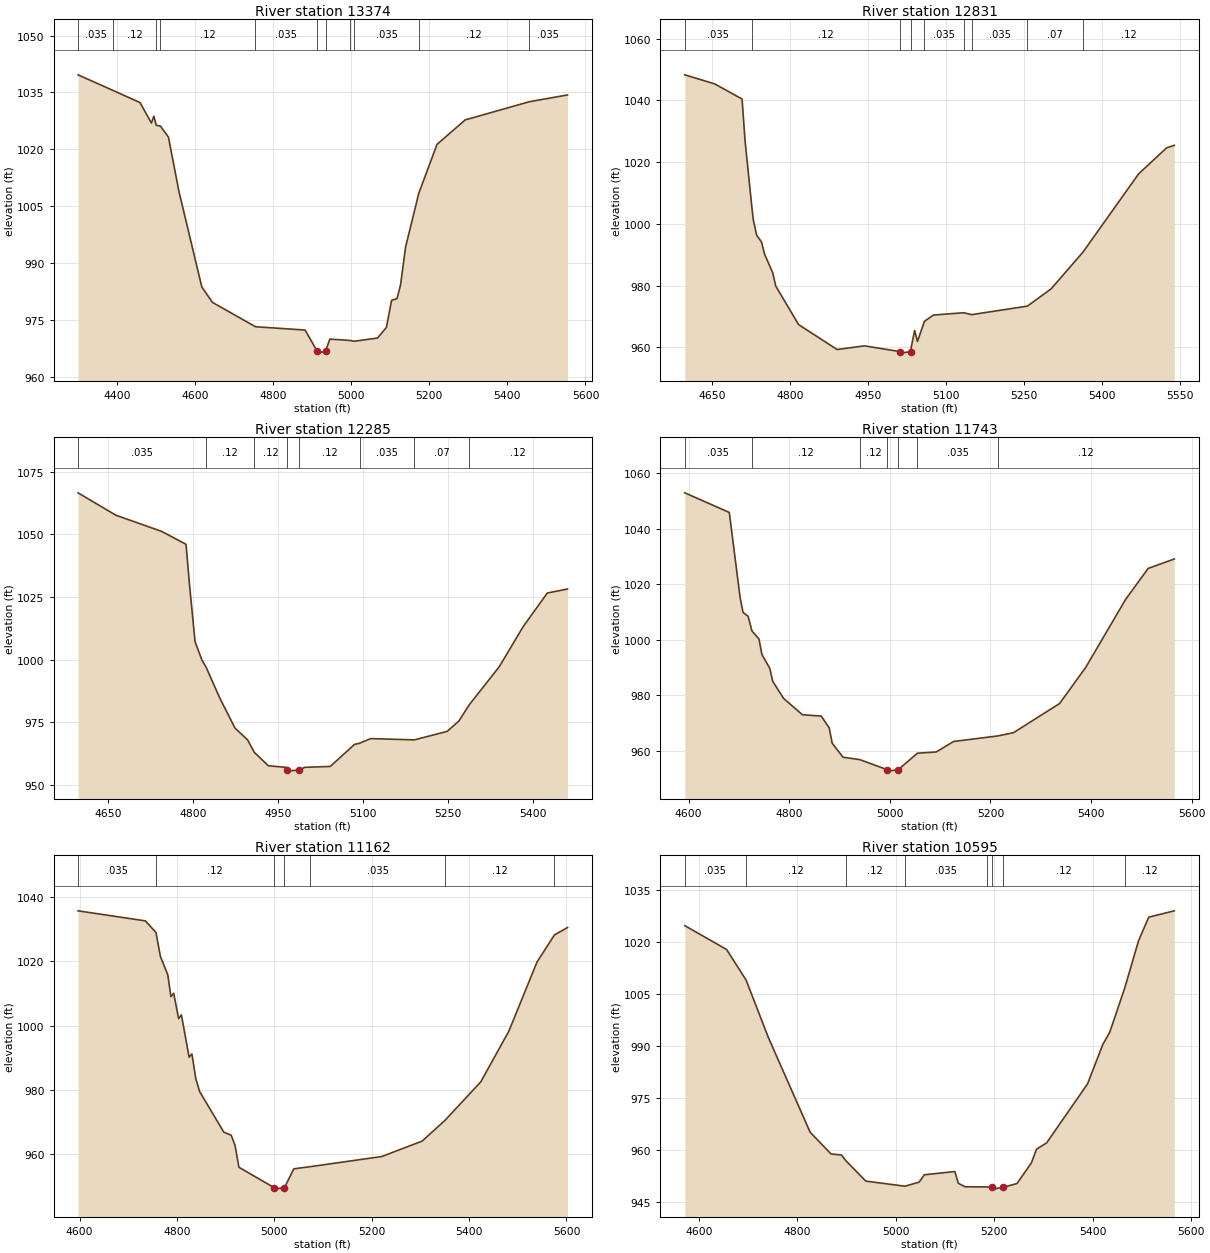
Type RM Length L Ch R = 1 ,13374   ,543,543,543
BEGIN DESCRIPTION:
Rebecca Creek 23.0
END DESCRIPTION:
XS GIS Cut Line= 3
       2169756.8     13882779.76        2170175.       13882225.
      2170483.05     13881759.41
#Sta/Elev= 30
    4301 1039.63  4391.5 1035.47  4459.7 1032.31  4488.8  1026.9  4495.1 1028.73
  4501.4  1026.3  4511.9 1026.11  4532.4 1023.21  4559.6 1008.74  4617.9  983.64
  4645.1  979.57  4755.3  973.14  4882.3  972.26  4913.2  966.67  4913.7  966.17
  4934.6  966.67  4945.6  969.87  4996.9  969.52  5008.3   969.3  5067.7  970.16
  5090.5  972.96  5103.6   980.1  5117.6  980.56  5126.6  984.18  5139.6  994.21
  5173.3 1008.36  5219.9 1021.27  5292.1 1027.73  5456.3 1032.53    5554 1034.32
#Mann= 11 ,-1 , 0
    4301    .035       0  4391.5     .12       0  4501.4    .035       0
  4511.9     .12       0  4755.3    .035       0  4913.2     .05       0
  4934.6    .035       0  4996.9     .12       0  5008.3    .035       0
  5173.3     .12       0  5456.3    .035       0
Bank Sta=4913.2,4934.6
XS Rating Curve= 0 ,0
Exp/Cntr=0.3,0.1

Type RM Length L Ch R = 1 ,12831   ,546,546,546
BEGIN DESCRIPTION:
Rebecca Creek 22.0
END DESCRIPTION:
XS GIS Cut Line= 3
      2170975.03     13882675.02        2170625.       13882475.
      2170424.99     13881974.97
#Sta/Elev= 30
  4597.7  1048.3  4655.3 1045.36  4707.9 1040.46  4713.6 1027.06  4726.5 1005.79
  4729.5 1001.35  4735.9  996.36  4745.3  994.14  4751.1  990.26  4766.9  984.13
  4772.7  979.88  4816.6  967.39  4890.7  959.31  4943.3   960.5  5011.6  958.64
  5012.1  958.14  5033.1  958.64  5033.2  959.96  5039.9   965.5  5045.3   961.9
  5058.7  968.44  5076.2  970.48  5134.3  971.22  5149.5  970.61  5256.8  973.37
  5302.4  978.95    5364  990.92  5470.7  1016.2  5524.6 1024.65  5539.4 1025.47
#Mann= 9 ,-1 , 0
  4597.7    .035       0  4726.5     .12       0  5011.6     .05       0
  5033.1     .12       0  5058.7    .035       0  5134.3     .12       0
  5149.5    .035       0  5256.8     .07       0    5364     .12       0
Bank Sta=5011.6,5033.1
XS Rating Curve= 0 ,0
Exp/Cntr=0.3,0.1

Type RM Length L Ch R = 1 ,12285   ,542,542,542
BEGIN DESCRIPTION:
Rebecca Creek 21.0
END DESCRIPTION:
XS GIS Cut Line= 3
      2171374.97     13882374.98        2171025.       13882175.
      2170674.97     13881874.97
#Sta/Elev= 30
  4596.9 1066.58  4663.8 1057.64  4744.4 1051.21  4787.6 1046.03  4793.4  1030.7
  4803.5 1007.19  4815.7  999.79  4823.1  996.98  4846.7  984.92    4874  972.71
  4896.3     968  4908.1  963.03    4933  957.65  4964.7  957.04  4966.1  956.03
  4966.6  955.53  4987.7  956.03  4997.1  957.04  5042.2   957.4    5085  966.19
    5094  966.66  5113.6  968.51  5190.7     968  5248.6   971.4  5269.4  975.55
  5287.1  981.88  5340.8  997.28  5382.5 1013.12  5425.3 1026.59    5461 1028.21
#Mann= 8 ,-1 , 0
  4596.9    .035       0  4823.1     .12       0  4908.1     .12       0
  4966.1     .05       0  4987.7     .12       0    5094    .035       0
  5190.7     .07       0  5287.1     .12       0
Bank Sta=4966.1,4987.7
XS Rating Curve= 0 ,0
Exp/Cntr=0.3,0.1

Type RM Length L Ch R = 1 ,11743   ,581,581,581
BEGIN DESCRIPTION:
Rebecca Creek 20.0
END DESCRIPTION:
XS GIS Cut Line= 3
      2171474.99     13882074.98        2171275.       13881725.
      2170724.98     13881574.99
#Sta/Elev= 30
  4592.3 1052.94  4680.8 1045.87  4702.4 1015.03  4708.2 1009.84  4718.3 1008.43
  4725.8 1003.18  4739.8 1000.27  4745.6  994.69  4761.4  989.65  4767.2     985
  4788.8  978.84  4826.2  972.98  4863.7  972.48  4879.5  968.21  4885.3  962.74
  4906.9  957.66  4940.2   956.8    4995  953.15  4995.5  952.65  5016.6  953.15
  5054.8  959.11  5092.1  959.55  5126.7  963.33  5214.5  965.33  5245.9  966.51
  5337.4     977  5389.3     990  5468.7 1014.53  5513.7 1025.71  5565.5  1029.1
#Mann= 7 ,-1 , 0
  4592.3    .035       0  4725.8     .12       0  4940.2     .12       0
    4995     .05       0  5016.6     .12       0  5054.8    .035       0
  5214.5     .12       0
Bank Sta=4995,5016.6
XS Rating Curve= 0 ,0
Exp/Cntr=0.3,0.1

Type RM Length L Ch R = 1 ,11162   ,567,567,567
BEGIN DESCRIPTION:
Rebecca Creek 19.0
END DESCRIPTION:
XS GIS Cut Line= 3
      2171724.99       13881375.        2171375.       13881175.
      2170774.99       13881125.
#Sta/Elev= 30
  4596.9 1035.77  4735.1 1032.65    4757 1029.03  4766.1 1021.56  4781.2 1015.88
  4787.7 1009.05  4793.4 1010.11  4803.5 1002.21  4809.2 1003.38  4825.1   990.2
  4830.8  991.22  4838.8  983.49  4846.7  979.51  4896.3  966.86  4911.5  965.91
  4919.4  962.75  4927.3  955.94  4999.2  949.63  4999.7  949.13  5020.9  949.63
  5040.1  955.45  5074.1  956.13  5220.8  959.28  5303.6  964.09  5350.1  970.48
    5424  982.53  5481.7  998.33  5539.4 1019.81  5575.3 1028.26  5602.1 1030.58
#Mann= 7 ,-1 , 0
  4596.9    .035       0    4757     .12       0  4999.2     .05       0
  5020.9     .12       0  5074.1    .035       0  5350.1     .12       0
  5575.3    .035       0
Bank Sta=4999.2,5020.9
XS Rating Curve= 0 ,0
Exp/Cntr=0.3,0.1

Type RM Length L Ch R = 1 ,10595   ,570,570,570
BEGIN DESCRIPTION:
Rebecca Creek 18.0
END DESCRIPTION:
XS GIS Cut Line= 3
      2171725.02     13880925.02        2171425.       13880625.
      2170874.98     13880474.99
#Sta/Elev= 30
  4571.1 1024.83    4656 1017.94  4695.6 1009.11  4740.8  992.52  4825.7  965.12
  4868.1  958.82  4889.3  958.53  4898.1  956.91  4938.8  950.97  5018.4  949.49
  5047.2  950.68  5057.6   952.8  5119.8  953.74  5126.7  950.35  5140.5  949.32
  5184.1  949.29  5195.3  949.15  5195.8  948.65    5217  949.15  5245.9  950.26
  5275.2  956.24  5285.6  960.19  5306.3  962.05  5389.3  979.09  5420.4   990.5
  5434.2  993.94  5465.2 1006.97  5492.9 1020.48  5513.6 1027.27  5565.5 1029.11
#Mann= 8 ,-1 , 0
  4571.1    .035       0  4695.6     .12       0  4898.1     .12       0
  5018.4    .035       0  5184.1     .12       0  5195.3     .05       0
    5217     .12       0  5465.2     .12       0
Bank Sta=5195.3,5217
XS Rating Curve= 0 ,0
Exp/Cntr=0.3,0.1

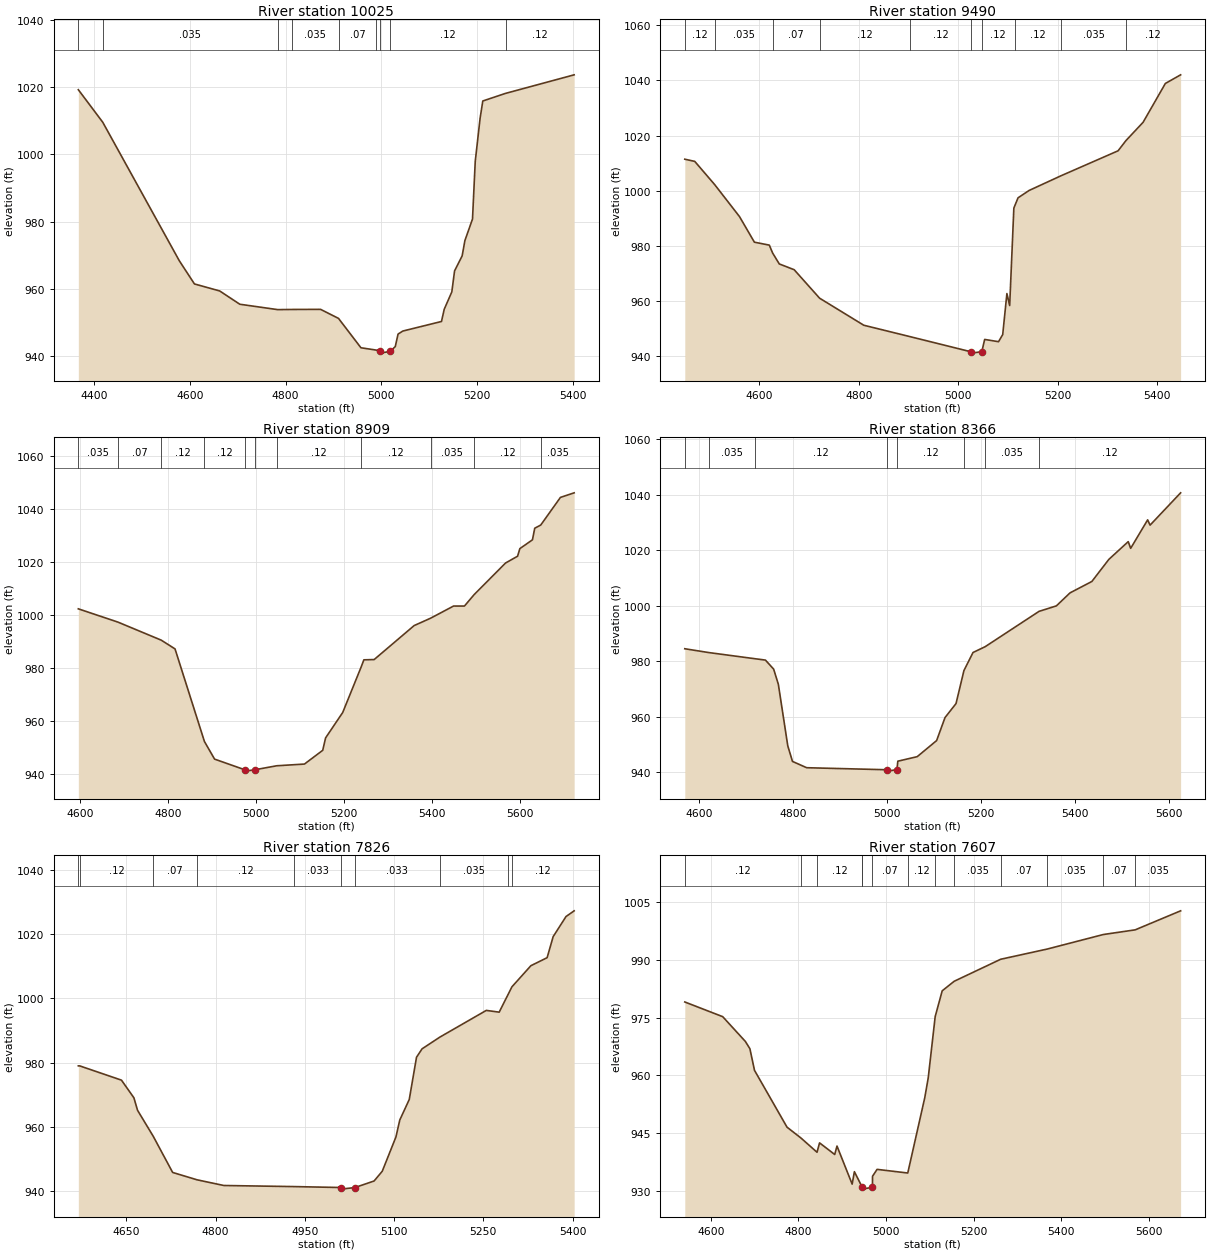
Type RM Length L Ch R = 1 ,10025   ,535,535,535
BEGIN DESCRIPTION:
Rebecca Creek 17.0
END DESCRIPTION:
XS GIS Cut Line= 3
      2171825.01     13880725.04        2171625.       13880125.
      2171275.01       13879925.
#Sta/Elev= 30
    4367  1019.2    4418 1009.54  4577.9   968.4  4609.5  961.51  4662.2  959.43
  4704.3  955.48  4783.4  953.88  4813.6  953.93    4873  953.96  4910.4  951.28
  4957.3  942.55  4989.3  941.86  4996.4  941.46  4996.9  940.96  5018.4  941.46
    5029  942.91  5034.8  946.62  5044.8  947.52  5125.5  950.36  5131.2  953.98
  5147.1  959.15  5152.8  965.37  5168.7  969.86  5174.4  974.39  5190.3  980.79
    5196  997.91  5206.1 1010.66  5211.8 1015.85  5259.3 1018.11  5402.6 1023.62
#Mann= 9 ,-1 , 0
    4367     .12       0    4418    .035       0  4783.4     .12       0
  4813.6    .035       0  4910.4     .07       0  4989.3     .12       0
  4996.4     .05       0  5018.4     .12       0  5259.3     .12       0
Bank Sta=4996.4,5018.4
XS Rating Curve= 0 ,0
Exp/Cntr=0.3,0.1

Type RM Length L Ch R = 1 ,9490    ,581,581,581
BEGIN DESCRIPTION:
Rebecca Creek 16.0
END DESCRIPTION:
XS GIS Cut Line= 3
        2172125.     13880574.99        2172125.       13880025.
        2171925.       13879625.
#Sta/Elev= 30
    4450 1011.46    4470 1010.67    4510 1002.28    4560  990.68    4590   981.4
    4620  980.34  4626.5  977.53    4640  973.53    4670  971.43  4721.1  961.12
    4810  951.32  4903.5  947.17  5025.3  941.72  5025.8  941.22  5047.3  941.72
  5053.1  946.18    5081  945.36  5089.4  947.95  5097.8  962.79  5103.4  958.46
  5111.8  993.76  5113.8  994.64  5120.2  997.47  5142.5 1000.14  5206.7 1005.46
  5321.4  1014.5  5337.2 1018.19  5371.7 1024.82  5416.5 1038.89  5447.2 1042.02
#Mann= 10 ,-1 , 0
    4450     .12       0    4510    .035       0  4626.5     .07       0
  4721.1     .12       0  4903.5     .12       0  5025.3     .05       0
  5047.3     .12       0  5113.8     .12       0  5206.7    .035       0
  5337.2     .12       0
Bank Sta=5025.3,5047.3
XS Rating Curve= 0 ,0
Exp/Cntr=0.3,0.1

Type RM Length L Ch R = 1 ,8909    ,543,543,543
BEGIN DESCRIPTION:
Rebecca Creek 15.0
END DESCRIPTION:
XS GIS Cut Line= 3
        2172675.       13880425.        2172675.       13880025.
        2172475.     13879325.01
#Sta/Elev= 30
  4595.4 1002.35  4685.6  997.32  4783.9  990.51  4815.4  987.19  4882.3  952.16
  4905.4   945.5  4974.4  941.46  4974.9  940.96  4996.5  941.46    5047  942.99
  5109.8  943.63  5151.4  948.83  5157.9  953.52  5196.9  963.15  5238.1  980.05
    5245  983.06  5268.4  983.16  5359.4  996.02  5396.9  998.81  5449.1 1003.41
  5473.8  1003.4    5496 1007.75  5567.4 1019.69  5594.7 1022.25  5599.9 1025.13
  5628.5 1028.45  5633.7 1032.83  5647.4 1034.05  5692.2  1044.5  5723.4 1046.23
#Mann= 11 ,-1 , 0
  4595.4    .035       0  4685.6     .07       0  4783.9     .12       0
  4882.3     .12       0  4974.4     .05       0  4996.5     .12       0
    5047     .12       0  5238.1     .12       0  5396.9    .035       0
    5496     .12       0  5647.4    .035       0
Bank Sta=4974.4,4996.5
XS Rating Curve= 0 ,0
Exp/Cntr=0.3,0.1

Type RM Length L Ch R = 1 ,8366    ,540,540,540
BEGIN DESCRIPTION:
Rebecca Creek 14.0
END DESCRIPTION:
XS GIS Cut Line= 3
       2173166.2     13880203.18        2173125.       13879775.
      2172973.91     13879168.39
#Sta/Elev= 30
  4569.5  984.48  4620.1  983.11  4719.2  980.87  4741.1  980.39  4758.6  977.13
  4768.6  971.68  4788.7  949.46  4798.7  943.85  4828.9  941.58  4998.9  940.85
  4999.4  940.35    5021  940.85  5022.9  943.93  5064.2  945.57  5105.5  951.37
  5123.3  959.65  5146.8  964.72  5163.6   976.6  5182.9  983.12  5208.9  985.23
  5323.5  997.96  5360.4  999.94  5389.4 1004.62  5435.9 1008.74    5472 1016.69
  5513.3  1023.1  5518.5 1020.69  5554.6 1030.95  5559.8 1029.05  5624.8  1040.7
#Mann= 8 ,-1 , 0
  4569.5     .12       0  4620.1    .035       0  4719.2     .12       0
  4998.9     .05       0    5021     .12       0  5163.6     .12       0
  5208.9    .035       0  5323.5     .12       0
Bank Sta=4998.9,5021
XS Rating Curve= 0 ,0
Exp/Cntr=0.3,0.1

Type RM Length L Ch R = 1 ,7826    ,555,555,555
BEGIN DESCRIPTION:
Rebecca Creek 13.0
END DESCRIPTION:
XS GIS Cut Line= 3
      2173724.98     13879974.97        2173475.       13879625.
        2173275.     13879274.99
#Sta/Elev= 30
  4569.4  978.96  4571.7  978.96  4641.9  974.52  4662.8  969.02  4668.9  965.14
  4695.3  957.04  4727.9  945.79  4768.9   943.5  4813.9  941.73  4931.6  941.39
  5010.8   941.1  5011.3   940.6  5034.3   941.1  5066.4  943.13  5080.1  946.16
  5103.1  956.83  5109.6  962.12  5125.5   968.5  5137.7  981.65    5147  984.26
  5176.8   987.9    5255  996.23  5276.6  995.68  5292.1 1001.38    5298 1003.56
  5329.9 1010.14  5357.2 1012.64  5367.3 1019.18  5388.9 1025.44  5402.6 1027.22
#Mann= 10 ,-1 , 0
  4569.4    .035       0  4571.7     .12       0  4695.3     .07       0
  4768.9     .12       0  4931.6    .033       0  5010.8    .033       0
  5034.3    .033       0  5176.8    .035       0  5292.1     .07       0
    5298     .12       0
Bank Sta=5010.8,5034.3
XS Rating Curve= 0 ,0
Exp/Cntr=0.3,0.1

Type RM Length L Ch R = 1 ,7607    ,336,336,336
BEGIN DESCRIPTION:
Rebecca Creek 12.5
END DESCRIPTION:
XS GIS Cut Line= 3
      2173780.38     13879968.48      2173659.66     13879525.23
      2173427.27     13878894.37
#Sta/Elev= 30
  4540.6  979.05  4627.1  975.23  4678.9  968.78  4689.2  966.89  4699.7  961.27
  4773.9  946.49  4806.2  943.62  4842.4  939.96  4848.2   942.4  4882.8  939.38
    4888  941.57  4922.6  931.67  4927.7  934.91  4945.2  930.94  4945.4  930.87
  4945.9  930.37  4968.9  930.87  4969.1  933.72  4979.5  935.51  5049.5  934.56
  5088.3  954.14  5096.2  959.29  5112.1  975.25  5128.1  981.95  5155.5  984.44
  5261.6  990.16  5367.6  992.81    5496   996.6  5568.6  997.81  5672.3 1002.76
#Mann= 13 ,-1 , 0
  4540.6     .12       0  4806.2     .07       0  4842.4     .12       0
  4945.2     .07       0  4945.4     .05       0  4968.9     .07       0
  5049.5     .12       0  5112.1     .07       0  5155.5    .035       0
  5261.6     .07       0  5367.6    .035       0    5496     .07       0
  5568.6    .035       0
Bank Sta=4945.4,4968.9
XS Rating Curve= 0 ,0
Exp/Cntr=0.3,0.1

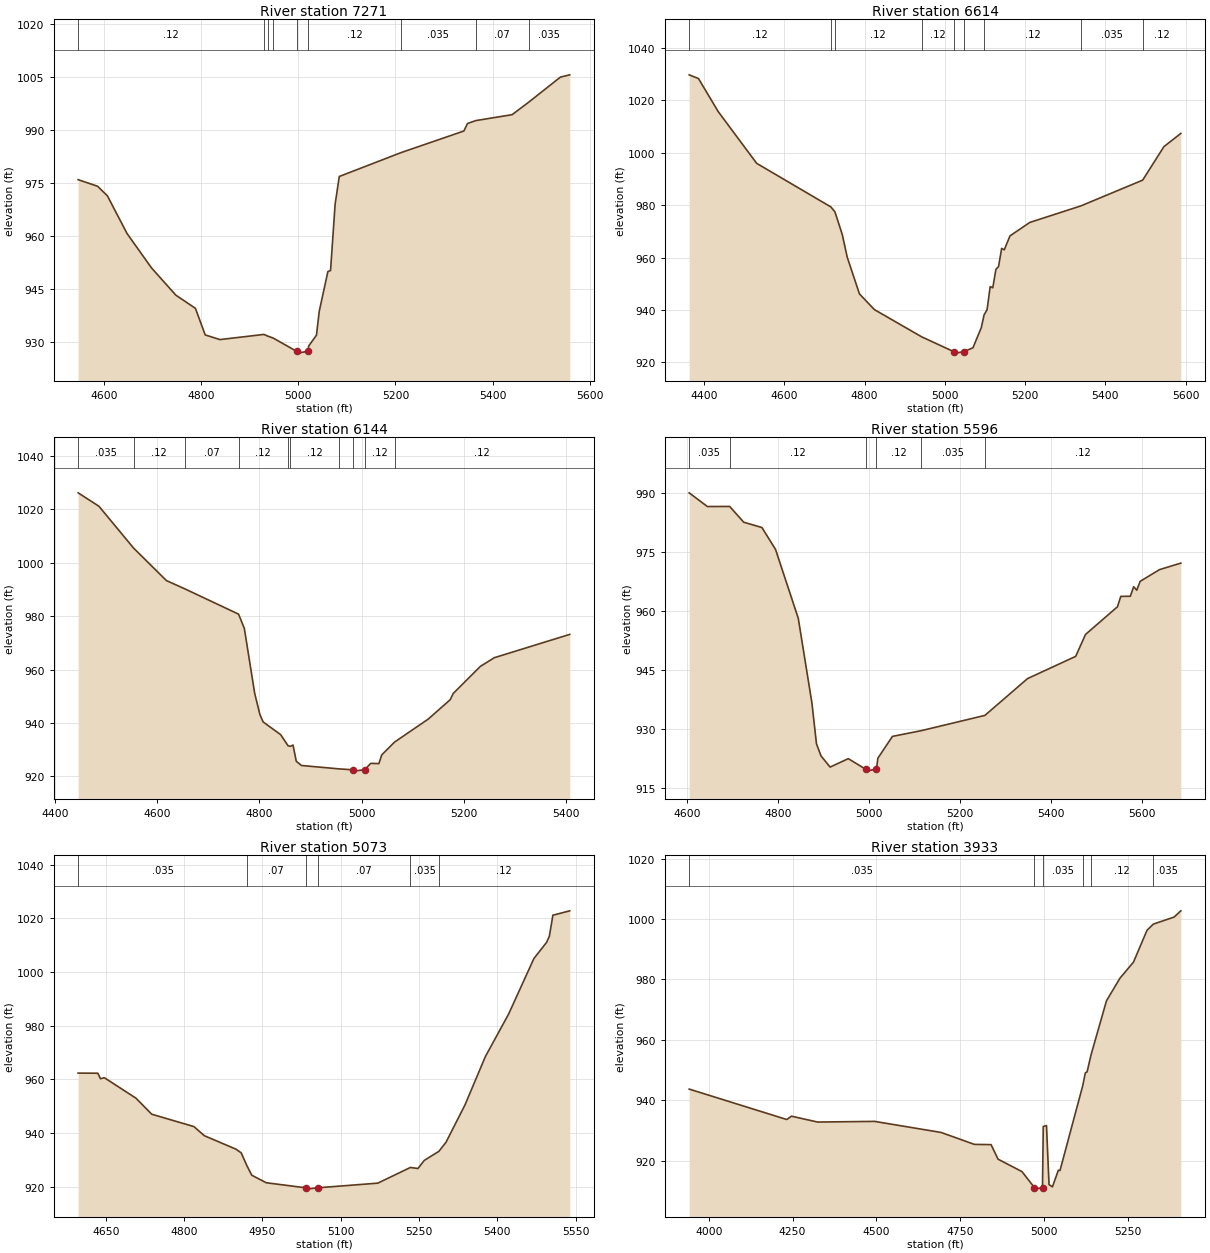
Type RM Length L Ch R = 1 ,7271    ,657,657,657
BEGIN DESCRIPTION:
Rebecca Creek 12.0
END DESCRIPTION:
XS GIS Cut Line= 3
      2173875.01     13879874.95        2173925.       13879425.
      2173702.46     13878911.91
#Sta/Elev= 30
  4546.8  975.99    4587  974.11  4607.1   971.4  4647.4  960.75  4697.7  951.01
    4748  943.26  4788.2  939.54  4808.4     932  4838.5  930.68  4929.4  932.14
    4937  931.67  4948.6  931.09  4996.7  927.34  4997.2  926.84  5020.3  927.34
  5021.3  928.84  5037.4  931.93  5043.1  938.68  5060.9  949.94  5066.4  950.25
  5075.8  969.05  5084.4  976.89  5211.3  983.64  5340.8  989.77  5348.3   991.9
  5365.3  992.72  5440.1   994.4    5474  997.91  5539.5 1005.04  5558.8 1005.69
#Mann= 9 ,-1 , 0
  4546.8     .12       0  4929.4     .12       0    4937     .12       0
  4948.6     .12       0  4996.7     .05       0  5020.3     .12       0
  5211.3    .035       0  5365.3     .07       0    5474    .035       0
Bank Sta=4996.7,5020.3
XS Rating Curve= 0 ,0
Exp/Cntr=0.3,0.1

Type RM Length L Ch R = 1 ,6614    ,470,470,470
BEGIN DESCRIPTION:
Rebecca Creek 11.0
END DESCRIPTION:
XS GIS Cut Line= 3
        2174875.       13879975.       2174547.5     13879415.09
      2174175.02     13878975.02
#Sta/Elev= 30
  4363.1 1029.73  4386.3 1028.31  4435.4  1015.7  4531.3  995.94  4716.3   979.3
  4726.3  977.43  4744.5  968.83    4757   960.1  4787.4  946.11  4824.6  940.12
  4942.1  929.75  5023.4     924  5023.9   923.5    5047     924  5070.3  925.55
  5091.2  933.28  5097.9  938.06  5105.4  940.06  5113.2  948.88  5119.7  948.45
  5127.5  955.49    5134  956.52  5141.8  963.49  5148.3  962.94  5162.6  968.26
    5212  973.39  5339.1  979.69  5493.2  989.53  5546.1 1002.31  5588.3 1007.37
#Mann= 9 ,-1 , 0
  4363.1     .12       0  4716.3    .035       0  4726.3     .12       0
  4942.1     .12       0  5023.4     .05       0    5047     .12       0
  5097.9     .12       0  5339.1    .035       0  5493.2     .12       0
Bank Sta=5023.4,5047
XS Rating Curve= 0 ,0
Exp/Cntr=0.3,0.1

Type RM Length L Ch R = 1 ,6144    ,548,548,548
BEGIN DESCRIPTION:
Rebecca Creek 10.0
END DESCRIPTION:
XS GIS Cut Line= 3
      2175075.01     13879825.03        2174975.       13879275.
      2174624.97     13879074.98
#Sta/Elev= 30
  4445.2  1026.1  4485.9 1021.09  4553.7 1005.44    4618  993.27  4654.3  990.15
  4759.2  980.71  4770.5  975.38  4790.8  951.03    4801  943.14  4807.3  940.38
  4841.6  935.62  4856.1  931.47  4860.6  931.26  4865.8  931.73  4872.1  925.68
  4882.3  924.09  4955.9  922.82  4982.3  922.48  4982.8  921.98  5005.9  922.48
  5017.9  924.89  5033.8  924.79  5039.5  928.06  5064.5  932.85  5130.2  941.42
  5173.4   948.7  5179.2  951.01  5232.4  961.16  5259.8  964.42  5407.4  973.14
#Mann= 10 ,-1 , 0
  4445.2    .035       0  4553.7     .12       0  4654.3     .07       0
  4759.2     .12       0  4856.1     .12       0  4860.6     .12       0
  4955.9     .12       0  4982.3     .05       0  5005.9     .12       0
  5064.5     .12       0
Bank Sta=4982.3,5005.9
XS Rating Curve= 0 ,0
Exp/Cntr=0.3,0.1

Type RM Length L Ch R = 1 ,5596    ,523,523,523
BEGIN DESCRIPTION:
Rebecca Creek 9.0
END DESCRIPTION:
XS GIS Cut Line= 3
        2175425.     13879425.05        2175425.     13879009.81
      2174971.98     13878521.26
#Sta/Elev= 30
  4604.3  990.17  4644.3  986.68  4693.4   986.7  4724.3  982.68  4764.3  981.33
  4794.3  975.74  4844.3  958.19  4874.3  936.62  4884.3  926.24  4894.3  923.14
  4914.3  920.29  4954.3  922.44  4992.4  919.76  4992.9  919.26  5016.2  919.76
  5019.4  922.56  5051.4  928.11  5114.1  929.55  5254.8  933.46  5348.5  942.83
  5454.5   948.5  5476.1  954.08  5546.4  961.14  5553.7  963.78  5574.7  963.82
  5582.1  966.25  5588.9  965.36  5596.3  967.61  5638.8   970.6  5685.8  972.26
#Mann= 6 ,-1 , 0
  4604.3    .035       0  4693.4     .12       0  4992.4     .05       0
  5016.2     .12       0  5114.1    .035       0  5254.8     .12       0
Bank Sta=4992.4,5016.2
XS Rating Curve= 0 ,0
Exp/Cntr=0.3,0.1

Type RM Length L Ch R = 1 ,5073    ,1140,1140,1140
BEGIN DESCRIPTION:
Rebecca Creek 8.0
END DESCRIPTION:
XS GIS Cut Line= 3
      2175775.01     13879174.95        2175825.       13878775.
      2175624.99     13878274.98
#Sta/Elev= 30
    4597  962.36  4634.7  962.32  4639.8  960.27  4647.3  960.64  4707.8  953.02
    4738  947.04  4818.7  942.44  4838.8  939.03  4899.3  934.02  4909.4  932.63
  4920.2  927.88  4929.5  924.33  4957.2  921.51  5032.6  919.63  5033.1  919.13
  5056.4  919.63    5171  921.36  5233.3   927.2  5247.8  926.81  5259.9  929.83
  5287.9   933.2  5301.6  936.61    5338  950.54    5377  968.54  5421.5  984.37
  5469.9 1005.05  5494.2 1011.08  5499.5 1013.36  5506.3  1021.2  5538.6 1022.83
#Mann= 6 ,-1 , 0
    4597    .035       0  4920.2     .07       0  5032.6     .05       0
  5056.4     .07       0  5233.3    .035       0  5287.9     .12       0
Bank Sta=5032.6,5056.4
XS Rating Curve= 0 ,0
Exp/Cntr=0.3,0.1

Type RM Length L Ch R = 1 ,3933    ,540,540,540
BEGIN DESCRIPTION:
Rebecca Creek 7.0
END DESCRIPTION:
XS GIS Cut Line= 3
      2175925.01     13879074.99        2176725.       13878375.
        2176675.     13877975.01
#Sta/Elev= 30
  3941.7  943.72  4232.6  933.65  4246.8  934.75  4324.7  932.81  4494.5  933.03
  4692.9  929.37  4792.1  925.42  4841.9  925.34  4862.8  920.52    4934  916.42
  4971.4  911.11  4971.9  910.61  4995.3  911.11  4997.6  931.34  5007.2  931.67
  5014.8  912.11  5024.9  911.36  5042.5  916.85  5047.5  916.78  5115.4   944.9
  5123.1  949.12  5128.2  949.38  5139.9  954.99  5186.1  972.94  5226.4  980.44
  5266.7  985.76    5307   996.3    5326  998.33  5387.7 1000.65  5407.8 1002.72
#Mann= 6 ,-1 , 0
  3941.7    .035       0  4971.4     .05       0  4995.3    .035       0
  5115.4     .07       0  5139.9     .12       0    5326    .035       0
Bank Sta=4971.4,4995.3
XS Rating Curve= 0 ,0
Exp/Cntr=0.3,0.1