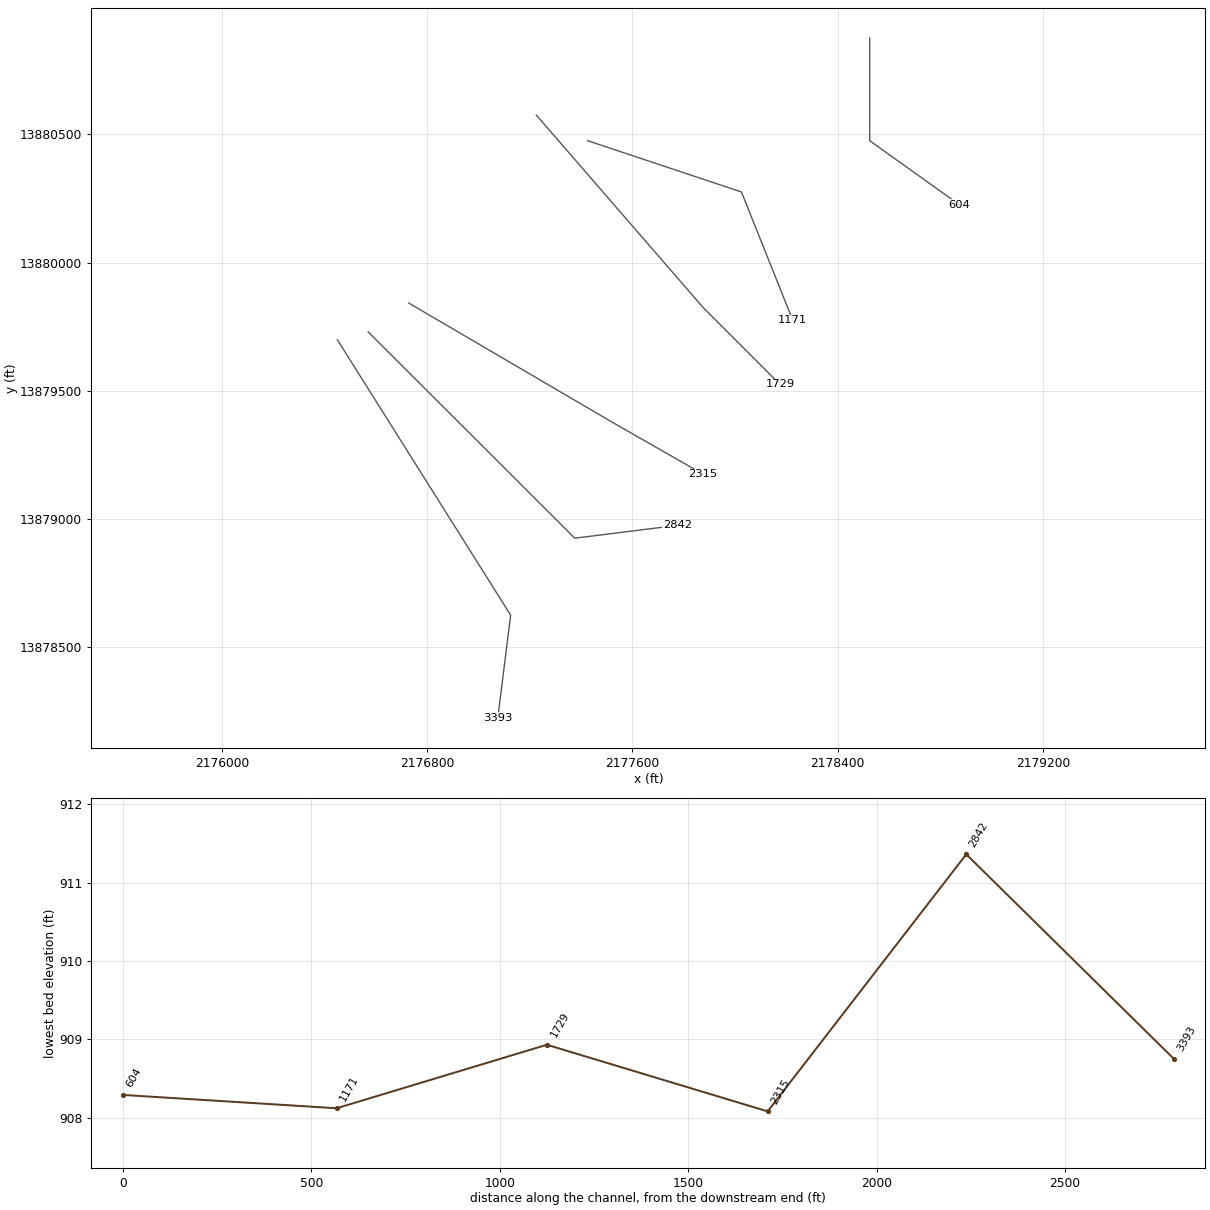
HEC-RAS study Rebecca Creek.prj: Rebecca Creek Base Level Engineering

--- Rebecca Creek.g01 (geometry) --- (continued)

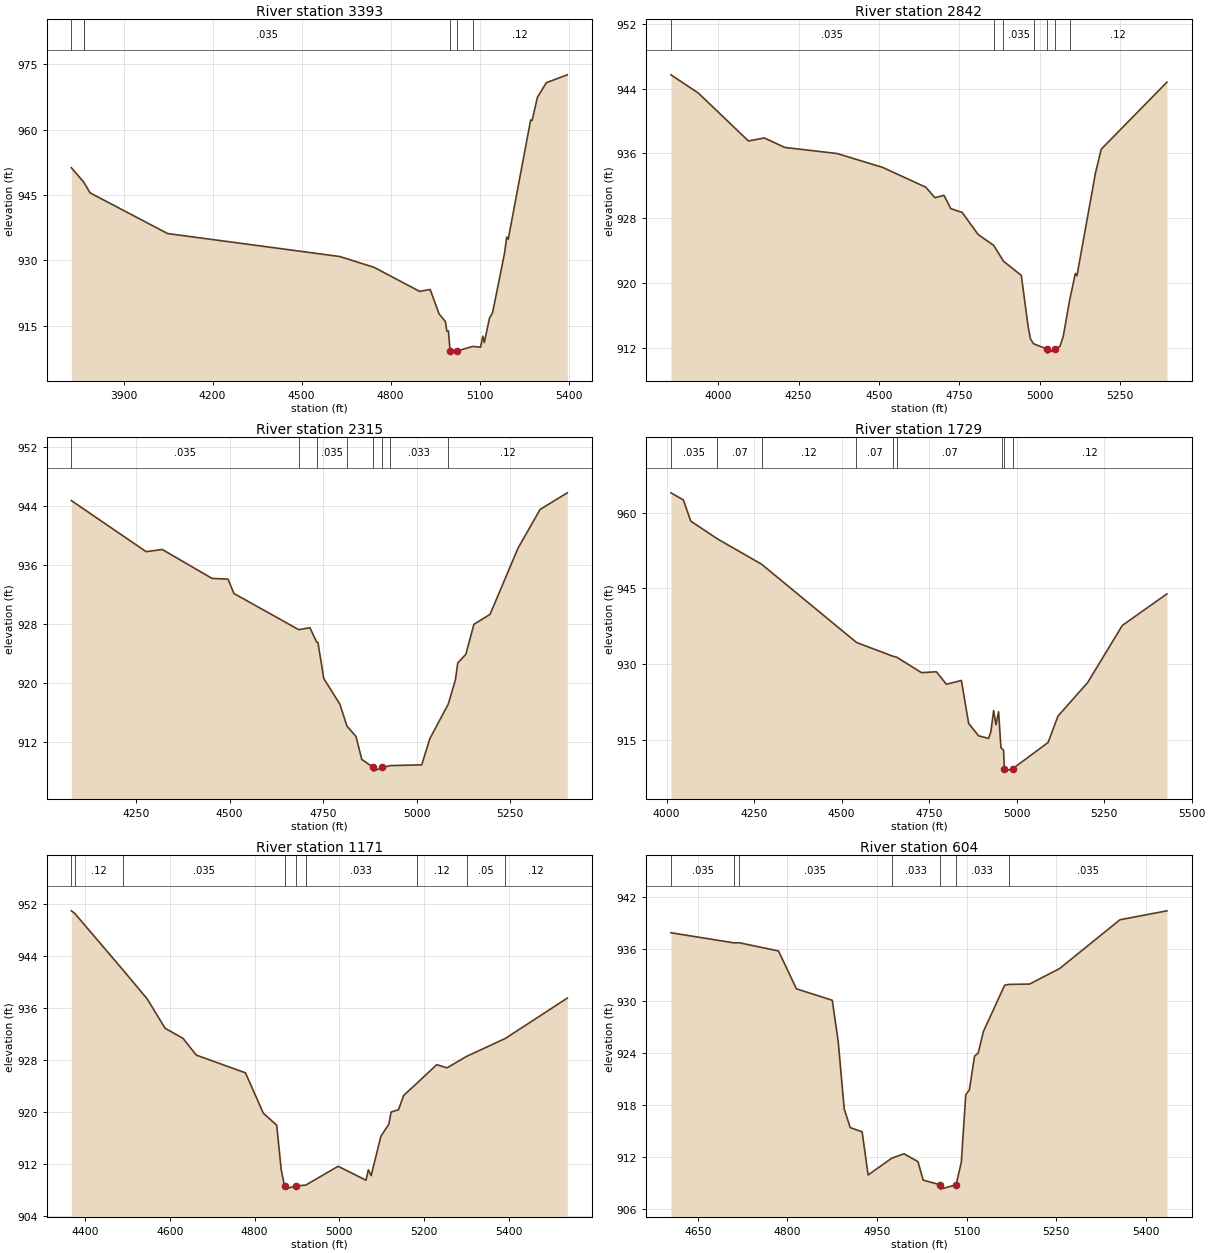
Type RM Length L Ch R = 1 ,3393    ,551,551,551
BEGIN DESCRIPTION:
Rebecca Creek 6.0
END DESCRIPTION:
XS GIS Cut Line= 3
      2176449.44     13879698.46        2177125.       13878625.
        2177075.     13878224.96
#Sta/Elev= 30
  3723.9  951.25  3765.2  947.99  3766.1   947.9  3787.1  945.49  4048.5  936.16
    4629  930.89  4744.4  928.41  4897.7  922.91  4933.2  923.34  4963.4  917.73
  4984.6     916  4989.3  913.82  4994.8  913.82  5000.3  909.25  5000.8  908.75
  5024.5  909.25  5076.2  910.28  5103.1  910.12  5110.7  912.64  5115.7  911.17
  5133.3  916.81  5143.4  917.97  5183.7  931.59  5191.3  935.37  5196.3  934.85
  5271.9  962.19  5276.9  962.09  5294.6  967.39  5324.8  970.75  5395.4  972.55
#Mann= 6 ,-1 , 0
  3723.9     .12       0  3765.2     .07       0  3766.1    .035       0
  5000.3    .035       0  5024.5    .035       0  5076.2     .12       0
Bank Sta=5000.3,5024.5
XS Rating Curve= 0 ,0
Exp/Cntr=0.3,0.1

Type RM Length L Ch R = 1 ,2842    ,527,527,527
BEGIN DESCRIPTION:
Rebecca Creek 5.0
END DESCRIPTION:
XS GIS Cut Line= 3
       2176569.2     13879729.76        2177375.       13878925.
      2177775.05     13878975.01
#Sta/Elev= 30
  3853.4   945.7  3938.6  943.45  4094.2  937.54  4143.7  937.91  4207.3  936.74
    4370  935.99  4511.4  934.28  4645.8  931.83    4674  930.54  4702.3  930.83
  4723.5  929.19  4758.9  928.72  4808.4     926    4857  924.65  4887.3   922.7
  4942.7  920.95    4964  914.61    4971  913.14  4980.6  912.52    5023  911.86
  5023.5  911.36  5047.2  911.86  5062.8  912.19  5072.9  913.39  5093.1  917.92
  5110.7  921.18  5115.7  920.91  5173.6  933.65  5191.3  936.53  5395.4  944.79
#Mann= 7 ,-1 , 0
  3853.4    .035       0    4857     .07       0  4887.3    .035       0
  4980.6    .033       0    5023    .033       0  5047.2    .033       0
  5093.1     .12       0
Bank Sta=5023,5047.2
XS Rating Curve= 0 ,0
Exp/Cntr=0.3,0.1

Type RM Length L Ch R = 1 ,2315    ,586,586,586
BEGIN DESCRIPTION:
Rebecca Creek 4.0
END DESCRIPTION:
XS GIS Cut Line= 3
       2176728.1     13879841.71        2177525.       13879375.
      2177874.98     13879175.01
#Sta/Elev= 30
  4076.6  944.77  4276.8  937.84  4319.8  938.14  4452.8  934.22  4495.8  934.11
  4511.5  932.17    4685  927.26  4714.7  927.53  4732.8  925.58  4736.2  925.54
  4751.9  920.63  4794.8  917.17  4813.9  914.18  4837.9  912.79  4853.5  909.67
  4884.3  908.58  4884.8  908.08  4908.6  908.58  4930.1  908.83  5013.8  908.93
  5035.4  912.47  5084.7  917.16  5103.8  920.42  5110.2  922.75  5131.8  923.92
  5153.4  927.99  5196.6  929.34  5271.5  938.33  5330.5  943.57  5403.2  945.82
#Mann= 8 ,-1 , 0
  4076.6    .035       0    4685     .07       0  4732.8    .035       0
  4813.9     .07       0  4884.3    .033       0  4908.6     .07       0
  4930.1    .033       0  5084.7     .12       0
Bank Sta=4884.3,4908.6
XS Rating Curve= 0 ,0
Exp/Cntr=0.3,0.1

Type RM Length L Ch R = 1 ,1729    ,558,558,558
BEGIN DESCRIPTION:
Rebecca Creek 3.0
END DESCRIPTION:
XS GIS Cut Line= 3
      2177225.02     13880574.98        2177875.       13879825.
        2178175.       13879525.
#Sta/Elev= 30
  4012.6  963.89  4048.2  962.48  4069.1  958.31  4144.8  954.82  4271.6  949.79
  4542.6  934.34  4646.6  931.62  4657.1  931.45  4728.2  928.38  4770.9  928.55
  4799.4  926.08  4842.2  926.84    4863  918.35  4891.5  915.89    4920   915.4
  4926.7   916.8  4934.3  920.91  4940.9  918.09  4948.5  920.67  4955.2  913.54
  4959.5  913.26  4962.8  913.05  4964.9  909.43  4965.4  908.93  4989.3  909.43
  5089.9  914.59  5118.2  919.81    5203  926.43    5302  937.71  5429.3  943.93
#Mann= 9 ,-1 , 0
  4012.6    .035       0  4144.8     .07       0  4271.6     .12       0
  4542.6     .07       0  4646.6    .035       0  4657.1     .07       0
  4959.5     .12       0  4964.9     .05       0  4989.3     .12       0
Bank Sta=4964.9,4989.3
XS Rating Curve= 0 ,0
Exp/Cntr=0.3,0.1

Type RM Length L Ch R = 1 ,1171    ,567,567,567
BEGIN DESCRIPTION:
Rebecca Creek 2.0
END DESCRIPTION:
XS GIS Cut Line= 3
      2177424.96     13880475.01        2178025.       13880275.
      2178224.99     13879775.02
#Sta/Elev= 30
  4367.5  950.97  4375.4  950.59  4490.2  941.81  4546.7   937.4  4588.9  932.89
  4631.1  931.34  4662.7  928.75  4778.6  926.03  4820.8  919.81  4852.4  917.96
    4863  911.12  4870.8  908.62  4871.3  908.12  4897.3  908.62  4920.7  908.73
  4997.4  911.64  5063.3  909.49  5068.7  911.09  5075.4   910.2  5098.3  916.25
  5117.1  918.11  5122.5  919.99    5140  920.35  5152.1  922.55  5182.9  924.39
  5230.2  927.29  5254.4  926.79  5300.8  928.56  5392.2  931.32  5538.5  937.53
#Mann= 9 ,-1 , 0
  4367.5     .07       0  4375.4     .12       0  4490.2    .035       0
  4870.8    .033       0  4897.3    .035       0  4920.7    .033       0
  5182.9     .12       0  5300.8     .05       0  5392.2     .12       0
Bank Sta=4870.8,4897.3
XS Rating Curve= 0 ,0
Exp/Cntr=0.3,0.1

Type RM Length L Ch R = 1 ,604     ,0,0,0
BEGIN DESCRIPTION:
Rebecca Creek 1.0
END DESCRIPTION:
XS GIS Cut Line= 3
        2178525.       13880875.        2178525.       13880475.
      2178874.98     13880225.01
#Sta/Elev= 30
    4605  937.87  4710.9   936.7    4719  936.72    4785  935.77    4815   931.4
    4875  930.08    4885  925.28    4895  917.55    4905  915.39    4925   914.9
    4935  909.92  4974.3  911.85    4995  912.37  5018.5  911.46  5027.1  909.33
  5055.7  908.79  5056.2  908.29  5082.2  908.79    5091   911.4  5098.4  919.19
  5104.5  919.75  5113.1  923.63  5119.3  923.99  5127.9  926.47  5163.5  931.81
  5170.1  931.91  5205.3  931.95  5255.7  933.75  5356.5  939.37  5435.1   940.4
#Mann= 7 ,-1 , 0
    4605    .035       0  4710.9     .07       0    4719    .035       0
  4974.3    .033       0  5055.7    .033       0  5082.2    .033       0
  5170.1    .035       0
Bank Sta=5055.7,5082.2
XS Rating Curve= 0 ,0
Exp/Cntr=0.3,0.1

Chan Stop Cuts=-1
Use User Specified Reach Order=0
Composite Channel Slope=5