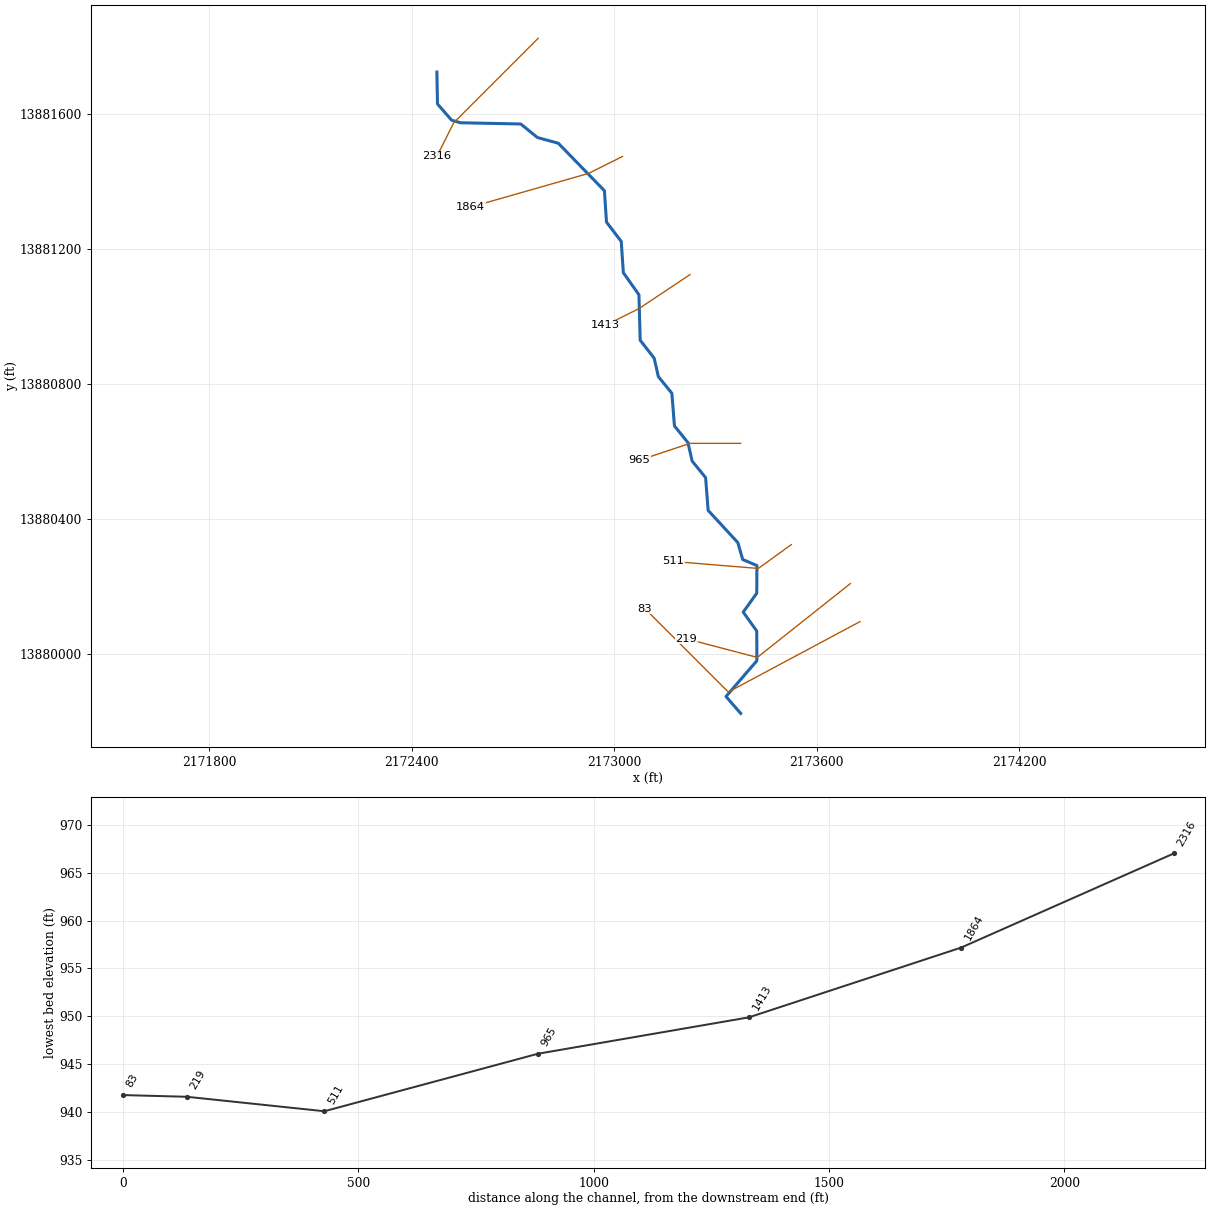
--- Rebecca Tributary 2.prj (project) ---

Proj Title=Rebecca Tributary 2 Base Level Engineering
Current Plan=p01
Default Exp/Contr=0.3,0.1
English Units
Geom File=g01
Flow File=f01
Plan File=p01
BEGIN DESCRIPTION:
Rebecca Tributary 2
END DESCRIPTION:

--- Rebecca Tributary 2.p01 (plan) ---

Plan Title=Multiple Run
Short Identifier=Multiple
Geom File=g01
Flow File=f01
Subcritical Flow
K Sum by GR= 0
Std Step Tol= 0.01
Critical Tol= 0.01
Num of Std Step Trials= 20
Max Error Tol= 0.3
Flow Tol Ratio= 0.001
Split Flow NTrial= 30
Split Flow Tol= 0.02
Split Flow Ratio= 0.02
Log Output Level= 0
Friction Slope Method= 1
Unsteady Friction Slope Method= 2
Unsteady Bridges Friction Slope Method= 1
Parabolic Critical Depth
Global Vel Dist=  1 , 1 , 1
Global Log Level= 0
CheckData=True
Encroach Param= -1, 0, 0, 0
BEGIN DESCRIPTION:
Multiple Run
END DESCRIPTION:

--- Rebecca Tributary 2.f01 (steady flow) ---

Flow Title=Multiple
Number of Profiles=7
Profile Names=10-year,25-year,50-year,1pct_min,100-year,1pct_plu,500-year
River Rch & RM= Rebecca Tributar,Reach-1,2316
    1221    2094    2933    1990    3971    7923    7206
Boundary for River Rch & Prof#=Rebecca Tributar,Reach-1,1
Up Type=0
Dn Type=3
Dn Slope=0.005
Boundary for River Rch & Prof#=Rebecca Tributar,Reach-1,2
Up Type=0
Dn Type=3
Dn Slope=0.005
Boundary for River Rch & Prof#=Rebecca Tributar,Reach-1,3
Up Type=0
Dn Type=3
Dn Slope=0.005
Boundary for River Rch & Prof#=Rebecca Tributar,Reach-1,4
Up Type=0
Dn Type=3
Dn Slope=0.005
Boundary for River Rch & Prof#=Rebecca Tributar,Reach-1,5
Up Type=0
Dn Type=3
Dn Slope=0.005
Boundary for River Rch & Prof#=Rebecca Tributar,Reach-1,6
Up Type=0
Dn Type=3
Dn Slope=0.005
Boundary for River Rch & Prof#=Rebecca Tributar,Reach-1,7
Up Type=0
Dn Type=3
Dn Slope=0.005

--- Rebecca Tributary 2.g01 (geometry) ---

Geom Title=Existing Conditions

River Reach=Rebecca Tributar,Reach-1
Reach XY= 30
      2172475.00     13881725.00      2172476.76     13881630.52
      2172518.48     13881582.65      2172544.87     13881574.91
      2172723.45     13881571.25      2172772.83     13881531.14
      2172834.68     13881514.24      2172971.39     13881373.50
      2172977.47     13881280.57      2173021.15     13881223.40
      2173027.47     13881130.57      2173073.61     13881065.33
      2173077.36     13880930.52      2173118.88     13880877.18
      2173131.11     13880822.82      2173171.17     13880773.42
      2173178.83     13880676.58      2173218.89     13880627.18
      2173231.11     13880572.82      2173271.17     13880523.41
      2173278.62     13880426.50      2173366.75     13880330.77
      2173381.07     13880280.80      2173423.19     13880263.00
      2173422.67     13880180.98      2173382.57     13880125.00
      2173422.64     13880069.10      2173423.02     13879980.89
      2173331.59     13879874.99      2173375.00     13879825.00

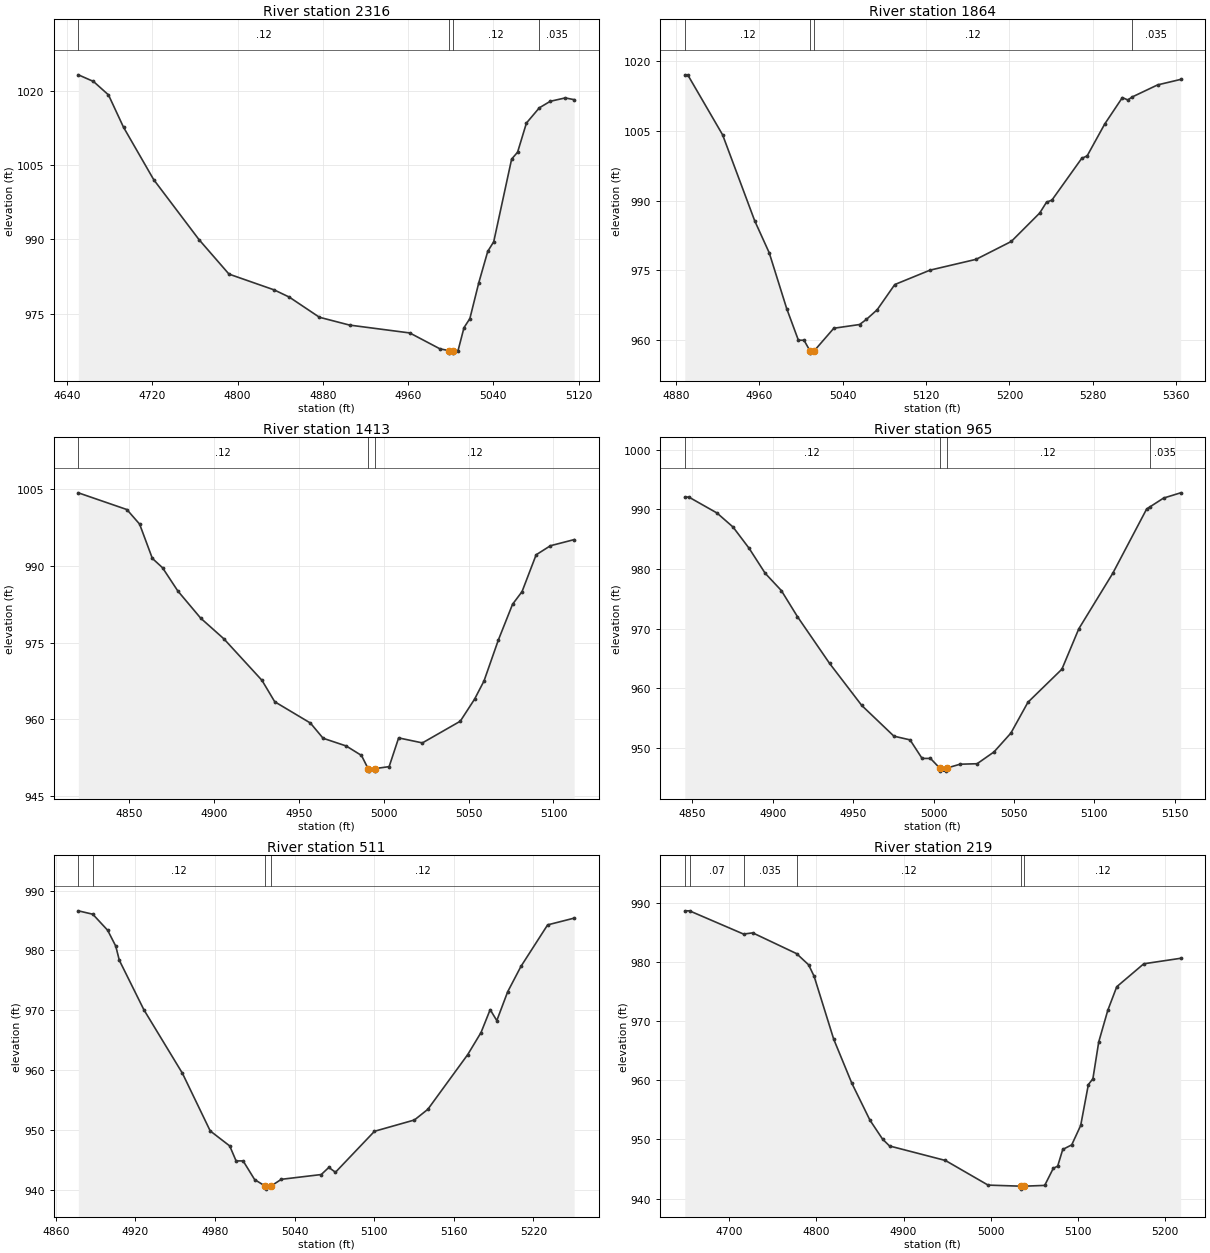
Type RM Length L Ch R = 1,2316,452,452,452
BEGIN DESCRIPTION:
Rebecca Tributary 2 5.0
END DESCRIPTION:
XS GIS Cut Line= 3
      2172775.01     13881825.01      2172525.00     13881575.00
      2172474.99     13881474.97
#Sta/Elev= 30
  4650.5 1023.29  4664.7 1021.95  4678.8 1019.23  4692.9 1012.70  4721.2 1002.11
  4763.7  989.99  4791.9  983.00  4834.4  979.80  4848.5  978.35  4876.8  974.27
  4905.1  972.69  4961.6  971.10  4989.9  967.89  4998.5  967.52  4998.8  967.02
  5002.3  967.02  5002.5  967.52  5006.9  967.52  5012.5  972.17  5018.0  974.00
  5026.4  981.27  5034.8  987.60  5040.4  989.54  5057.2 1006.25  5062.8 1007.65
  5071.1 1013.54  5083.2 1016.62  5093.5 1017.94  5107.5 1018.62  5115.9 1018.27
#Mann=4,-1,0
  4650.5    0.12       0  4998.5    0.05       0  5002.5    0.12       0
  5083.2   0.035       0
Bank Sta=4998.5,5002.5
Exp/Cntr=0.3,0.1

Type RM Length L Ch R = 1,1864,451,451,451
BEGIN DESCRIPTION:
Rebecca Tributary 2 4.0
END DESCRIPTION:
XS GIS Cut Line= 3
      2173024.98     13881474.99      2172925.00     13881425.00
      2172574.98     13881325.00
#Sta/Elev= 30
  4888.5 1017.12  4891.3 1017.12  4924.8 1004.19  4955.6  985.67  4969.5  978.80
  4986.3  966.76  4997.5  959.96  5002.9  959.96  5008.6  957.68  5008.9  957.18
  5012.7  957.68  5031.5  962.54  5056.2  963.34  5062.7  964.43  5073.1  966.52
  5090.0  971.95  5123.8  975.05  5168.0  977.38  5201.8  981.23  5229.1  987.36
  5235.6  989.68  5240.8  990.14  5269.4  999.13  5274.6  999.66  5291.5 1006.54
  5308.4 1012.22  5313.6 1011.71  5317.8 1012.35  5342.2 1014.95  5364.3 1016.13
#Mann=4,-1,0
  4888.5    0.12       0  5008.6    0.05       0  5012.7    0.12       0
  5317.8   0.035       0
Bank Sta=5008.6,5012.7
Exp/Cntr=0.3,0.1

Type RM Length L Ch R = 1,1413,448,448,448
BEGIN DESCRIPTION:
Rebecca Tributary 2 3.0
END DESCRIPTION:
XS GIS Cut Line= 3
      2173225.02     13881125.01      2173075.00     13881025.00
      2172975.00     13880975.00
#Sta/Elev= 30
  4820.1 1004.32  4848.7 1001.05  4856.2  998.20  4863.7  991.50  4869.7  989.67
  4878.7  985.13  4892.2  979.80  4905.8  975.78  4928.3  967.64  4935.8  963.46
  4956.8  959.30  4964.3  956.32  4977.9  954.81  4986.9  952.96  4990.8  950.39
  4991.1  949.89  4994.7  949.89  4995.0  950.39  5003.2  950.77  5008.8  956.39
  5022.8  955.41  5045.1  959.65  5053.5  963.95  5059.1  967.53  5067.5  975.50
  5075.9  982.52  5081.5  985.00  5089.8  992.20  5098.2  993.97  5112.2  995.17
#Mann=3,-1,0
  4820.1    0.12       0  4990.8    0.05       0  4995.0    0.12       0
Bank Sta=4990.8,4995
Exp/Cntr=0.3,0.1

Type RM Length L Ch R = 1,965,454,454,454
BEGIN DESCRIPTION:
Rebecca Tributary 2 2.0
END DESCRIPTION:
XS GIS Cut Line= 3
      2173375.04     13880625.00      2173225.00     13880625.00
      2173074.95     13880574.98
#Sta/Elev= 30
  4845.4  992.04  4847.9  992.04  4865.4  989.37  4875.4  987.01  4885.4  983.44
  4895.4  979.25  4905.4  976.37  4915.4  972.00  4935.4  964.15  4955.4  957.10
  4975.4  951.95  4985.4  951.33  4992.9  948.22  4998.1  948.22  5003.9  946.59
  5004.2  946.09  5007.8  946.09  5008.1  946.59  5016.5  947.25  5027.1  947.33
  5037.6  949.31  5048.1  952.47  5058.7  957.64  5079.8  963.18  5090.3  969.95
  5111.4  979.25  5132.5  990.05  5134.6  990.41  5143.0  991.87  5153.6  992.75
#Mann=4,-1,0
  4845.4    0.12       0  5003.9    0.05       0  5008.1    0.12       0
  5134.6   0.035       0
Bank Sta=5003.9,5008.1
Exp/Cntr=0.3,0.1

Type RM Length L Ch R = 1,511,292,292,292
BEGIN DESCRIPTION:
Rebecca Tributary 2 1.0
END DESCRIPTION:
XS GIS Cut Line= 3
      2173525.02     13880325.01      2173427.44     13880254.39
      2173175.03     13880275.00
#Sta/Elev= 30
  4877.0  986.61  4887.9  986.04  4899.1  983.36  4905.2  980.71  4907.9  978.34
  4926.4  970.07  4955.5  959.43  4976.4  949.81  4991.1  947.30  4995.9  944.80
  5001.2  944.80  5009.9  941.67  5017.9  940.58  5018.1  940.08  5022.1  940.58
  5030.0  941.72  5060.1  942.52  5065.8  943.71  5070.8  942.90  5100.2  949.75
  5130.3  951.64  5140.4  953.42  5170.5  962.58  5180.5  966.26  5187.4  970.09
  5192.4  968.26  5200.6  973.08  5210.6  977.32  5230.7  984.26  5250.7  985.39
#Mann=4,-1,0
  4877.0    0.07       0  4887.9    0.12       0  5017.9    0.05       0
  5022.1    0.12       0
Bank Sta=5017.9,5022.1
Exp/Cntr=0.3,0.1

Type RM Length L Ch R = 1,219,136,136,136
BEGIN DESCRIPTION:
Rebecca Tributary 2 0.1
END DESCRIPTION:
XS GIS Cut Line= 3
      2173699.87     13880209.41      2173424.32     13879990.77
      2173214.10     13880045.98
#Sta/Elev= 30
  4648.9  988.67  4654.3  988.67  4716.3  984.74  4726.9  984.94  4777.2  981.43
  4791.0  979.54  4797.3  977.61  4819.8  966.96  4840.6  959.51  4861.4  953.26
  4875.9  950.05  4883.9  948.89  4948.0  946.44  4997.0  942.27  5034.5  942.09
  5034.7  941.59  5038.7  942.09  5062.0  942.22  5071.8  945.10  5076.9  945.49
  5082.7  948.30  5093.0  949.08  5103.3  952.36  5112.1  959.28  5117.3  960.25
  5124.0  966.49  5134.4  971.84  5144.7  975.83  5175.7  979.71  5218.0  980.64
#Mann=6,-1,0
  4648.9   0.035       0  4654.3    0.07       0  4716.3   0.035       0
  4777.2    0.12       0  5034.5    0.05       0  5038.7    0.12       0
Bank Sta=5034.5,5038.7
Exp/Cntr=0.3,0.1

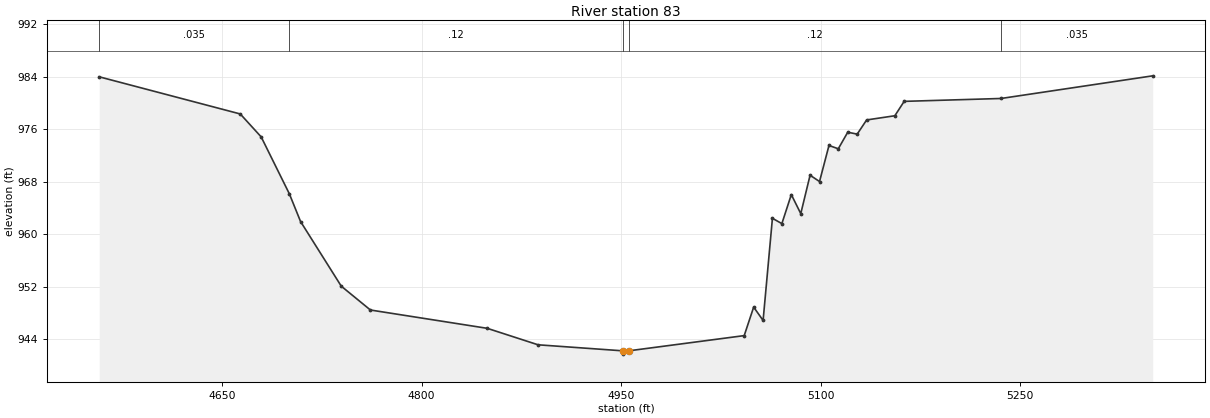
Type RM Length L Ch R = 1,83,0,0,0
BEGIN DESCRIPTION:
Rebecca Tributary 2 0.0
END DESCRIPTION:
XS GIS Cut Line= 3
      2173728.44     13880096.80      2173338.47     13879888.32
      2173091.23     13880135.35
#Sta/Elev= 30
  4557.8  984.01  4663.8  978.35  4679.5  974.86  4700.7  966.18  4709.1  961.97
  4739.7  952.12  4761.6  948.49  4849.4  945.70  4887.6  943.19  4951.4  942.27
  4951.6  941.77  4955.6  942.27  5042.5  944.59  5049.6  948.93  5056.7  946.90
  5063.7  962.46  5070.8  961.65  5077.9  966.07  5085.0  963.17  5092.0  969.02
  5099.1  968.06  5106.2  973.55  5113.2  973.05  5120.3  975.57  5127.4  975.28
  5134.5  977.44  5155.7  978.08  5162.7  980.27  5235.5  980.71  5349.5  984.16
#Mann=5,-1,0
  4557.8   0.035       0  4700.7    0.12       0  4951.4    0.05       0
  4955.6    0.12       0  5235.5   0.035       0
Bank Sta=4951.4,4955.6
Exp/Cntr=0.3,0.1

Chan Stop Cuts=-1