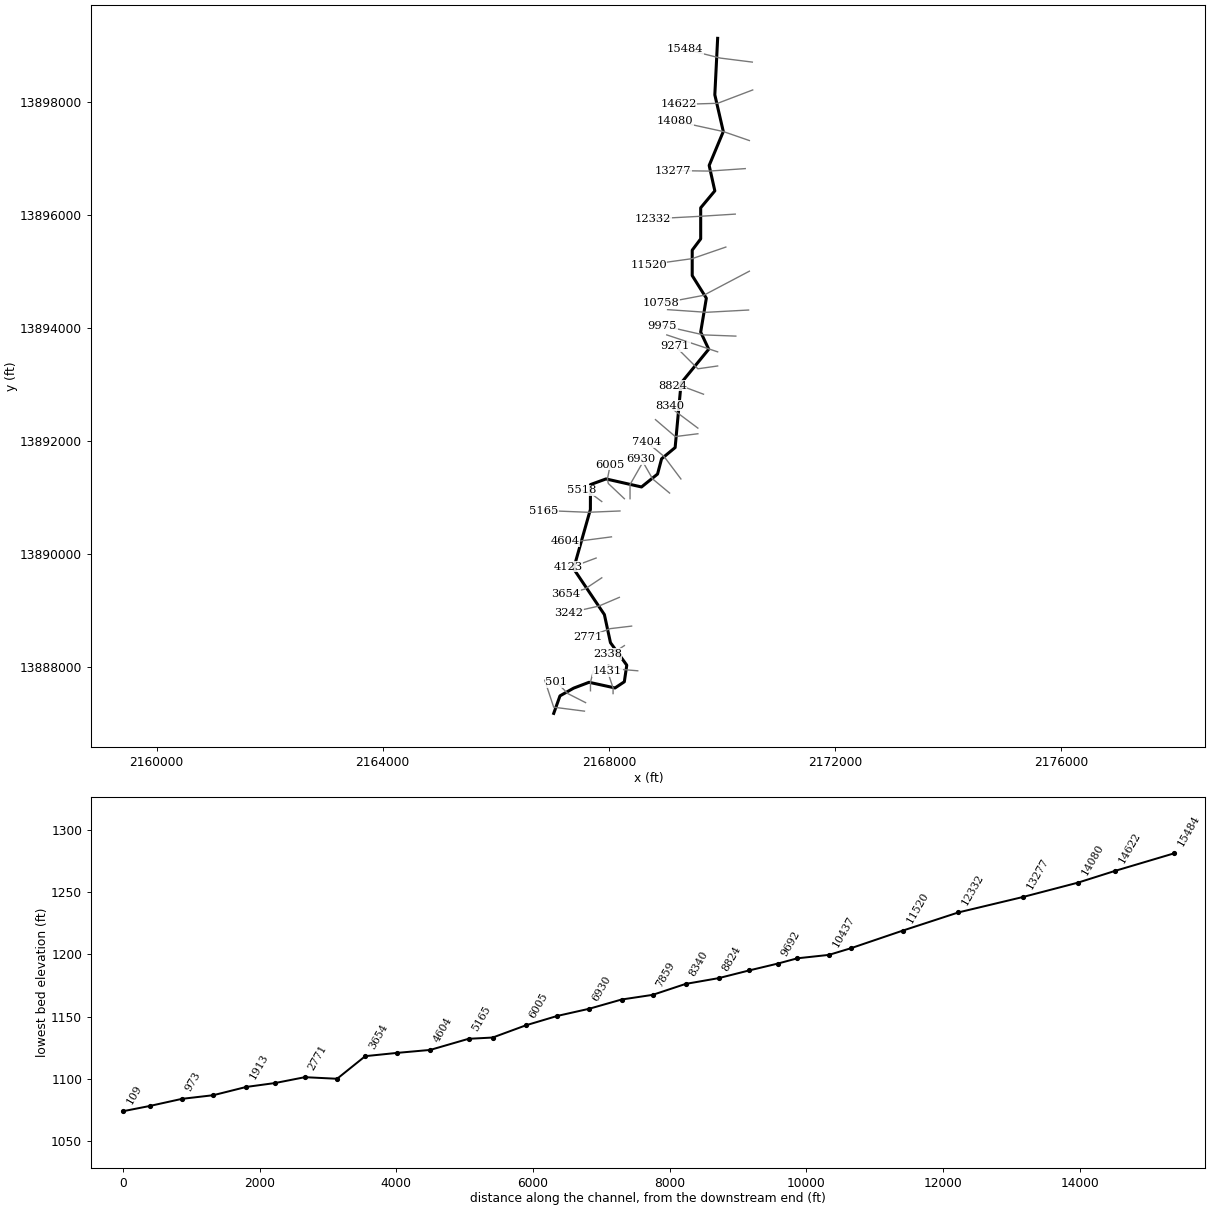
--- Rebecca Tributary 3.prj (project) ---

Proj Title=Rebecca Tributary 3 Base Level Engineering
Current Plan=p01
Default Exp/Contr=0.3,0.1
English Units
Geom File=g01
Flow File=f01
Plan File=p01
BEGIN DESCRIPTION:
Rebecca Tributary 3
END DESCRIPTION:

--- Rebecca Tributary 3.p01 (plan) ---

Plan Title=Multiple Run
Short Identifier=Multiple
Geom File=g01
Flow File=f01
Subcritical Flow
K Sum by GR= 0
Std Step Tol= 0.01
Critical Tol= 0.01
Num of Std Step Trials= 20
Max Error Tol= 0.3
Flow Tol Ratio= 0.001
Split Flow NTrial= 30
Split Flow Tol= 0.02
Split Flow Ratio= 0.02
Log Output Level= 0
Friction Slope Method= 1
Unsteady Friction Slope Method= 2
Unsteady Bridges Friction Slope Method= 1
Parabolic Critical Depth
Global Vel Dist=  1 , 1 , 1
Global Log Level= 0
CheckData=True
Encroach Param= -1, 0, 0, 0
BEGIN DESCRIPTION:
Multiple Run
END DESCRIPTION:

--- Rebecca Tributary 3.f01 (steady flow) ---

Flow Title=Multiple
Number of Profiles=7
Profile Names=10-year,25-year,50-year,1pct_min,100-year,1pct_plu,500-year
River Rch & RM= Rebecca Tributar,Reach-1,15484
    1331    2291    3217    2188    4366    8712    7961
River Rch & RM= Rebecca Tributar,Reach-1,9692
    1482    2558    3600    2452    4893    9764    8950
River Rch & RM= Rebecca Tributar,Reach-1,5518
    2615    4643    6658    4612    9201   18359   17409
Boundary for River Rch & Prof#=Rebecca Tributar,Reach-1,1
Up Type=0
Dn Type=3
Dn Slope=0.005
Boundary for River Rch & Prof#=Rebecca Tributar,Reach-1,2
Up Type=0
Dn Type=3
Dn Slope=0.005
Boundary for River Rch & Prof#=Rebecca Tributar,Reach-1,3
Up Type=0
Dn Type=3
Dn Slope=0.005
Boundary for River Rch & Prof#=Rebecca Tributar,Reach-1,4
Up Type=0
Dn Type=3
Dn Slope=0.005
Boundary for River Rch & Prof#=Rebecca Tributar,Reach-1,5
Up Type=0
Dn Type=3
Dn Slope=0.005
Boundary for River Rch & Prof#=Rebecca Tributar,Reach-1,6
Up Type=0
Dn Type=3
Dn Slope=0.005
Boundary for River Rch & Prof#=Rebecca Tributar,Reach-1,7
Up Type=0
Dn Type=3
Dn Slope=0.005

--- Rebecca Tributary 3.g01 (geometry) ---

Geom Title=Existing Conditions

River Reach=Rebecca Tributar,Reach-1
Reach XY= 30
      2169925.00     13899125.00      2169875.00     13898125.00
      2170025.00     13897475.00      2169775.00     13896875.00
      2169875.00     13896425.00      2169625.00     13896125.00
      2169625.00     13895575.00      2169475.00     13895375.00
      2169475.00     13894925.00      2169725.00     13894525.00
      2169625.00     13893925.00      2169766.96     13893621.70
      2169278.54     13893023.53      2169172.94     13891880.85
      2168933.02     13891681.34      2168861.63     13891411.68
      2168578.32     13891183.04      2167950.07     13891325.23
      2167675.00     13891225.00      2167673.62     13890784.66
      2167376.22     13889735.50      2167921.38     13888923.50
      2168028.75     13888426.55      2168317.38     13888028.33
      2168273.87     13887734.44      2168109.61     13887625.08
      2167650.00     13887725.41      2167376.50     13887621.38
      2167135.63     13887485.05      2167025.00     13887175.00

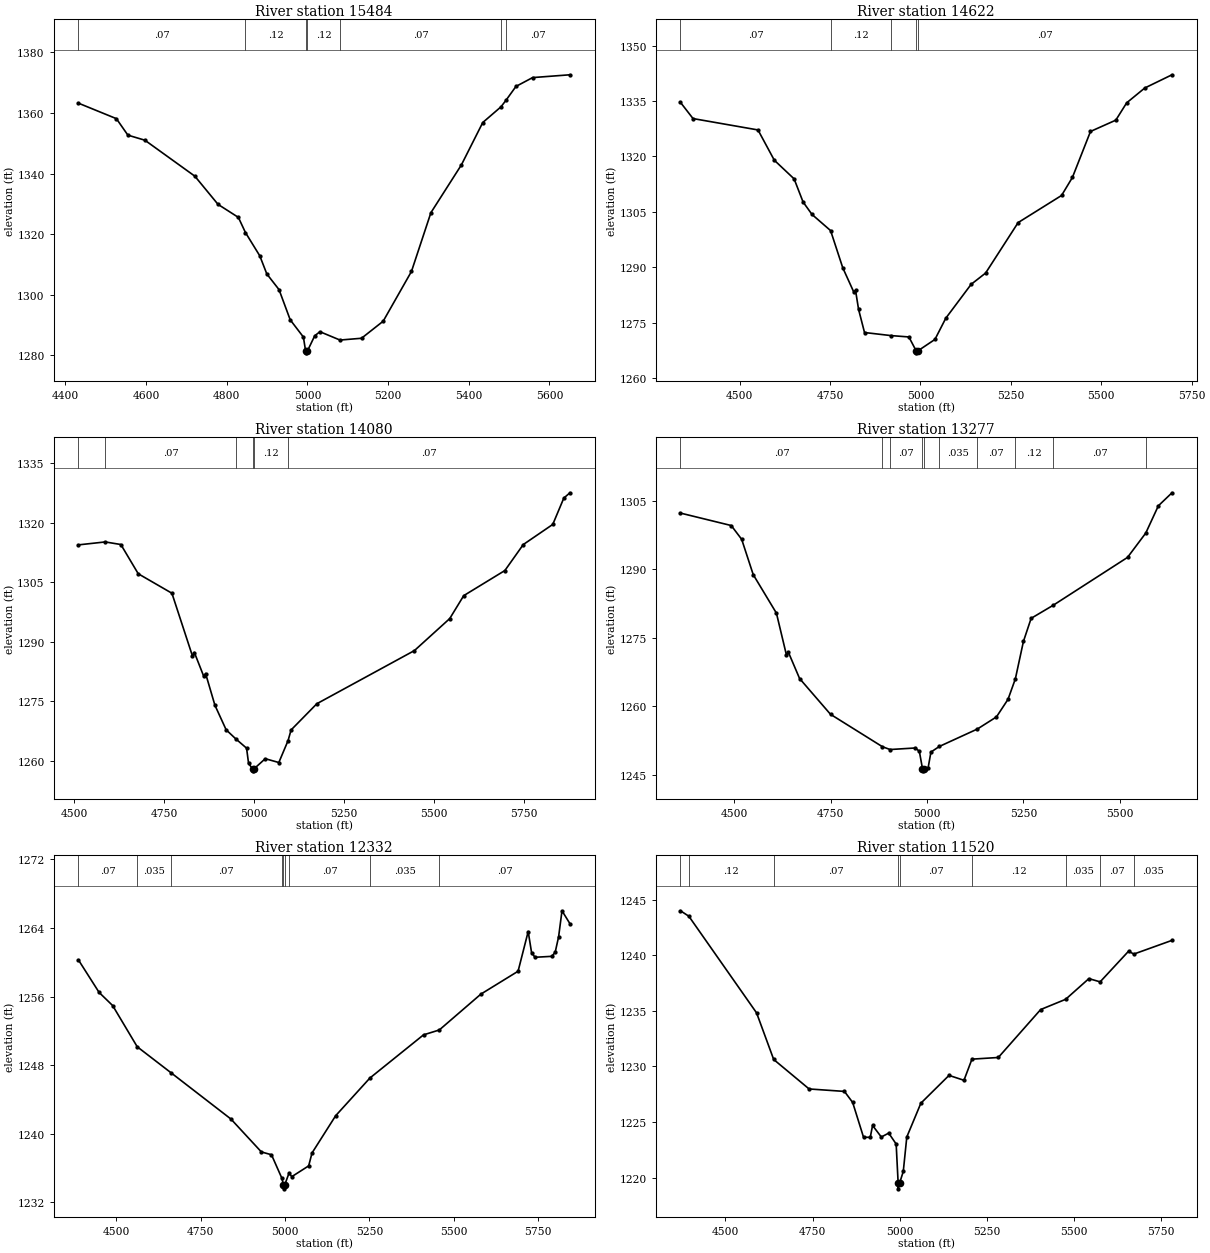
Type RM Length L Ch R = 1,15484,862,862,862
BEGIN DESCRIPTION:
Rebecca Tributary 3 30.0
END DESCRIPTION:
XS GIS Cut Line= 3
      2170538.38     13898704.32      2169975.00     13898775.00
      2169343.90     13898933.49
#Sta/Elev= 30
  4432.2 1363.26  4526.3 1358.15  4554.8 1352.71  4596.9 1351.04  4720.8 1339.17
  4778.3 1329.86  4828.7 1325.57  4846.2 1320.58  4881.8 1312.88  4899.2 1306.91
  4929.5 1301.73  4957.2 1291.77  4989.9 1286.08  4995.5 1281.37  4995.7 1280.87
  4999.5 1281.37  5018.0 1286.50  5030.9 1287.84  5080.6 1285.09  5134.0 1285.68
  5187.7 1291.31  5257.8 1307.73  5306.0 1327.12  5381.5 1342.87  5434.6 1356.88
  5479.7 1362.05  5492.7 1364.32  5516.9 1368.79  5558.1 1371.70  5650.7 1372.63
#Mann=7,-1,0
  4432.2    0.07       0  4846.2    0.12       0  4995.5    0.05       0
  4999.5    0.12       0  5080.6    0.07       0  5479.7   0.035       0
  5492.7    0.07       0
Bank Sta=4995.5,4999.5
Exp/Cntr=0.3,0.1

Type RM Length L Ch R = 1,14622,542,542,542
BEGIN DESCRIPTION:
Rebecca Tributary 3 29.0
END DESCRIPTION:
XS GIS Cut Line= 3
      2170545.33     13898211.27      2169925.00     13897975.00
      2169229.71     13897954.33
#Sta/Elev= 30
  4336.2 1334.61  4370.9 1330.23  4550.6 1327.15  4595.7 1318.96  4650.5 1313.91
  4675.3 1307.65  4700.0 1304.28  4751.4 1299.91  4785.0 1289.86  4815.1 1283.37
  4820.4 1283.72  4828.8 1278.58  4845.2 1272.33  4918.1 1271.50  4967.9 1271.13
  4988.3 1267.33  4988.6 1266.83  4992.3 1267.33  5040.0 1270.46  5070.0 1276.20
  5140.1 1285.37  5180.1 1288.42  5270.1 1302.08  5390.2 1309.42  5420.2 1314.30
  5470.2 1326.74  5540.2 1329.80  5570.3 1334.49  5620.3 1338.50  5695.6 1342.08
#Mann=5,-1,0
  4336.2    0.07       0  4751.4    0.12       0  4918.1    0.07       0
  4988.3    0.05       0  4992.3    0.07       0
Bank Sta=4988.3,4992.3
Exp/Cntr=0.3,0.1

Type RM Length L Ch R = 1,14080,803,803,803
BEGIN DESCRIPTION:
Rebecca Tributary 3 28.0
END DESCRIPTION:
XS GIS Cut Line= 3
      2170486.28     13897315.43      2170025.00     13897475.00
      2169168.44     13897662.30
#Sta/Elev= 30
  4511.9 1314.41  4586.3 1315.15  4629.7 1314.50  4678.0 1307.12  4771.5 1302.21
  4828.6 1286.36  4833.9 1287.26  4859.8 1281.27  4865.0 1281.96  4890.9 1273.96
  4922.1 1267.76  4948.9 1265.47  4978.8 1263.13  4984.4 1259.28  4995.4 1257.91
  4995.6 1257.41  4999.4 1257.91  5030.7 1260.47  5068.4 1259.51  5094.1 1265.05
  5102.4 1267.72  5174.0 1274.34  5445.0 1287.75  5543.0 1295.82  5581.8 1301.60
  5696.1 1307.94  5747.2 1314.49  5829.1 1319.57  5859.8 1326.22  5876.8 1327.55
#Mann=6,-1,0
  4511.9    0.12       0  4586.3    0.07       0  4948.9    0.12       0
  4995.4    0.05       0  4999.4    0.12       0  5094.1    0.07       0
Bank Sta=4995.4,4999.4
Exp/Cntr=0.3,0.1

Type RM Length L Ch R = 1,13277,945,945,945
BEGIN DESCRIPTION:
Rebecca Tributary 3 27.0
END DESCRIPTION:
XS GIS Cut Line= 3
      2170413.39     13896818.90      2169775.00     13896775.00
      2169139.57     13896784.17
#Sta/Elev= 30
  4360.1 1302.27  4491.8 1299.55  4518.9 1296.54  4548.9 1288.81  4609.1 1280.39
  4634.9 1271.29  4639.9 1271.89  4669.2 1266.10  4749.4 1258.28  4884.2 1251.19
  4904.0 1250.58  4969.9 1250.92  4980.0 1250.16  4988.0 1246.42  4988.2 1245.92
  4992.0 1246.42  5002.5 1246.48  5010.0 1250.02  5031.8 1251.25  5130.5 1255.06
  5180.0 1257.71  5210.0 1261.55  5229.1 1266.04  5250.0 1274.21  5270.0 1279.26
  5327.7 1282.14  5520.1 1292.58  5567.5 1297.91  5600.1 1303.86  5635.5 1306.71
#Mann=10,-1,0
  4360.1    0.07       0  4884.2    0.12       0  4904.0    0.07       0
  4988.0    0.05       0  4992.0    0.07       0  5031.8   0.035       0
  5130.5    0.07       0  5229.1    0.12       0  5327.7    0.07       0
  5567.5    0.12       0
Bank Sta=4988,4992
Exp/Cntr=0.3,0.1

Type RM Length L Ch R = 1,12332,812,812,812
BEGIN DESCRIPTION:
Rebecca Tributary 3 26.0
END DESCRIPTION:
XS GIS Cut Line= 3
      2170236.30     13896013.35      2169625.00     13895975.00
      2168781.40     13895930.01
#Sta/Elev= 30
  4387.5 1260.27  4448.9 1256.47  4489.0 1254.94  4561.8 1250.13  4661.2 1247.12
  4839.7 1241.69  4929.9 1237.85  4959.9 1237.52  4990.1 1234.83  4995.5 1234.04
  4995.7 1233.54  4999.5 1234.04  5012.0 1235.39  5020.0 1234.96  5070.1 1236.22
  5080.1 1237.73  5150.2 1242.08  5251.7 1246.48  5410.6 1251.52  5457.4 1252.09
  5580.8 1256.28  5691.0 1258.95  5721.0 1263.59  5731.0 1261.13  5741.1 1260.58
  5791.1 1260.69  5801.1 1261.18  5811.2 1262.98  5821.2 1266.01  5844.8 1264.50
#Mann=9,-1,0
  4387.5    0.07       0  4561.8   0.035       0  4661.2    0.07       0
  4990.1    0.12       0  4995.5    0.05       0  4999.5    0.12       0
  5012.0    0.07       0  5251.7   0.035       0  5457.4    0.07       0
Bank Sta=4995.5,4999.5
Exp/Cntr=0.3,0.1

Type RM Length L Ch R = 1,11520,762,762,762
BEGIN DESCRIPTION:
Rebecca Tributary 3 25.0
END DESCRIPTION:
XS GIS Cut Line= 3
      2170069.65     13895430.02      2169475.00     13895225.00
      2168701.53     13895117.51
#Sta/Elev= 30
  4371.0 1243.99  4395.0 1243.50  4589.3 1234.81  4638.4 1230.62  4740.0 1227.97
  4841.3 1227.75  4864.9 1226.76  4896.1 1223.63  4915.4 1223.62  4922.0 1224.69
  4947.1 1223.65  4968.3 1224.00  4989.7 1223.02  4995.4 1219.49  4995.6 1218.99
  4999.4 1219.49  5010.1 1220.55  5020.2 1223.65  5060.6 1226.69  5141.3 1229.19
  5184.2 1228.75  5207.1 1230.65  5282.7 1230.80  5404.2 1235.11  5475.8 1236.03
  5542.5 1237.89  5574.8 1237.60  5656.2 1240.35  5671.7 1240.10  5780.9 1241.33
#Mann=9,-1,0
  4371.0    0.07       0  4395.0    0.12       0  4638.4    0.07       0
  4995.4    0.05       0  4999.4    0.07       0  5207.1    0.12       0
  5475.8   0.035       0  5574.8    0.07       0  5671.7   0.035       0
Bank Sta=4995.4,4999.4
Exp/Cntr=0.3,0.1

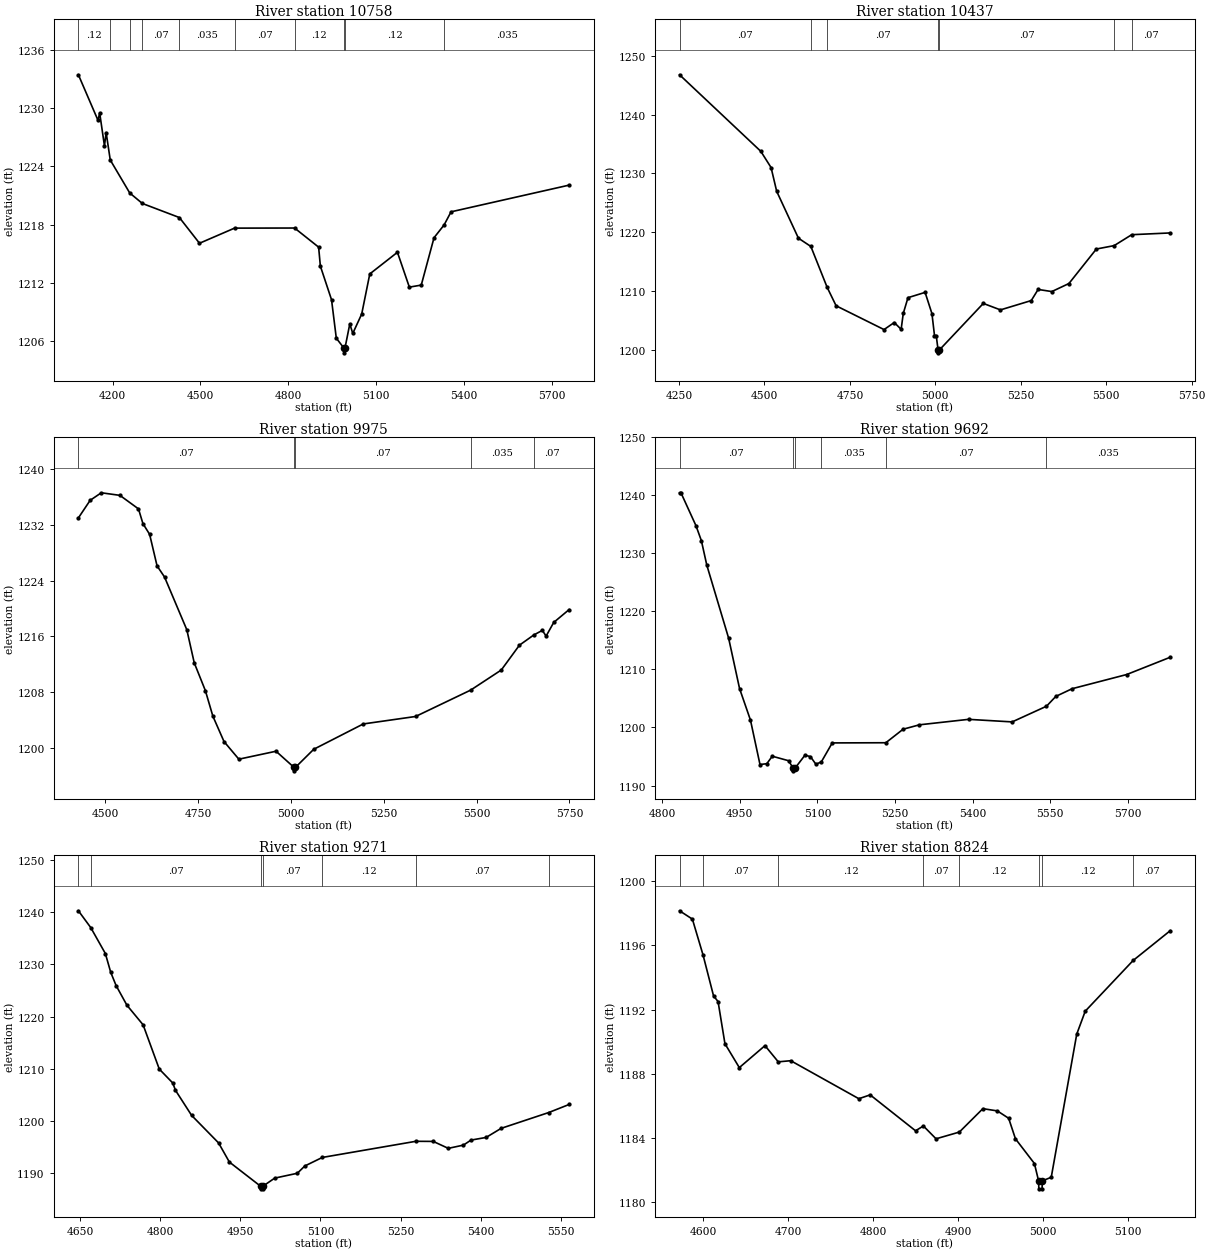
Type RM Length L Ch R = 1,10758,321,321,321
BEGIN DESCRIPTION:
Rebecca Tributary 3 24.0
END DESCRIPTION:
XS GIS Cut Line= 3
      2170486.26     13895002.92      2169675.00     13894575.00
      2168928.65     13894433.75
#Sta/Elev= 30
  4082.8 1233.45  4149.9 1228.75  4155.5 1229.53  4171.9 1226.12  4177.6 1227.50
  4191.7 1224.67  4258.3 1221.27  4301.4 1220.19  4427.9 1218.74  4496.6 1216.09
  4616.4 1217.65  4821.5 1217.66  4903.7 1215.69  4909.6 1213.74  4947.8 1210.27
  4964.1 1206.31  4989.8 1205.30  4990.1 1204.80  4993.8 1205.30  5010.2 1207.78
  5020.4 1206.80  5050.9 1208.80  5078.5 1212.93  5173.0 1215.16  5213.7 1211.57
  5254.4 1211.78  5298.0 1216.66  5332.5 1217.98  5356.2 1219.33  5759.6 1222.08
#Mann=10,-1,0
  4082.8    0.12       0  4191.7    0.07       0  4258.3    0.12       0
  4301.4    0.07       0  4427.9   0.035       0  4616.4    0.07       0
  4821.5    0.12       0  4989.8    0.05       0  4993.8    0.12       0
  5332.5   0.035       0
Bank Sta=4989.8,4993.8
Exp/Cntr=0.3,0.1

Type RM Length L Ch R = 1,10437,462,462,462
BEGIN DESCRIPTION:
Rebecca Tributary 3 23.0
END DESCRIPTION:
XS GIS Cut Line= 3
      2170472.41     13894315.43      2169725.00     13894275.00
      2169039.23     13894322.31
#Sta/Elev= 30
  4251.5 1246.80  4489.3 1233.77  4519.3 1231.01  4535.7 1226.97  4599.4 1218.98
  4635.7 1217.58  4683.3 1210.63  4709.6 1207.48  4849.8 1203.43  4879.8 1204.63
  4899.9 1203.47  4906.1 1206.17  4919.9 1208.86  4970.0 1209.76  4990.0 1206.15
  4997.5 1202.42  5002.5 1202.42  5008.0 1199.97  5008.3 1199.47  5012.0 1199.97
  5140.3 1207.88  5190.5 1206.78  5280.7 1208.37  5300.7 1210.26  5340.8 1209.90
  5390.9 1211.27  5471.1 1217.14  5523.2 1217.72  5574.6 1219.58  5687.4 1219.88
#Mann=7,-1,0
  4251.5    0.07       0  4635.7    0.12       0  4683.3    0.07       0
  5008.0    0.05       0  5012.0    0.07       0  5523.2   0.035       0
  5574.6    0.07       0
Bank Sta=5008,5012
Exp/Cntr=0.3,0.1

Type RM Length L Ch R = 1,9975,283,283,283
BEGIN DESCRIPTION:
Rebecca Tributary 3 22.0
END DESCRIPTION:
XS GIS Cut Line= 3
      2170246.70     13893853.62      2169675.00     13893875.00
      2168944.65     13894041.12
#Sta/Elev= 30
  4427.9 1232.98  4459.6 1235.50  4489.6 1236.58  4539.7 1236.21  4589.7 1234.27
  4601.6 1232.17  4619.7 1230.62  4639.7 1226.10  4659.8 1224.51  4719.8 1216.95
  4739.8 1212.21  4769.8 1208.22  4789.9 1204.57  4819.9 1200.93  4859.9 1198.40
  4960.0 1199.54  5008.3 1197.23  5008.5 1196.73  5012.3 1197.23  5061.5 1199.82
  5194.9 1203.45  5335.7 1204.52  5484.0 1208.30  5566.4 1211.18  5615.3 1214.74
  5653.9 1216.20  5676.9 1216.86  5687.1 1216.04  5707.6 1218.00  5749.0 1219.84
#Mann=5,-1,0
  4427.9    0.07       0  5008.3    0.05       0  5012.3    0.07       0
  5484.0   0.035       0  5653.9    0.07       0
Bank Sta=5008.3,5012.3
Exp/Cntr=0.3,0.1

Type RM Length L Ch R = 1,9692,421,421,421
BEGIN DESCRIPTION:
Rebecca Tributary 3 21.0
END DESCRIPTION:
XS GIS Cut Line= 3
      2169925.04     13893574.99      2169775.00     13893625.00
      2169025.02     13893874.99
#Sta/Elev= 30
  4833.5 1240.43  4836.2 1240.43  4865.2 1234.77  4875.7 1232.18  4886.2 1227.96
  4928.4 1215.38  4949.5 1206.71  4970.6 1201.27  4989.0 1193.62  5002.2 1193.76
  5012.7 1195.05  5044.4 1194.27  5052.8 1193.03  5053.1 1192.53  5057.1 1193.03
  5076.0 1195.23  5086.5 1194.98  5097.1 1193.67  5107.6 1194.07  5128.7 1197.34
  5232.3 1197.37  5265.7 1199.70  5297.3 1200.46  5392.2 1201.40  5476.5 1200.96
  5542.9 1203.66  5560.9 1205.35  5592.5 1206.68  5697.9 1209.12  5782.2 1212.10
#Mann=6,-1,0
  4833.5    0.07       0  5052.8    0.05       0  5057.1    0.07       0
  5107.6   0.035       0  5232.3    0.07       0  5542.9   0.035       0
Bank Sta=5052.8,5057.1
Exp/Cntr=0.3,0.1

Type RM Length L Ch R = 1,9271,447,447,447
BEGIN DESCRIPTION:
Rebecca Tributary 3 20.0
END DESCRIPTION:
XS GIS Cut Line= 3
      2169924.98     13893325.00      2169575.00     13893275.00
      2169175.02     13893674.98
#Sta/Elev= 30
  4646.5 1240.24  4669.6 1237.03  4697.0 1232.06  4707.1 1228.45  4717.2 1225.91
  4737.4 1222.16  4767.7 1218.41  4798.0 1209.94  4823.3 1207.27  4828.3 1205.88
  4858.6 1201.07  4909.1 1195.80  4929.3 1192.14  4987.8 1187.51  4988.1 1187.01
  4991.8 1187.01  4992.1 1187.51  5014.2 1189.06  5056.6 1189.99  5070.7 1191.39
  5103.4 1193.02  5278.6 1196.11  5311.2 1196.09  5339.4 1194.76  5367.7 1195.38
  5381.9 1196.34  5410.2 1196.85  5438.4 1198.59  5527.6 1201.62  5565.7 1203.16
#Mann=7,-1,0
  4646.5   0.035       0  4669.6    0.07       0  4987.8    0.05       0
  4992.1    0.07       0  5103.4    0.12       0  5278.6    0.07       0
  5527.6   0.035       0
Bank Sta=4987.8,4992.1
Exp/Cntr=0.3,0.1

Type RM Length L Ch R = 1,8824,484,484,484
BEGIN DESCRIPTION:
Rebecca Tributary 3 19.0
END DESCRIPTION:
XS GIS Cut Line= 3
      2169674.96     13892825.02      2169275.00     13892975.00
      2169124.95     13892975.00
#Sta/Elev= 30
  4572.5 1198.16  4587.6 1197.64  4600.1 1195.41  4612.5 1192.85  4617.8 1192.50
  4625.9 1189.87  4642.8 1188.38  4673.0 1189.75  4688.6 1188.74  4703.3 1188.81
  4783.4 1186.44  4796.7 1186.68  4850.1 1184.44  4859.3 1184.74  4874.2 1183.94
  4901.6 1184.36  4929.3 1185.82  4946.3 1185.68  4959.6 1185.22  4967.6 1183.94
  4989.9 1182.40  4994.8 1181.32  4995.1 1180.82  4998.9 1180.82  4999.2 1181.32
  5009.7 1181.54  5039.7 1190.47  5049.7 1191.90  5106.0 1195.06  5149.7 1196.92
#Mann=8,-1,0
  4572.5   0.035       0  4600.1    0.07       0  4688.6    0.12       0
  4859.3    0.07       0  4901.6    0.12       0  4994.8    0.05       0
  4999.2    0.12       0  5106.0    0.07       0
Bank Sta=4994.8,4999.2
Exp/Cntr=0.3,0.1

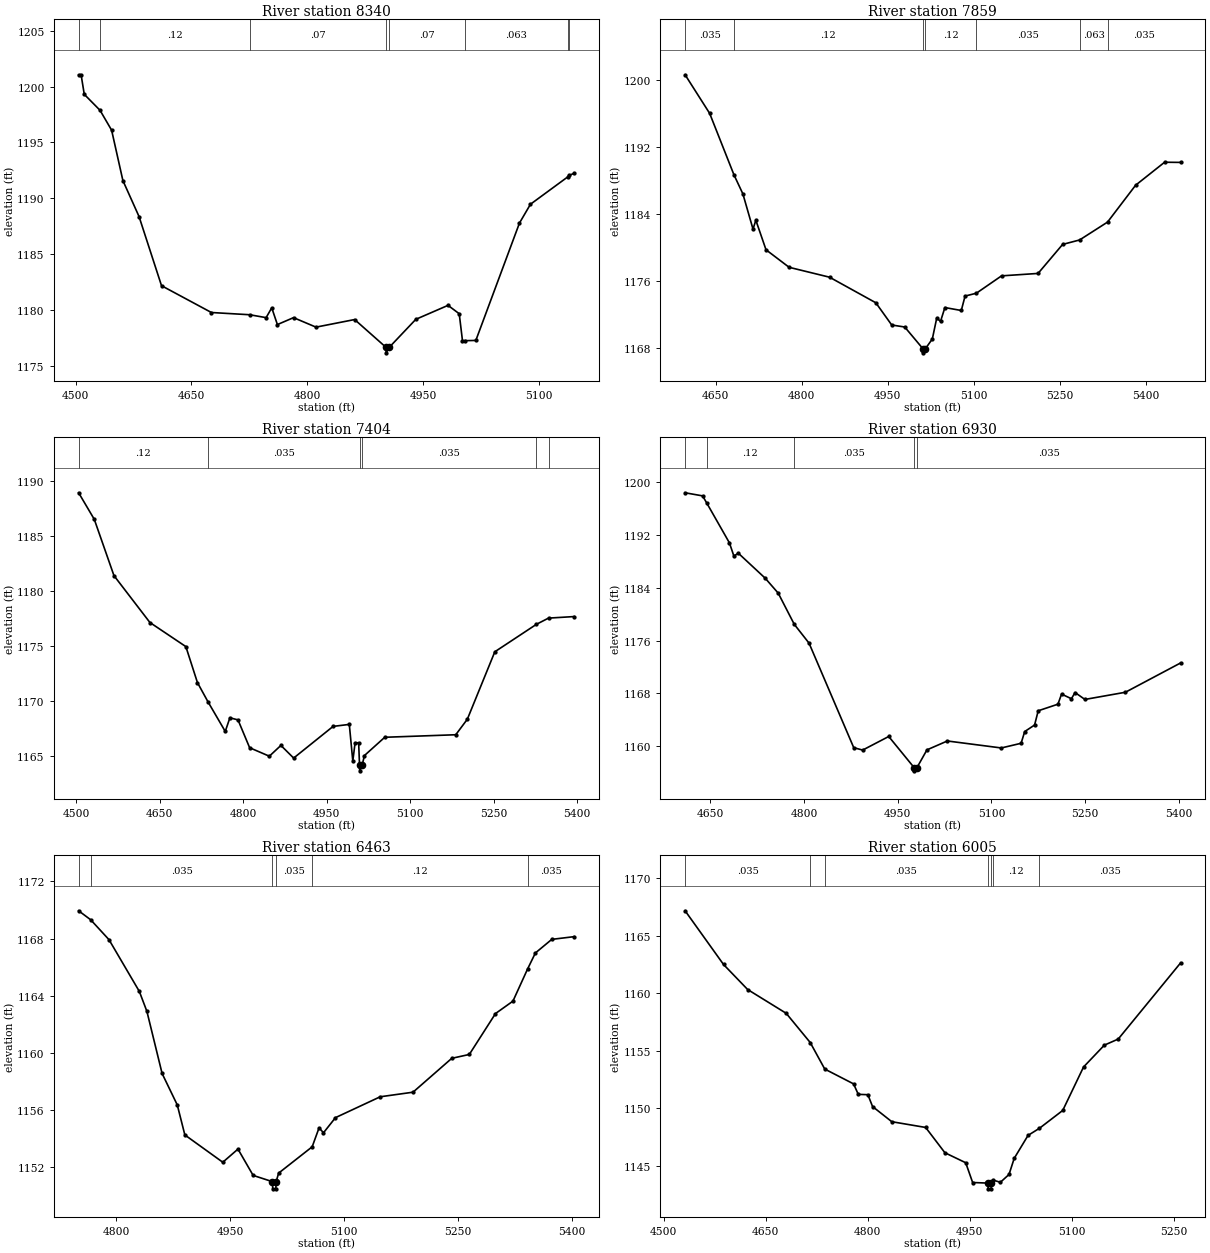
Type RM Length L Ch R = 1,8340,481,481,481
BEGIN DESCRIPTION:
Rebecca Tributary 3 18.0
END DESCRIPTION:
XS GIS Cut Line= 3
      2169575.03     13892224.98      2169175.00     13892525.00
      2169074.97     13892625.03
#Sta/Elev= 30
  4503.9 1201.06  4507.1 1201.06  4511.2 1199.31  4531.6 1197.88  4546.6 1196.10
  4561.2 1191.59  4582.1 1188.37  4611.2 1182.18  4675.8 1179.78  4725.4 1179.58
  4746.6 1179.32  4753.9 1180.20  4761.2 1178.70  4782.1 1179.32  4811.2 1178.47
  4861.2 1179.15  4901.7 1176.67  4902.0 1176.17  4906.1 1176.67  4940.4 1179.17
  4982.1 1180.42  4996.6 1179.67  5000.8 1177.26  5004.3 1177.26  5018.1 1177.28
  5074.6 1187.79  5088.8 1189.47  5136.9 1191.91  5139.3 1192.07  5145.4 1192.24
#Mann=8,-1,0
  4503.9    0.07       0  4531.6    0.12       0  4725.4    0.07       0
  4901.7    0.05       0  4906.1    0.07       0  5004.3   0.063       0
  5136.9    0.12       0  5139.3   0.063       0
Bank Sta=4901.7,4906.1
Exp/Cntr=0.3,0.1

Type RM Length L Ch R = 1,7859,455,455,455
BEGIN DESCRIPTION:
Rebecca Tributary 3 17.0
END DESCRIPTION:
XS GIS Cut Line= 3
      2169575.00     13892125.00      2169175.00     13892075.00
      2168824.99     13892375.01
#Sta/Elev= 30
  4596.9 1200.57  4639.7 1195.97  4682.1 1188.64  4697.7 1186.36  4715.3 1182.17
  4720.3 1183.22  4738.0 1179.70  4778.3 1177.61  4848.8 1176.43  4929.5 1173.38
  4957.2 1170.73  4979.9 1170.49  5011.5 1167.91  5011.8 1167.41  5016.0 1167.91
  5028.0 1169.06  5035.7 1171.56  5042.3 1171.16  5049.9 1172.81  5078.5 1172.46
  5085.1 1174.18  5104.8 1174.52  5148.7 1176.59  5212.4 1176.88  5255.2 1180.34
  5284.8 1180.87  5333.5 1183.00  5382.5 1187.40  5433.0 1190.14  5461.0 1190.12
#Mann=7,-1,0
  4596.9   0.035       0  4682.1    0.12       0  5011.5    0.05       0
  5016.0    0.12       0  5104.8   0.035       0  5284.8   0.063       0
  5333.5   0.035       0
Bank Sta=5011.5,5016
Exp/Cntr=0.3,0.1

Type RM Length L Ch R = 1,7404,474,474,474
BEGIN DESCRIPTION:
Rebecca Tributary 3 16.0
END DESCRIPTION:
XS GIS Cut Line= 3
      2169274.98     13891325.02      2168975.00     13891725.00
      2168674.99     13891975.01
#Sta/Elev= 30
  4504.4 1188.94  4532.5 1186.53  4567.9 1181.41  4632.5 1177.15  4697.1 1174.96
  4717.9 1171.69  4737.0 1169.93  4767.9 1167.25  4776.2 1168.49  4790.8 1168.30
  4811.7 1165.77  4847.1 1165.00  4867.9 1165.98  4890.8 1164.83  4961.7 1167.71
  4990.8 1167.89  4997.1 1164.56  5001.2 1166.22  5007.6 1166.22  5009.2 1164.17
  5009.5 1163.67  5013.8 1164.17  5018.0 1165.06  5054.5 1166.72  5182.1 1166.95
  5202.9 1168.36  5252.3 1174.49  5327.2 1176.99  5348.8 1177.55  5394.9 1177.69
#Mann=6,-1,0
  4504.4    0.12       0  4737.0   0.035       0  5009.2   0.035       0
  5013.8   0.035       0  5327.2    0.07       0  5348.8   0.035       0
Bank Sta=5009.2,5013.8
Exp/Cntr=0.3,0.1

Type RM Length L Ch R = 1,6930,467,467,467
BEGIN DESCRIPTION:
Rebecca Tributary 3 15.0
END DESCRIPTION:
XS GIS Cut Line= 3
      2169075.02     13891074.99      2168775.00     13891325.00
      2168575.02     13891674.96
#Sta/Elev= 30
  4609.5 1198.44  4637.5 1197.97  4643.9 1196.93  4680.5 1190.84  4687.6 1188.85
  4694.8 1189.27  4737.7 1185.49  4758.6 1183.22  4784.3 1178.49  4808.0 1175.63
  4879.6 1159.77  4893.9 1159.41  4935.6 1161.47  4976.2 1156.76  4976.6 1156.26
  4980.9 1156.76  4996.8 1159.44  5029.5 1160.79  5115.9 1159.73  5147.6 1160.44
  5153.4 1162.22  5169.2 1163.21  5175.0 1165.37  5206.6 1166.37  5212.4 1167.90
  5228.2 1167.20  5234.0 1168.14  5249.8 1167.09  5314.6 1168.18  5403.1 1172.63
#Mann=5,-1,0
  4609.5   0.035       0  4643.9    0.12       0  4784.3   0.035       0
  4976.2   0.035       0  4980.9   0.035       0
Bank Sta=4976.2,4980.9
Exp/Cntr=0.3,0.1

Type RM Length L Ch R = 1,6463,458,458,458
BEGIN DESCRIPTION:
Rebecca Tributary 3 14.0
END DESCRIPTION:
XS GIS Cut Line= 3
      2168375.00     13890975.04      2168375.00     13891225.00
      2168575.01     13891575.03
#Sta/Elev= 30
  4750.4 1169.95  4766.3 1169.32  4790.4 1167.93  4830.4 1164.31  4840.4 1162.91
  4860.4 1158.57  4880.4 1156.37  4890.4 1154.27  4940.4 1152.36  4960.4 1153.28
  4980.4 1151.44  5005.9 1151.00  5006.2 1150.50  5010.3 1150.50  5010.7 1151.00
  5014.0 1151.60  5058.2 1153.44  5067.3 1154.77  5073.1 1154.42  5088.9 1155.48
  5147.9 1156.94  5191.1 1157.26  5242.2 1159.63  5265.3 1159.90  5299.8 1162.76
  5322.8 1163.63  5342.2 1165.89  5352.4 1167.00  5374.0 1167.95  5403.5 1168.14
#Mann=6,-1,0
  4750.4   0.063       0  4766.3   0.035       0  5005.9   0.035       0
  5010.7   0.035       0  5058.2    0.12       0  5342.2   0.035       0
Bank Sta=5005.9,5010.7
Exp/Cntr=0.3,0.1

Type RM Length L Ch R = 1,6005,487,487,487
BEGIN DESCRIPTION:
Rebecca Tributary 3 13.0
END DESCRIPTION:
XS GIS Cut Line= 4
      2168275.02     13890974.98      2167990.43     13891244.78
      2167975.00     13891325.00      2168025.00     13891575.01
#Sta/Elev= 30
  4531.3 1167.19  4587.8 1162.52  4623.3 1160.34  4680.0 1158.27  4715.3 1155.73
  4736.7 1153.42  4779.1 1152.13  4786.0 1151.22  4800.1 1151.19  4807.0 1150.16
  4835.3 1148.84  4885.1 1148.34  4913.4 1146.14  4944.0 1145.27  4954.2 1143.55
  4976.8 1143.50  4977.1 1143.00  4981.2 1143.00  4981.6 1143.50  4984.3 1143.76
  4995.0 1143.57  5007.7 1144.25  5015.3 1145.65  5035.7 1147.65  5052.5 1148.27
  5086.7 1149.82  5117.3 1153.60  5147.9 1155.50  5168.3 1156.03  5260.1 1162.66
#Mann=7,-1,0
  4531.3   0.035       0  4715.3    0.12       0  4736.7   0.035       0
  4976.8    0.05       0  4981.6   0.035       0  4984.3    0.12       0
  5052.5   0.035       0
Bank Sta=4976.8,4981.6
Exp/Cntr=0.3,0.1

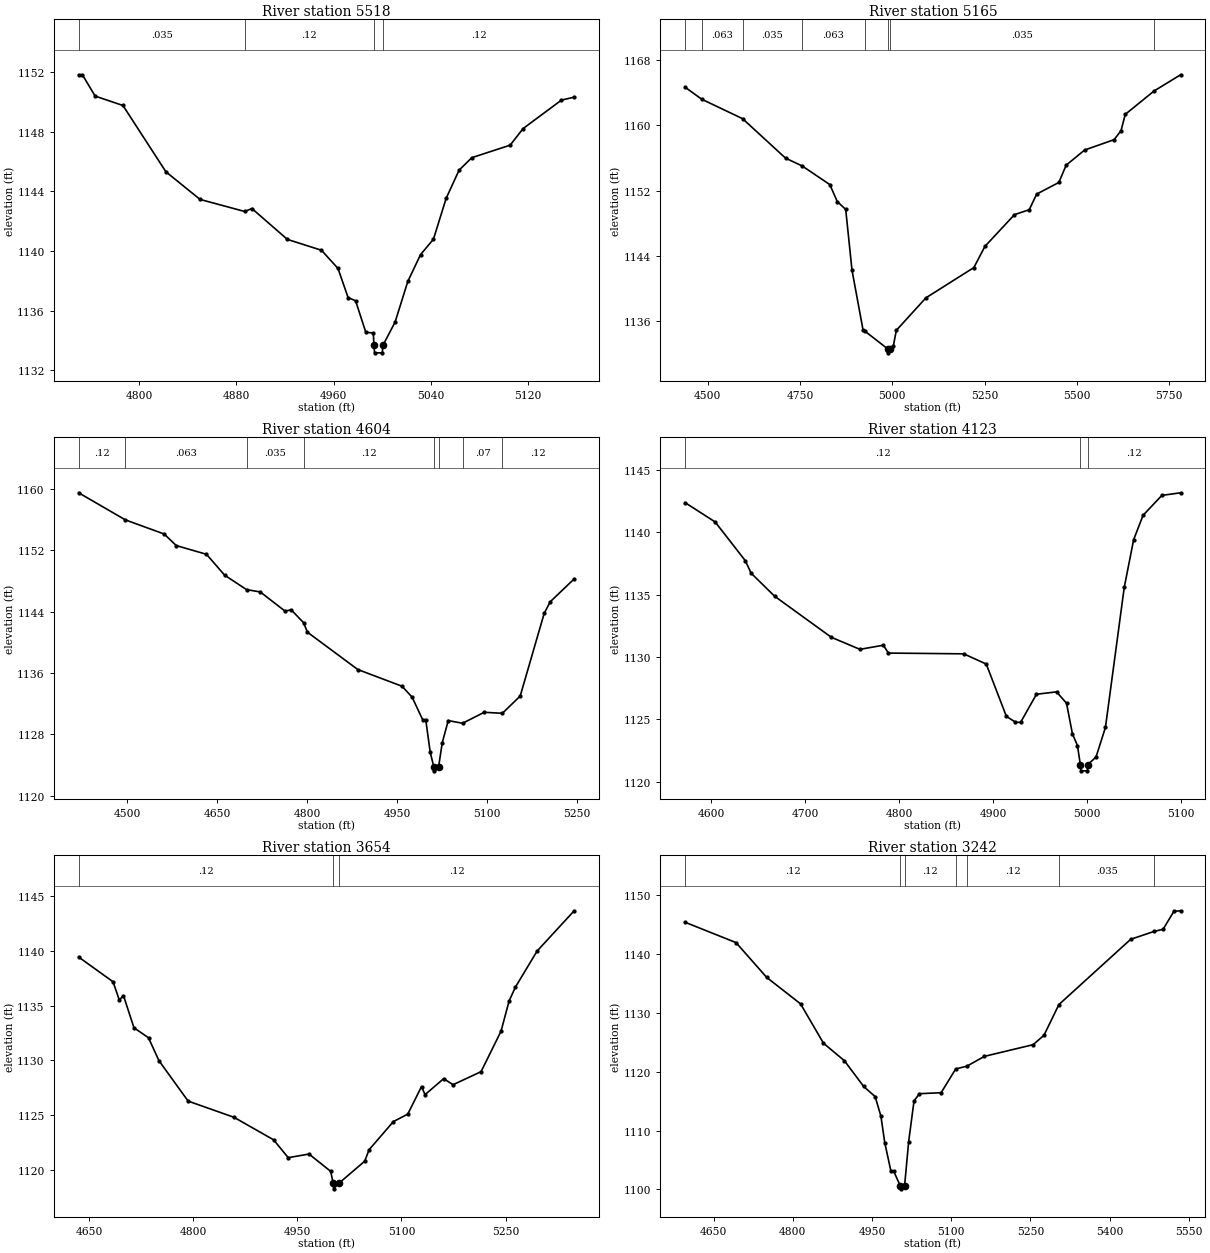
Type RM Length L Ch R = 1,5518,353,353,353
BEGIN DESCRIPTION:
Rebecca Tributary 3 12.0
END DESCRIPTION:
XS GIS Cut Line= 3
      2167875.01     13890924.99      2167675.00     13891075.00
      2167525.03     13891124.99
#Sta/Elev= 30
  4750.0 1151.82  4753.1 1151.82  4763.6 1150.39  4786.5 1149.76  4821.9 1145.31
  4850.0 1143.46  4886.8 1142.65  4892.7 1142.85  4921.9 1140.78  4950.0 1140.05
  4963.6 1138.83  4971.9 1136.88  4978.1 1136.66  4986.5 1134.55  4992.7 1134.50
  4993.2 1133.67  4993.7 1133.17  5000.1 1133.17  5000.6 1133.67  5010.6 1135.23
  5021.1 1137.96  5031.6 1139.76  5042.2 1140.79  5052.7 1143.54  5063.3 1145.42
  5073.8 1146.26  5105.4 1147.10  5116.0 1148.21  5147.6 1150.12  5158.1 1150.32
#Mann=4,-1,0
  4750.0   0.035       0  4886.8    0.12       0  4993.2    0.05       0
  5000.6    0.12       0
Bank Sta=4993.2,5000.6
Exp/Cntr=0.3,0.1

Type RM Length L Ch R = 1,5165,561,561,561
BEGIN DESCRIPTION:
Rebecca Tributary 3 11.0
END DESCRIPTION:
XS GIS Cut Line= 3
      2168197.00     13890758.12      2167635.89     13890734.63
      2166855.04     13890766.42
#Sta/Elev= 30
  4438.4 1164.64  4483.5 1163.17  4594.3 1160.79  4710.6 1155.97  4755.8 1155.01
  4830.7 1152.73  4850.8 1150.66  4873.7 1149.70  4890.8 1142.26  4920.8 1134.93
  4924.9 1134.84  4987.1 1132.66  4987.6 1132.16  4994.6 1132.66  5002.9 1133.02
  5010.9 1134.91  5091.0 1138.88  5221.1 1142.59  5251.1 1145.18  5331.2 1149.06
  5371.2 1149.66  5391.2 1151.57  5451.3 1152.99  5471.3 1155.11  5521.3 1156.96
  5601.4 1158.23  5620.0 1159.34  5631.4 1161.32  5709.8 1164.19  5781.5 1166.16
#Mann=8,-1,0
  4438.4   0.035       0  4483.5   0.063       0  4594.3   0.035       0
  4755.8   0.063       0  4924.9   0.035       0  4987.1   0.035       0
  4994.6   0.035       0  5709.8   0.094       0
Bank Sta=4987.1,4994.6
Exp/Cntr=0.3,0.1

Type RM Length L Ch R = 1,4604,481,481,481
BEGIN DESCRIPTION:
Rebecca Tributary 3 10.0
END DESCRIPTION:
XS GIS Cut Line= 3
      2168046.38     13890299.81      2167475.00     13890225.00
      2167224.96     13890225.00
#Sta/Elev= 30
  4418.7 1159.53  4496.7 1155.99  4561.3 1154.15  4581.5 1152.64  4631.9 1151.50
  4662.1 1148.78  4698.7 1146.89  4721.5 1146.59  4763.0 1144.08  4773.1 1144.26
  4793.7 1142.58  4800.3 1141.33  4884.2 1136.46  4958.0 1134.28  4974.8 1132.85
  4992.4 1129.91  4997.5 1129.91  5005.0 1125.65  5011.0 1123.74  5011.5 1123.24
  5018.9 1123.74  5025.0 1126.89  5035.0 1129.80  5058.9 1129.45  5095.0 1130.88
  5125.3 1130.75  5155.0 1133.00  5195.0 1143.79  5205.0 1145.30  5245.0 1148.29
#Mann=8,-1,0
  4418.7    0.12       0  4496.7   0.063       0  4698.7   0.035       0
  4793.7    0.12       0  5011.0    0.05       0  5018.9    0.12       0
  5058.9    0.07       0  5125.3    0.12       0
Bank Sta=5011,5018.9
Exp/Cntr=0.3,0.1

Type RM Length L Ch R = 1,4123,469,469,469
BEGIN DESCRIPTION:
Rebecca Tributary 3 9.0
END DESCRIPTION:
XS GIS Cut Line= 3
      2167775.00     13889925.00      2167375.00     13889775.00
      2167275.00     13889775.00
#Sta/Elev= 30
  4572.4 1142.38  4604.4 1140.83  4636.5 1137.72  4642.7 1136.72  4667.6 1134.88
  4728.1 1131.58  4758.4 1130.62  4783.3 1130.95  4788.7 1130.32  4868.8 1130.26
  4892.8 1129.44  4914.2 1125.25  4923.9 1124.78  4929.3 1124.76  4946.2 1127.02
  4967.6 1127.21  4978.2 1126.30  4984.5 1123.84  4989.8 1122.91  4992.9 1121.38
  4993.4 1120.88  5000.4 1120.88  5000.9 1121.38  5009.6 1121.99  5019.6 1124.36
  5039.6 1135.58  5049.6 1139.41  5059.6 1141.36  5079.6 1142.96  5099.6 1143.17
#Mann=3,-1,0
  4572.4    0.12       0  4992.9    0.05       0  5000.9    0.12       0
Bank Sta=4992.9,5000.9
Exp/Cntr=0.3,0.1

Type RM Length L Ch R = 1,3654,412,412,412
BEGIN DESCRIPTION:
Rebecca Tributary 3 8.0
END DESCRIPTION:
XS GIS Cut Line= 3
      2167875.03     13889575.02      2167575.00     13889375.00
      2167233.09     13889285.16
#Sta/Elev= 30
  4634.8 1139.43  4684.4 1137.17  4693.4 1135.50  4699.4 1135.91  4714.5 1132.97
  4735.5 1132.05  4750.5 1129.96  4792.6 1126.26  4858.7 1124.78  4915.8 1122.72
  4936.8 1121.09  4966.8 1121.42  4998.0 1119.84  5001.7 1118.74  5002.2 1118.24
  5009.7 1118.74  5047.1 1120.77  5053.3 1121.81  5088.4 1124.39  5109.1 1125.07
  5128.9 1127.59  5134.0 1126.85  5160.8 1128.31  5174.4 1127.76  5214.7 1128.95
  5243.5 1132.65  5255.1 1135.41  5264.2 1136.68  5295.5 1139.98  5348.9 1143.66
#Mann=3,-1,0
  4634.8    0.12       0  5001.7    0.05       0  5009.7    0.12       0
Bank Sta=5001.7,5009.7
Exp/Cntr=0.3,0.1

Type RM Length L Ch R = 1,3242,471,471,471
BEGIN DESCRIPTION:
Rebecca Tributary 3 7.0
END DESCRIPTION:
XS GIS Cut Line= 3
      2168186.04     13889228.97      2167825.00     13889075.00
      2167292.60     13888954.81
#Sta/Elev= 30
  4596.2 1145.35  4692.6 1141.90  4750.7 1135.99  4814.8 1131.50  4858.2 1124.82
  4897.9 1121.84  4934.3 1117.48  4956.1 1115.75  4967.0 1112.43  4974.2 1107.96
  4986.0 1103.07  4991.3 1103.07  5003.6 1100.60  5004.1 1100.10  5011.8 1100.60
  5019.5 1108.11  5029.7 1115.04  5040.0 1116.25  5081.0 1116.42  5108.6 1120.45
  5129.7 1120.92  5163.0 1122.59  5255.2 1124.57  5275.7 1126.16  5304.0 1131.38
  5439.8 1142.45  5484.3 1143.80  5501.3 1144.16  5521.8 1147.22  5534.5 1147.30
#Mann=7,-1,0
  4596.2    0.12       0  5003.6    0.05       0  5011.8    0.12       0
  5108.6    0.07       0  5129.7    0.12       0  5304.0   0.035       0
  5484.3    0.07       0
Bank Sta=5003.6,5011.8
Exp/Cntr=0.3,0.1

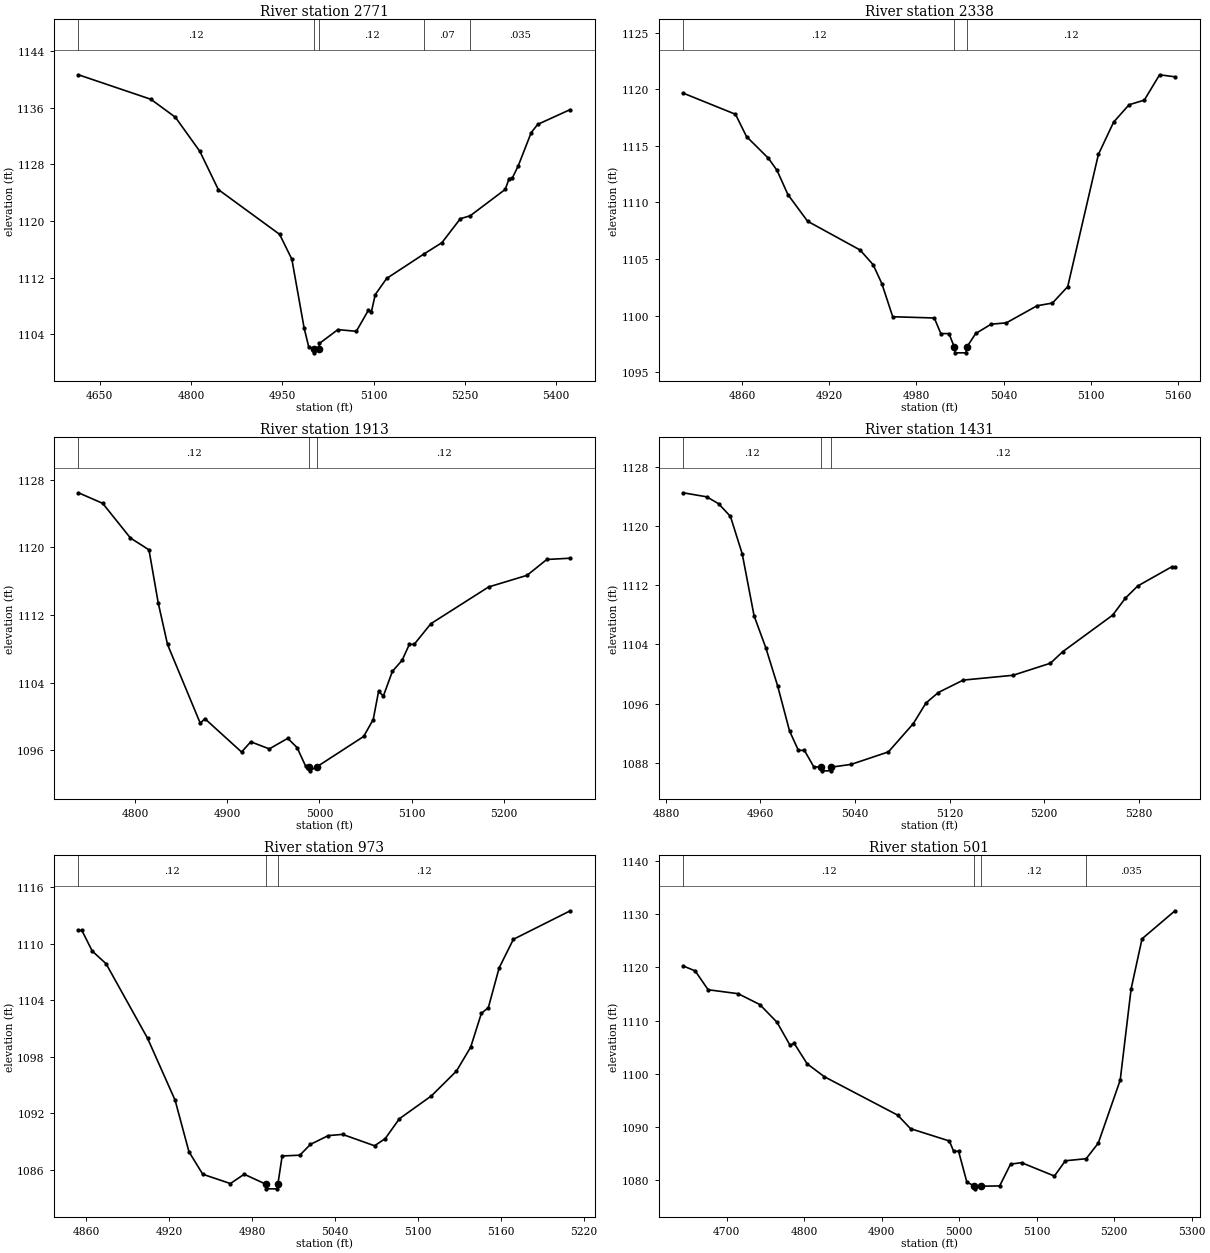
Type RM Length L Ch R = 1,2771,433,433,433
BEGIN DESCRIPTION:
Rebecca Tributary 3 6.0
END DESCRIPTION:
XS GIS Cut Line= 3
      2168403.14     13888720.16      2168025.00     13888675.00
      2167625.03     13888525.01
#Sta/Elev= 30
  4615.1 1140.64  4734.1 1137.18  4774.4 1134.64  4814.6 1129.82  4844.9 1124.43
  4945.6 1118.11  4965.7 1114.60  4985.9 1104.87  4993.4 1102.23  5001.5 1101.88
  5002.0 1101.38  5009.9 1101.88  5011.1 1102.71  5041.3 1104.66  5071.6 1104.42
  5091.2 1107.36  5096.5 1107.21  5102.7 1109.60  5121.4 1111.88  5183.5 1115.38
  5212.2 1116.93  5242.5 1120.32  5258.7 1120.73  5316.3 1124.46  5322.6 1125.98
  5327.9 1126.06  5337.7 1127.80  5359.0 1132.49  5369.7 1133.64  5423.1 1135.73
#Mann=5,-1,0
  4615.1    0.12       0  5001.5    0.05       0  5009.9    0.12       0
  5183.5    0.07       0  5258.7   0.035       0
Bank Sta=5001.5,5009.9
Exp/Cntr=0.3,0.1

Type RM Length L Ch R = 1,2338,425,425,425
BEGIN DESCRIPTION:
Rebecca Tributary 3 5.0
END DESCRIPTION:
XS GIS Cut Line= 3
      2168274.99     13888374.99      2168125.00     13888275.00
      2167974.98     13888224.99
#Sta/Elev= 30
  4819.5 1119.66  4855.5 1117.79  4863.1 1115.82  4878.1 1113.91  4884.1 1112.83
  4891.6 1110.69  4905.1 1108.34  4941.2 1105.80  4950.2 1104.50  4956.2 1102.83
  4963.7 1099.90  4992.3 1099.79  4996.8 1098.41  5002.4 1098.41  5006.1 1097.21
  5006.6 1096.71  5014.1 1096.71  5014.6 1097.21  5020.8 1098.42  5031.4 1099.24
  5041.9 1099.36  5063.0 1100.87  5073.6 1101.11  5084.1 1102.56  5105.2 1114.24
  5115.7 1117.10  5126.3 1118.63  5136.8 1119.04  5147.3 1121.28  5157.9 1121.10
#Mann=3,-1,0
  4819.5    0.12       0  5006.1    0.05       0  5014.6    0.12       0
Bank Sta=5006.1,5014.6
Exp/Cntr=0.3,0.1

Type RM Length L Ch R = 1,1913,482,482,482
BEGIN DESCRIPTION:
Rebecca Tributary 3 4.0
END DESCRIPTION:
XS GIS Cut Line= 3
      2168511.23     13887928.81      2168255.18     13887950.51
      2167989.95     13888028.42
#Sta/Elev= 30
  4738.6 1126.48  4764.9 1125.23  4795.0 1121.12  4815.1 1119.72  4825.1 1113.45
  4835.2 1108.51  4870.7 1099.18  4875.7 1099.72  4915.5 1095.77  4925.5 1096.98
  4945.6 1096.14  4965.6 1097.39  4975.7 1096.30  4985.1 1094.07  4988.8 1094.04
  4989.3 1093.54  4997.5 1094.04  5047.9 1097.61  5058.3 1099.62  5064.1 1102.95
  5069.3 1102.40  5079.1 1105.33  5089.6 1106.63  5097.5 1108.53  5102.7 1108.52
  5120.8 1110.97  5183.4 1115.32  5225.1 1116.70  5246.6 1118.58  5272.0 1118.73
#Mann=3,-1,0
  4738.6    0.12       0  4988.8    0.05       0  4997.5    0.12       0
Bank Sta=4988.8,4997.5
Exp/Cntr=0.3,0.1

Type RM Length L Ch R = 1,1431,458,458,458
BEGIN DESCRIPTION:
Rebecca Tributary 3 3.0
END DESCRIPTION:
XS GIS Cut Line= 3
      2168075.00     13887525.05      2168075.00     13887625.00
      2167974.99     13887925.02
#Sta/Elev= 30
  4894.6 1124.49  4914.6 1123.94  4924.6 1123.01  4934.6 1121.30  4944.6 1116.23
  4954.6 1107.88  4964.6 1103.52  4974.6 1098.37  4984.6 1092.32  4992.1 1089.69
  4997.2 1089.69  5005.1 1087.47  5011.2 1087.42  5011.7 1086.92  5019.5 1086.92
  5020.0 1087.42  5036.7 1087.79  5068.3 1089.48  5089.4 1093.31  5100.0 1096.07
  5110.5 1097.50  5131.6 1099.18  5173.7 1099.83  5205.4 1101.46  5215.9 1103.03
  5258.1 1107.96  5268.6 1110.21  5279.2 1111.89  5308.1 1114.49  5310.8 1114.49
#Mann=3,-1,0
  4894.6    0.12       0  5011.2    0.05       0  5020.0    0.12       0
Bank Sta=5011.2,5020
Exp/Cntr=0.3,0.1

Type RM Length L Ch R = 1,973,472,472,472
BEGIN DESCRIPTION:
Rebecca Tributary 3 2.0
END DESCRIPTION:
XS GIS Cut Line= 3
      2167675.00     13887575.04      2167675.00     13887725.00
      2167725.00     13887924.99
#Sta/Elev= 30
  4854.3 1111.42  4856.8 1111.42  4864.3 1109.23  4874.3 1107.89  4904.3 1099.99
  4924.3 1093.40  4934.3 1087.94  4944.3 1085.55  4964.3 1084.56  4974.3 1085.55
  4989.9 1084.50  4990.4 1084.00  4998.2 1084.00  4998.7 1084.50  5001.8 1087.49
  5014.6 1087.57  5022.3 1088.72  5035.2 1089.65  5045.5 1089.78  5068.7 1088.57
  5076.4 1089.33  5086.7 1091.44  5109.9 1093.87  5128.0 1096.50  5138.3 1099.04
  5146.0 1102.61  5151.1 1103.24  5158.9 1107.45  5169.2 1110.48  5210.4 1113.51
#Mann=3,-1,0
  4854.3    0.12       0  4989.9    0.05       0  4998.7    0.12       0
Bank Sta=4989.9,4998.7
Exp/Cntr=0.3,0.1

Type RM Length L Ch R = 1,501,392,392,392
BEGIN DESCRIPTION:
Rebecca Tributary 3 1.0
END DESCRIPTION:
XS GIS Cut Line= 3
      2167588.65     13887365.40      2167275.00     13887525.00
      2167074.97     13887725.03
#Sta/Elev= 30
  4643.7 1120.29  4659.2 1119.36  4675.9 1115.81  4714.7 1115.06  4742.6 1113.02
  4764.9 1109.67  4781.5 1105.38  4787.1 1105.68  4803.7 1101.85  4826.0 1099.41
  4920.6 1092.17  4937.2 1089.62  4987.3 1087.30  4992.8 1085.36  4999.2 1085.36
  5009.8 1079.59  5019.5 1078.78  5020.0 1078.28  5028.3 1078.78  5052.2 1078.83
  5066.3 1082.94  5080.5 1083.21  5122.9 1080.69  5137.0 1083.57  5163.9 1083.96
  5179.5 1086.90  5207.8 1098.77  5221.9 1115.98  5236.0 1125.41  5278.5 1130.69
#Mann=4,-1,0
  4643.7    0.12       0  5019.5    0.05       0  5028.3    0.12       0
  5163.9   0.035       0
Bank Sta=5019.5,5028.3
Exp/Cntr=0.3,0.1

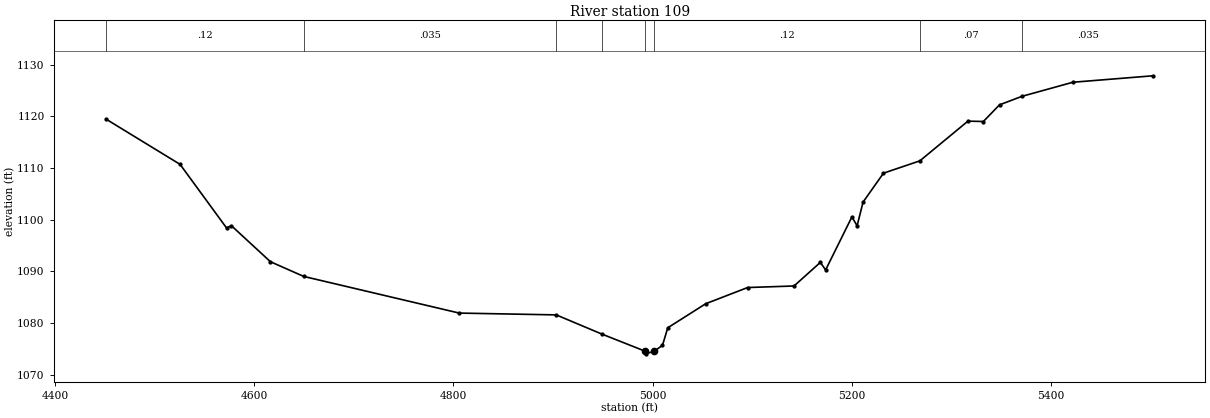
Type RM Length L Ch R = 1,109,0,0,0
BEGIN DESCRIPTION:
Rebecca Tributary 3 0.1
END DESCRIPTION:
XS GIS Cut Line= 3
      2167568.55     13887214.46      2167024.42     13887284.33
      2166866.31     13887761.42
#Sta/Elev= 30
  4451.4 1119.42  4525.6 1110.69  4572.2 1098.41  4577.2 1098.82  4616.3 1091.87
  4649.7 1089.03  4805.9 1081.94  4903.3 1081.59  4949.0 1077.89  4992.7 1074.56
  4993.2 1074.06  5001.6 1074.56  5010.0 1075.71  5015.3 1079.10  5053.4 1083.75
  5095.5 1086.88  5142.1 1087.18  5168.5 1091.74  5173.8 1090.28  5200.2 1100.54
  5205.4 1098.81  5211.4 1103.40  5231.9 1108.99  5268.4 1111.37  5316.7 1119.05
  5332.2 1118.98  5348.4 1122.20  5371.0 1123.85  5422.1 1126.57  5502.6 1127.82
#Mann=8,-1,0
  4451.4    0.12       0  4649.7   0.035       0  4903.3    0.07       0
  4949.0    0.12       0  4992.7    0.05       0  5001.6    0.12       0
  5268.4    0.07       0  5371.0   0.035       0
Bank Sta=4992.7,5001.6
Exp/Cntr=0.3,0.1

Chan Stop Cuts=-1