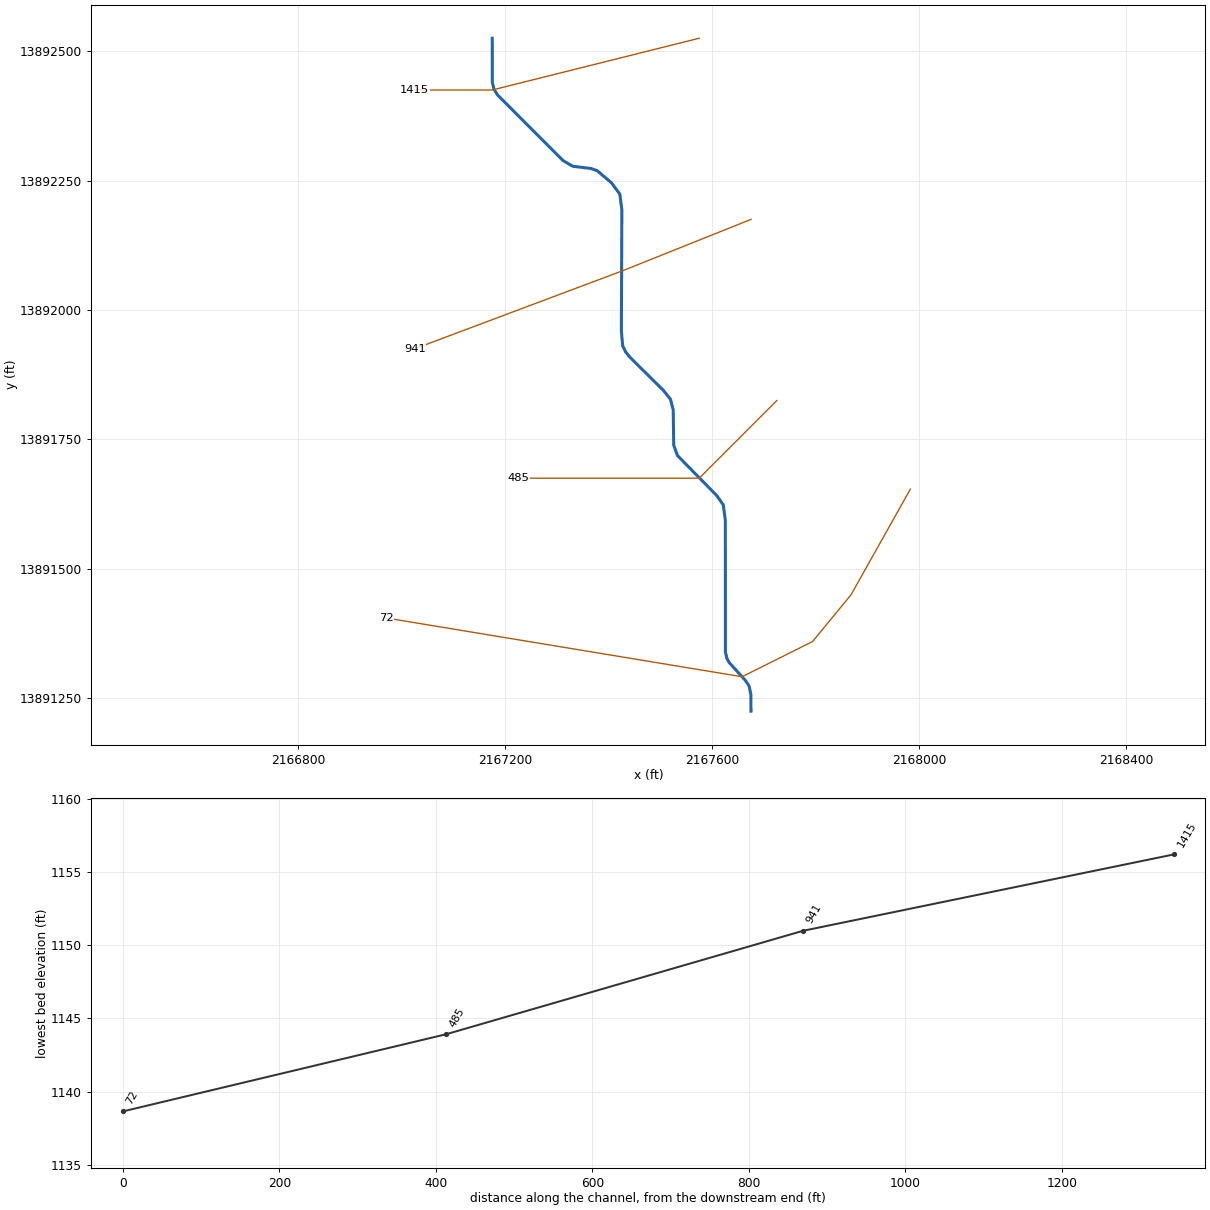
--- Rebecca Tributary 4.prj (project) ---

Proj Title=Rebecca Tributary 4 Base Level Engineering
Current Plan=p01
Default Exp/Contr=0.3,0.1
English Units
Geom File=g01
Flow File=f01
Plan File=p01
BEGIN DESCRIPTION:
Rebecca Tributary 4
END DESCRIPTION:

--- Rebecca Tributary 4.p01 (plan) ---

Plan Title=Multiple Run
Short Identifier=Multiple
Geom File=g01
Flow File=f01
Subcritical Flow
K Sum by GR= 0
Std Step Tol= 0.01
Critical Tol= 0.01
Num of Std Step Trials= 20
Max Error Tol= 0.3
Flow Tol Ratio= 0.001
Split Flow NTrial= 30
Split Flow Tol= 0.02
Split Flow Ratio= 0.02
Log Output Level= 0
Friction Slope Method= 1
Unsteady Friction Slope Method= 2
Unsteady Bridges Friction Slope Method= 1
Parabolic Critical Depth
Global Vel Dist=  1 , 1 , 1
Global Log Level= 0
CheckData=True
Encroach Param= -1, 0, 0, 0
BEGIN DESCRIPTION:
Multiple Run
END DESCRIPTION:

--- Rebecca Tributary 4.f01 (steady flow) ---

Flow Title=Multiple
Number of Profiles=7
Profile Names=10-year,25-year,50-year,1pct_min,100-year,1pct_plu,500-year
River Rch & RM= Rebecca Tributar,Reach-1,1415
    1425    2467    3480    2379    4746    9470    8735
Boundary for River Rch & Prof#=Rebecca Tributar,Reach-1,1
Up Type=0
Dn Type=3
Dn Slope=0.005
Boundary for River Rch & Prof#=Rebecca Tributar,Reach-1,2
Up Type=0
Dn Type=3
Dn Slope=0.005
Boundary for River Rch & Prof#=Rebecca Tributar,Reach-1,3
Up Type=0
Dn Type=3
Dn Slope=0.005
Boundary for River Rch & Prof#=Rebecca Tributar,Reach-1,4
Up Type=0
Dn Type=3
Dn Slope=0.005
Boundary for River Rch & Prof#=Rebecca Tributar,Reach-1,5
Up Type=0
Dn Type=3
Dn Slope=0.005
Boundary for River Rch & Prof#=Rebecca Tributar,Reach-1,6
Up Type=0
Dn Type=3
Dn Slope=0.005
Boundary for River Rch & Prof#=Rebecca Tributar,Reach-1,7
Up Type=0
Dn Type=3
Dn Slope=0.005

--- Rebecca Tributary 4.g01 (geometry) ---

Geom Title=Existing Conditions

River Reach=Rebecca Tributar,Reach-1
Reach XY= 30
      2167175.00     13892525.00      2167175.12     13892440.05
      2167178.38     13892426.40      2167185.43     13892415.18
      2167311.80     13892288.64      2167330.68     13892277.66
      2167365.38     13892273.37      2167377.58     13892269.26
      2167405.56     13892245.55      2167421.55     13892223.75
      2167425.49     13892193.44      2167424.51     13891959.80
      2167427.07     13891930.86      2167432.83     13891918.81
      2167441.47     13891908.25      2167505.33     13891845.14
      2167519.46     13891827.42      2167524.74     13891806.71
      2167525.68     13891738.92      2167532.88     13891718.84
      2167608.53     13891641.75      2167621.45     13891623.53
      2167625.46     13891593.37      2167625.60     13891338.89
      2167628.60     13891326.49      2167632.89     13891318.84
      2167663.94     13891284.56      2167671.35     13891273.49
      2167674.88     13891256.80      2167675.00     13891225.00

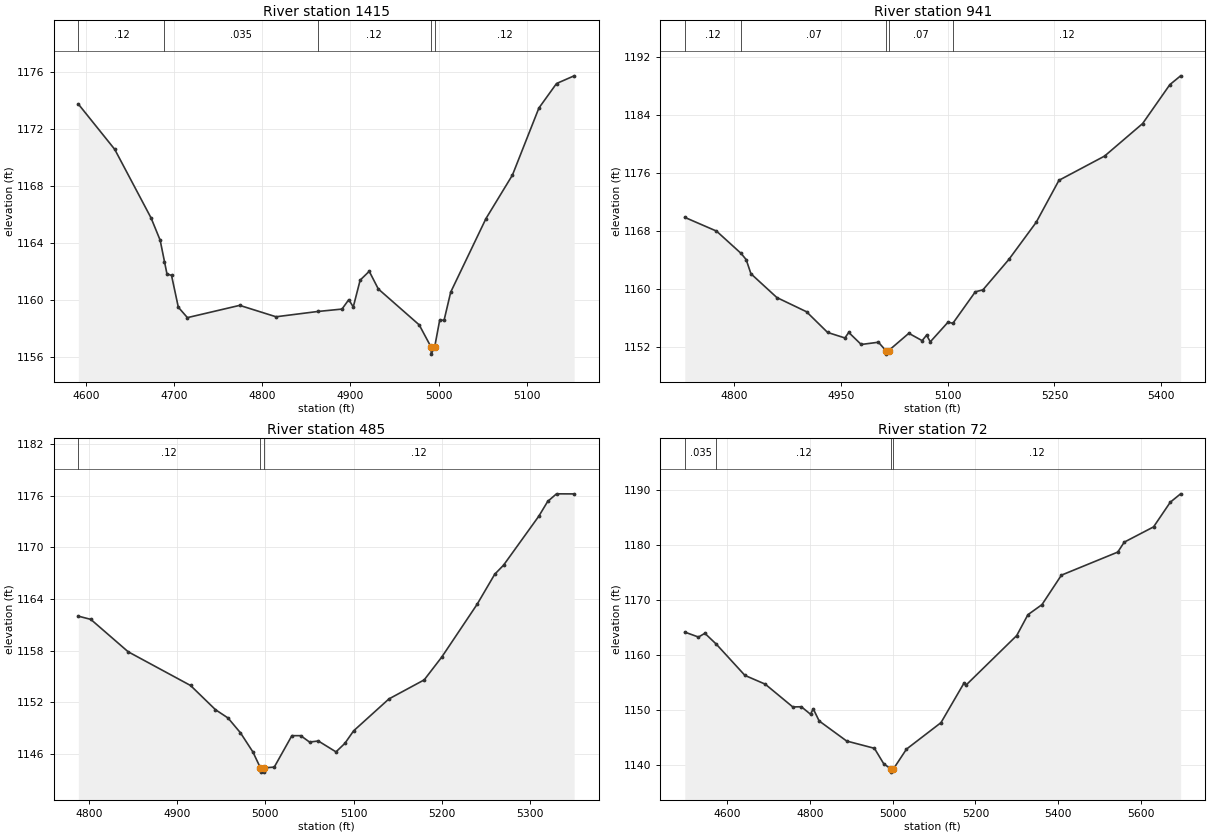
Type RM Length L Ch R = 1,1415,474,474,474
BEGIN DESCRIPTION:
Rebecca Tributary 4 3.0
END DESCRIPTION:
XS GIS Cut Line= 3
      2167575.03     13892525.01      2167175.00     13892425.00
      2167025.04     13892425.00
#Sta/Elev= 30
  4591.4 1173.77  4632.7 1170.59  4673.9 1165.78  4684.2 1164.22  4689.1 1162.72
  4691.9 1161.86  4697.1 1161.75  4704.8 1159.52  4715.1 1158.79  4774.4 1159.65
  4815.6 1158.85  4862.8 1159.22  4890.4 1159.39  4898.1 1160.05  4903.2 1159.54
  4911.0 1161.42  4921.3 1162.04  4931.6 1160.80  4978.0 1158.28  4991.4 1156.73
  4991.6 1156.23  4995.5 1156.73  5001.2 1158.61  5006.2 1158.61  5013.7 1160.58
  5053.7 1165.74  5083.7 1168.79  5113.7 1173.49  5133.7 1175.21  5153.7 1175.75
#Mann=5,-1,0
  4591.4    0.12       0  4689.1   0.035       0  4862.8    0.12       0
  4991.4    0.05       0  4995.5    0.12       0
Bank Sta=4991.4,4995.5
Exp/Cntr=0.3,0.1

Type RM Length L Ch R = 1,941,456,456,456
BEGIN DESCRIPTION:
Rebecca Tributary 4 2.0
END DESCRIPTION:
XS GIS Cut Line= 3
      2167675.03     13892175.01      2167425.00     13892075.00
      2167025.00     13891925.00
#Sta/Elev= 30
  4730.7 1169.85  4775.2 1167.96  4809.8 1164.88  4816.9 1164.03  4823.6 1162.08
  4860.0 1158.80  4901.7 1156.84  4931.3 1153.99  4955.6 1153.23  4961.0 1153.99
  4978.5 1152.33  5002.7 1152.64  5013.0 1151.50  5013.3 1151.00  5017.2 1151.50
  5045.4 1153.87  5064.1 1152.86  5070.3 1153.61  5075.6 1152.70  5100.6 1155.42
  5107.2 1155.24  5138.8 1159.59  5149.5 1159.86  5186.0 1164.06  5224.3 1169.17
  5256.3 1174.96  5320.4 1178.30  5373.8 1182.78  5412.1 1188.15  5427.2 1189.36
#Mann=5,-1,0
  4730.7    0.12       0  4809.8    0.07       0  5013.0    0.05       0
  5017.2    0.07       0  5107.2    0.12       0
Bank Sta=5013,5017.2
Exp/Cntr=0.3,0.1

Type RM Length L Ch R = 1,485,413,413,413
BEGIN DESCRIPTION:
Rebecca Tributary 4 1.0
END DESCRIPTION:
XS GIS Cut Line= 3
      2167724.97     13891824.97      2167575.00     13891675.00
      2167224.99     13891675.00
#Sta/Elev= 30
  4787.9 1162.01  4802.0 1161.64  4844.4 1157.88  4915.1 1153.97  4943.4 1151.16
  4957.6 1150.20  4971.7 1148.48  4985.8 1146.26  4994.3 1144.42  4994.6 1143.92
  4998.3 1143.92  4998.6 1144.42  5010.0 1144.50  5030.0 1148.15  5040.0 1148.15
  5050.0 1147.41  5060.0 1147.53  5080.0 1146.27  5090.0 1147.25  5100.0 1148.71
  5140.0 1152.41  5180.0 1154.62  5200.0 1157.28  5240.0 1163.39  5260.0 1166.88
  5270.0 1167.93  5310.0 1173.62  5320.0 1175.32  5330.0 1176.20  5350.0 1176.19
#Mann=3,-1,0
  4787.9    0.12       0  4994.3    0.05       0  4998.6    0.12       0
Bank Sta=4994.3,4998.6
Exp/Cntr=0.3,0.1

Type RM Length L Ch R = 1,72,0,0,0
BEGIN DESCRIPTION:
Rebecca Tributary 4 0.0
END DESCRIPTION:
XS GIS Cut Line= 5
      2167982.99     13891653.82      2167868.27     13891449.59
      2167794.14     13891359.57      2167657.77     13891291.43
      2166970.37     13891404.89
#Sta/Elev= 30
  4496.7 1164.09  4529.8 1163.19  4545.3 1163.87  4572.8 1161.91  4642.2 1156.22
  4691.3 1154.63  4758.0 1150.49  4778.8 1150.52  4801.0 1149.16  4807.5 1150.15
  4821.9 1147.94  4888.5 1144.29  4955.6 1142.97  4978.0 1140.18  4996.6 1139.14
  4996.9 1138.64  5000.9 1139.14  5033.2 1142.82  5116.7 1147.63  5172.7 1154.86
  5177.8 1154.49  5300.0 1163.46  5327.1 1167.25  5361.1 1169.08  5408.2 1174.44
  5544.5 1178.63  5560.3 1180.44  5631.2 1183.21  5671.7 1187.70  5696.7 1189.22
#Mann=4,-1,0
  4496.7   0.035       0  4572.8    0.12       0  4996.6    0.05       0
  5000.9    0.12       0
Bank Sta=4996.6,5000.9
Exp/Cntr=0.3,0.1

Chan Stop Cuts=-1