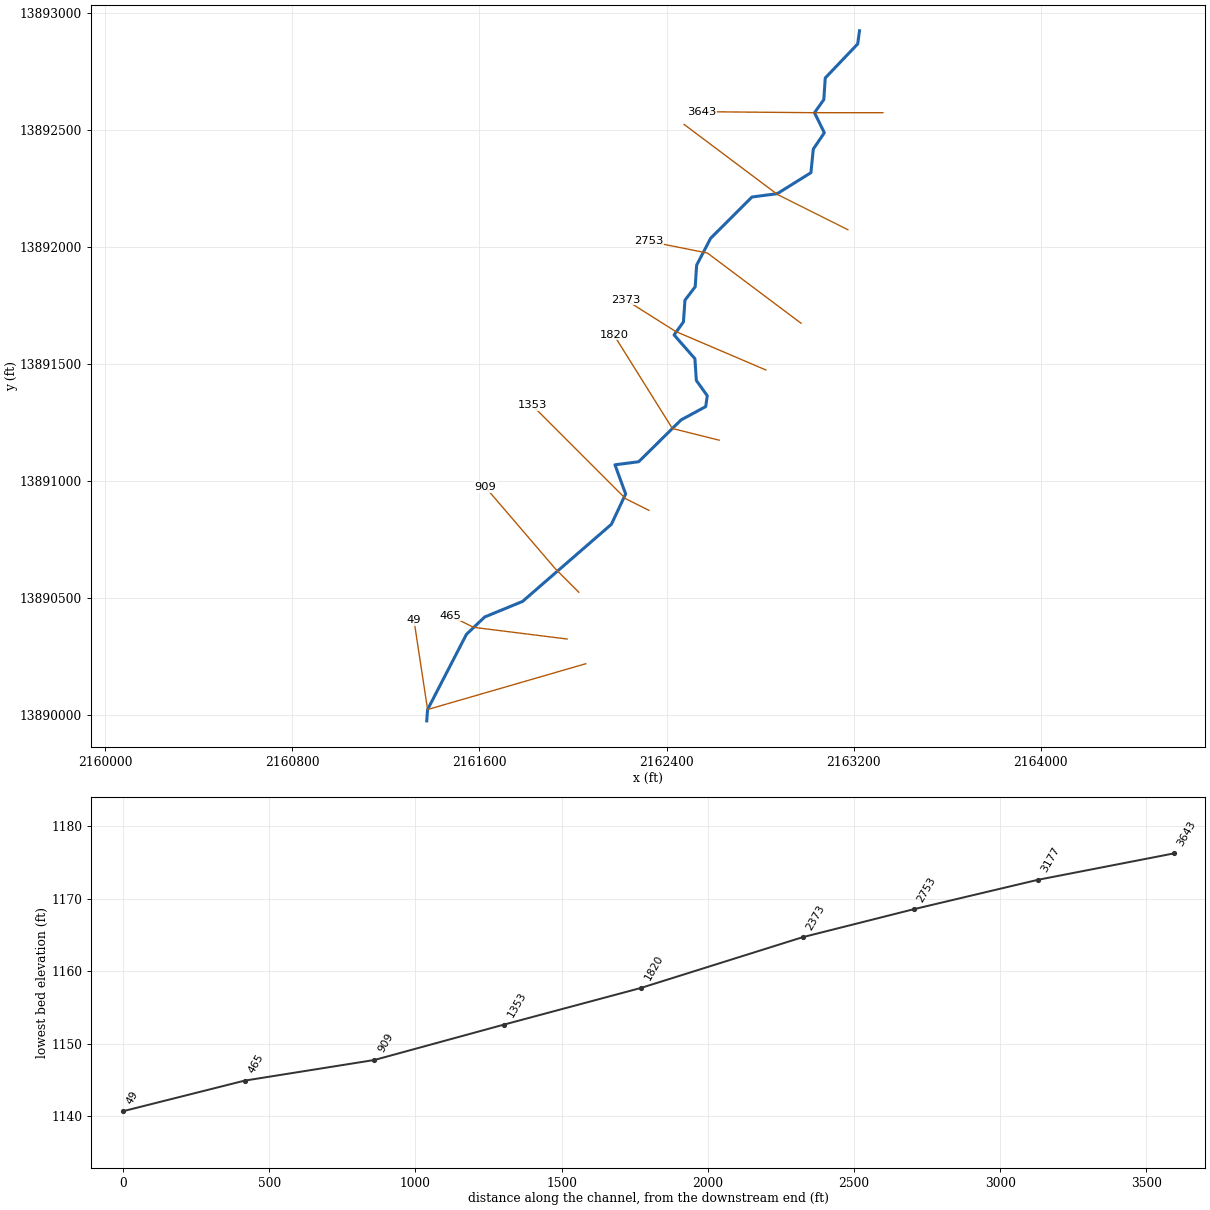
--- Rebecca Tributary 6.prj (project) ---

Proj Title=Rebecca Tributary 6 Base Level Engineering
Current Plan=p01
Default Exp/Contr=0.3,0.1
English Units
Geom File=g01
Flow File=f01
Plan File=p01
BEGIN DESCRIPTION:
Rebecca Tributary 6
END DESCRIPTION:

--- Rebecca Tributary 6.p01 (plan) ---

Plan Title=Multiple Run
Short Identifier=Multiple
Geom File=g01
Flow File=f01
Subcritical Flow
K Sum by GR= 0
Std Step Tol= 0.01
Critical Tol= 0.01
Num of Std Step Trials= 20
Max Error Tol= 0.3
Flow Tol Ratio= 0.001
Split Flow NTrial= 30
Split Flow Tol= 0.02
Split Flow Ratio= 0.02
Log Output Level= 0
Friction Slope Method= 1
Unsteady Friction Slope Method= 2
Unsteady Bridges Friction Slope Method= 1
Parabolic Critical Depth
Global Vel Dist=  1 , 1 , 1
Global Log Level= 0
CheckData=True
Encroach Param= -1, 0, 0, 0
BEGIN DESCRIPTION:
Multiple Run
END DESCRIPTION:

--- Rebecca Tributary 6.f01 (steady flow) ---

Flow Title=Multiple
Number of Profiles=7
Profile Names=10-year,25-year,50-year,1pct_min,100-year,1pct_plu,500-year
River Rch & RM= Rebecca Tributar,Reach-1,3643
    1680    2925    4140    2836    5658   11290   10463
Boundary for River Rch & Prof#=Rebecca Tributar,Reach-1,1
Up Type=0
Dn Type=3
Dn Slope=0.005
Boundary for River Rch & Prof#=Rebecca Tributar,Reach-1,2
Up Type=0
Dn Type=3
Dn Slope=0.005
Boundary for River Rch & Prof#=Rebecca Tributar,Reach-1,3
Up Type=0
Dn Type=3
Dn Slope=0.005
Boundary for River Rch & Prof#=Rebecca Tributar,Reach-1,4
Up Type=0
Dn Type=3
Dn Slope=0.005
Boundary for River Rch & Prof#=Rebecca Tributar,Reach-1,5
Up Type=0
Dn Type=3
Dn Slope=0.005
Boundary for River Rch & Prof#=Rebecca Tributar,Reach-1,6
Up Type=0
Dn Type=3
Dn Slope=0.005
Boundary for River Rch & Prof#=Rebecca Tributar,Reach-1,7
Up Type=0
Dn Type=3
Dn Slope=0.005

--- Rebecca Tributary 6.g01 (geometry) ---

Geom Title=Existing Conditions

River Reach=Rebecca Tributar,Reach-1
Reach XY= 30
      2163225.00     13892925.00      2163217.24     13892868.79
      2163078.61     13892723.50      2163072.45     13892630.90
      2163032.59     13892574.99      2163074.70     13892489.12
      2163027.50     13892419.44      2163017.26     13892318.54
      2162873.42     13892228.83      2162765.21     13892214.48
      2162588.62     13892038.22      2162528.82     13891923.42
      2162522.65     13891830.97      2162478.85     13891773.40
      2162472.32     13891680.48      2162432.33     13891624.90
      2162521.36     13891523.50      2162527.50     13891430.56
      2162574.14     13891365.09      2162567.64     13891318.66
      2162461.80     13891261.36      2162281.11     13891082.88
      2162179.63     13891069.75      2162225.28     13890945.18
      2162164.24     13890815.32      2161784.68     13890485.76
      2161622.69     13890419.17      2161544.77     13890345.13
      2161378.60     13890023.51      2161375.00     13889975.00

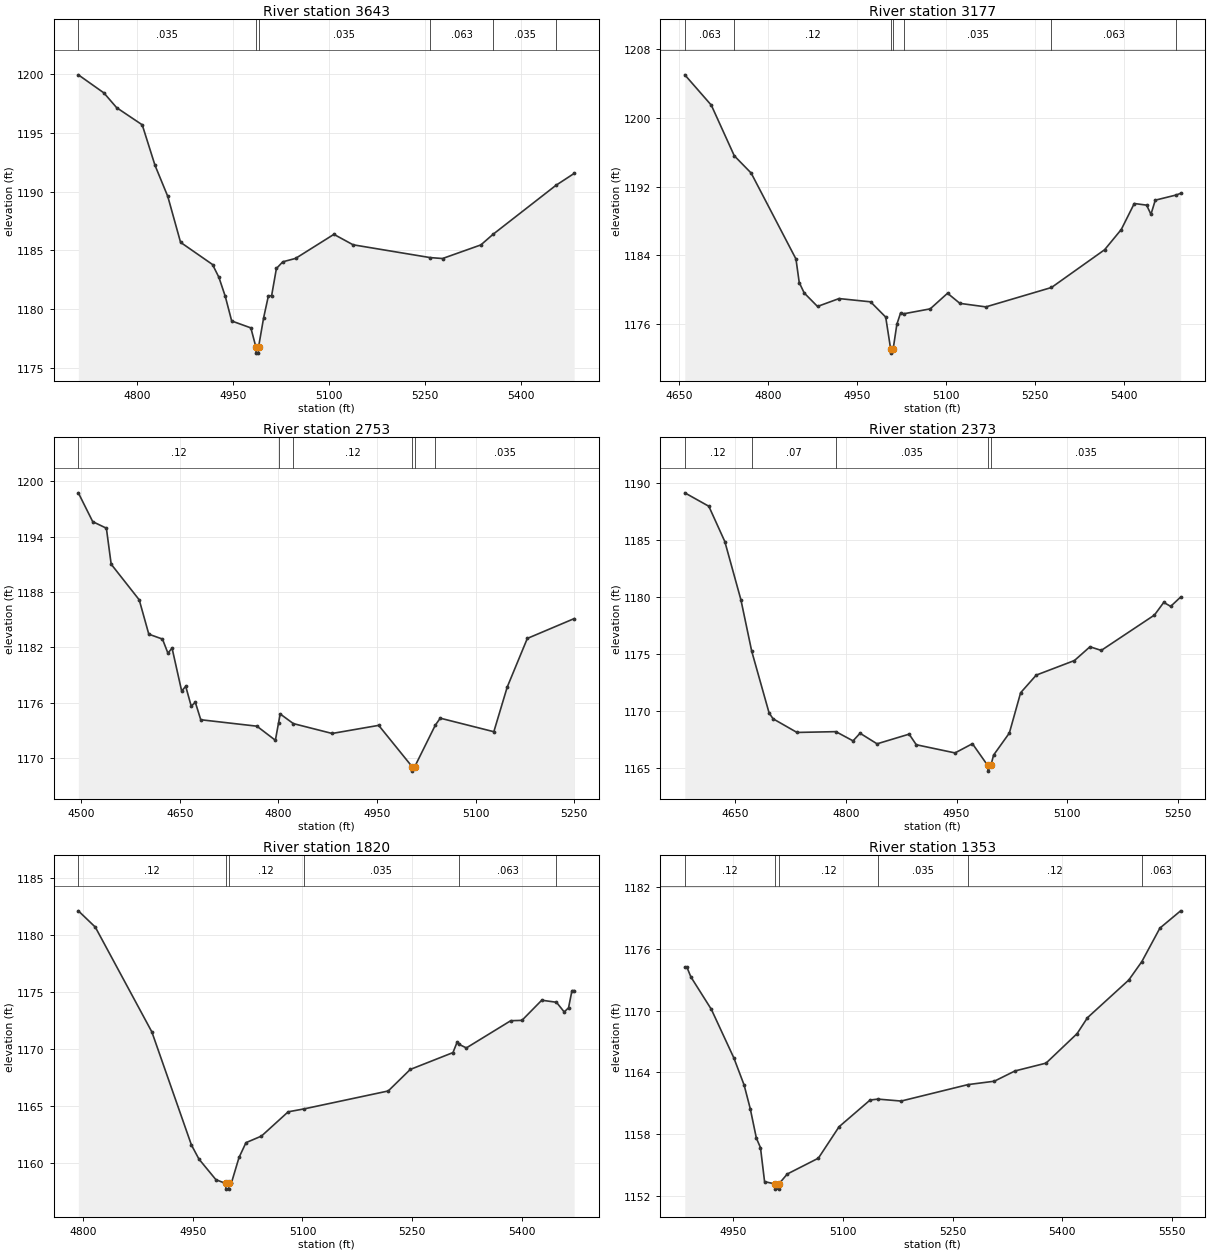
Type RM Length L Ch R = 1,3643,466,466,466
BEGIN DESCRIPTION:
Rebecca Tributary 6 8.0
END DESCRIPTION:
XS GIS Cut Line= 3
      2163324.99     13892575.00      2163025.00     13892575.00
      2162549.01     13892579.28
#Sta/Elev= 30
  4707.6 1199.96  4747.6 1198.42  4767.6 1197.16  4807.6 1195.70  4827.6 1192.25
  4847.6 1189.60  4867.6 1185.69  4917.6 1183.80  4927.6 1182.71  4937.6 1181.08
  4947.6 1178.99  4977.6 1178.40  4985.6 1176.75  4985.8 1176.25  4989.3 1176.25
  4989.6 1176.75  4997.6 1179.26  5005.1 1181.14  5010.1 1181.14  5017.6 1183.46
  5027.6 1184.03  5047.6 1184.32  5107.6 1186.37  5137.6 1185.48  5258.1 1184.39
  5277.6 1184.31  5337.6 1185.47  5356.6 1186.37  5455.2 1190.55  5483.6 1191.56
#Mann=6,-1,0
  4707.6   0.035       0  4985.6   0.035       0  4989.6   0.035       0
  5258.1   0.063       0  5356.6   0.035       0  5455.2   0.063       0
Bank Sta=4985.6,4989.6
Exp/Cntr=0.3,0.1

Type RM Length L Ch R = 1,3177,424,424,424
BEGIN DESCRIPTION:
Rebecca Tributary 6 7.0
END DESCRIPTION:
XS GIS Cut Line= 3
      2163174.99     13892075.01      2162875.00     13892225.00
      2162475.00     13892525.00
#Sta/Elev= 30
  4659.6 1205.04  4704.3 1201.50  4743.0 1195.60  4771.4 1193.59  4846.9 1183.57
  4852.4 1180.83  4860.8 1179.61  4883.2 1178.04  4919.5 1178.96  4972.6 1178.58
  4998.1 1176.80  5006.4 1173.10  5006.7 1172.60  5010.7 1173.10  5016.9 1175.96
  5023.1 1177.27  5028.8 1177.19  5073.1 1177.76  5102.3 1179.58  5123.1 1178.40
  5166.9 1177.99  5277.4 1180.25  5366.9 1184.65  5395.0 1187.01  5416.9 1190.04
  5437.7 1189.85  5445.0 1188.78  5452.3 1190.43  5488.0 1191.04  5495.0 1191.23
#Mann=7,-1,0
  4659.6   0.063       0  4743.0    0.12       0  5006.4    0.05       0
  5010.7    0.12       0  5028.8   0.035       0  5277.4   0.063       0
  5488.0   0.035       0
Bank Sta=5006.4,5010.7
Exp/Cntr=0.3,0.1

Type RM Length L Ch R = 1,2753,380,380,380
BEGIN DESCRIPTION:
Rebecca Tributary 6 6.0
END DESCRIPTION:
XS GIS Cut Line= 3
      2162974.99     13891675.01      2162575.00     13891975.00
      2162325.04     13892024.99
#Sta/Elev= 30
  4495.3 1198.77  4517.2 1195.64  4538.0 1194.93  4545.3 1191.02  4588.0 1187.15
  4602.6 1183.42  4623.4 1182.89  4631.7 1181.36  4638.0 1181.91  4652.6 1177.25
  4658.8 1177.76  4667.2 1175.60  4673.4 1176.03  4681.7 1174.13  4767.2 1173.43
  4795.3 1171.90  4800.1 1173.78  4802.6 1174.76  4822.7 1173.71  4881.7 1172.64
  4952.6 1173.52  5003.3 1169.05  5003.6 1168.55  5007.6 1169.05  5038.8 1173.54
  5046.3 1174.30  5127.9 1172.83  5148.3 1177.68  5178.9 1182.96  5250.2 1185.11
#Mann=6,-1,0
  4495.3    0.12       0  4800.1    0.07       0  4822.7    0.12       0
  5003.3    0.05       0  5007.6    0.12       0  5038.8   0.035       0
Bank Sta=5003.3,5007.6
Exp/Cntr=0.3,0.1

Type RM Length L Ch R = 1,2373,553,553,553
BEGIN DESCRIPTION:
Rebecca Tributary 6 5.0
END DESCRIPTION:
XS GIS Cut Line= 3
      2162824.98     13891475.01      2162439.21     13891639.75
      2162225.01     13891775.00
#Sta/Elev= 30
  4581.3 1189.15  4613.9 1187.97  4635.6 1184.87  4657.4 1179.76  4672.1 1175.23
  4695.7 1169.80  4701.1 1169.29  4733.5 1168.09  4786.3 1168.16  4809.6 1167.35
  4819.1 1168.02  4842.2 1167.09  4885.7 1167.94  4895.4 1167.01  4948.0 1166.29
  4971.6 1167.10  4992.3 1165.19  4992.6 1164.69  4996.6 1165.19  5000.3 1166.10
  5021.7 1168.04  5037.0 1171.58  5058.2 1173.13  5110.0 1174.41  5131.1 1175.62
  5146.4 1175.30  5218.6 1178.41  5231.2 1179.52  5240.6 1179.17  5254.1 1179.99
#Mann=5,-1,0
  4581.3    0.12       0  4672.1    0.07       0  4786.3   0.035       0
  4992.3   0.035       0  4996.6   0.035       0
Bank Sta=4992.3,4996.6
Exp/Cntr=0.3,0.1

Type RM Length L Ch R = 1,1820,467,467,467
BEGIN DESCRIPTION:
Rebecca Tributary 6 4.0
END DESCRIPTION:
XS GIS Cut Line= 3
      2162625.01     13891175.00      2162425.00     13891225.00
      2162174.98     13891625.03
#Sta/Elev= 30
  4793.6 1182.13  4816.8 1180.70  4894.1 1171.50  4948.2 1161.57  4958.5 1160.33
  4981.7 1158.52  4995.0 1158.19  4995.3 1157.69  4999.1 1157.69  4999.4 1158.19
  5002.7 1158.19  5013.3 1160.47  5022.8 1161.77  5044.0 1162.35  5080.5 1164.48
  5101.8 1164.73  5217.3 1166.31  5247.4 1168.20  5305.8 1169.68  5311.7 1170.63
  5313.7 1170.42  5324.1 1170.09  5384.8 1172.48  5400.1 1172.51  5427.2 1174.28
  5447.3 1174.10  5457.9 1173.25  5463.8 1173.61  5468.5 1175.12  5471.5 1175.12
#Mann=6,-1,0
  4793.6    0.12       0  4995.0    0.05       0  4999.4    0.12       0
  5101.8   0.035       0  5313.7   0.063       0  5447.3   0.035       0
Bank Sta=4995,4999.4
Exp/Cntr=0.3,0.1

Type RM Length L Ch R = 1,1353,444,444,444
BEGIN DESCRIPTION:
Rebecca Tributary 6 3.0
END DESCRIPTION:
XS GIS Cut Line= 3
      2162324.97     13890875.02      2162225.00     13890925.00
      2161824.96     13891325.04
#Sta/Elev= 30
  4884.1 1174.26  4886.9 1174.26  4892.4 1173.30  4920.4 1170.14  4951.1 1165.42
  4965.1 1162.79  4973.5 1160.49  4981.9 1157.61  4987.5 1156.69  4993.1 1153.38
  5007.5 1153.15  5007.9 1152.65  5012.2 1152.65  5012.6 1153.15  5024.1 1154.12
  5066.6 1155.66  5094.9 1158.72  5137.3 1161.32  5148.0 1161.41  5179.7 1161.22
  5271.0 1162.82  5307.0 1163.15  5335.3 1164.15  5377.7 1164.91  5420.1 1167.78
  5434.3 1169.33  5490.8 1173.00  5508.6 1174.79  5533.3 1178.05  5561.6 1179.73
#Mann=6,-1,0
  4884.1    0.12       0  5007.5    0.05       0  5012.6    0.12       0
  5148.0   0.035       0  5271.0    0.12       0  5508.6   0.063       0
Bank Sta=5007.5,5012.6
Exp/Cntr=0.3,0.1

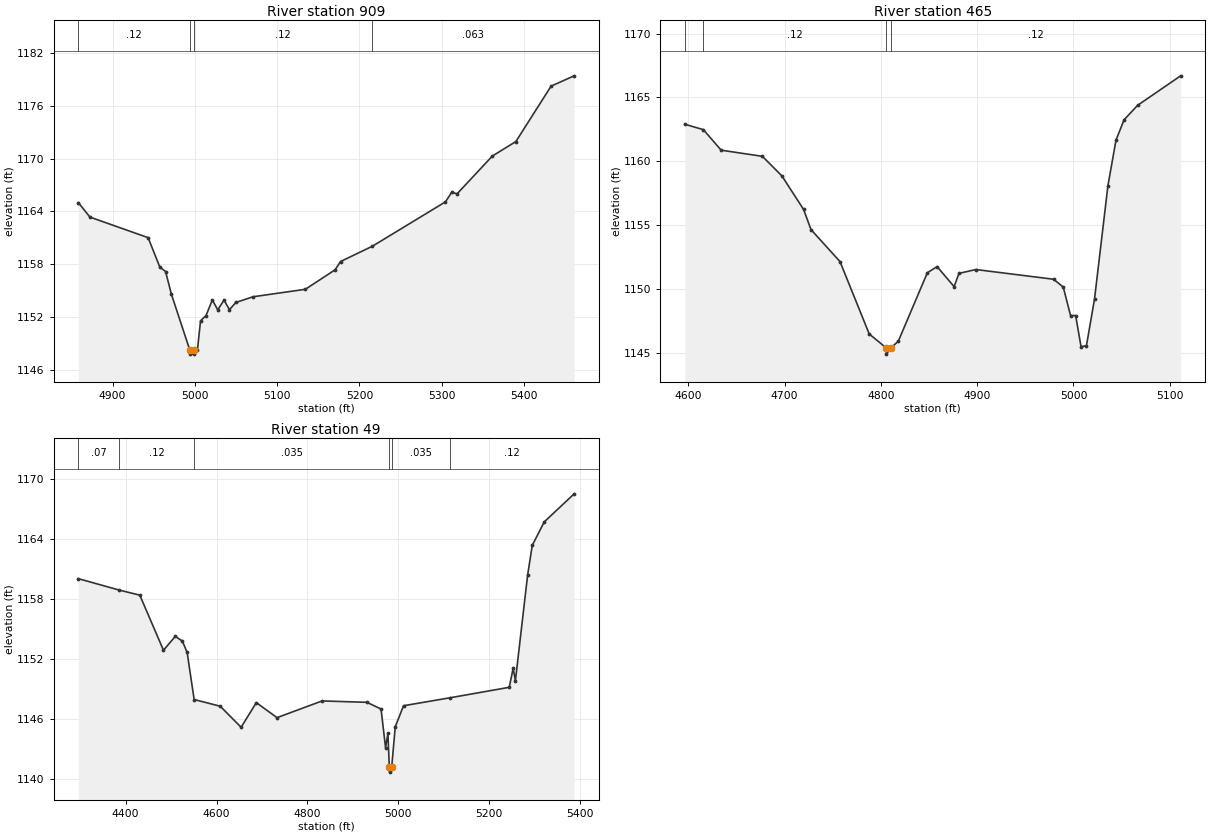
Type RM Length L Ch R = 1,909,444,444,444
BEGIN DESCRIPTION:
Rebecca Tributary 6 2.0
END DESCRIPTION:
XS GIS Cut Line= 3
      2162024.97     13890525.03      2161925.00     13890625.00
      2161624.97     13890975.03
#Sta/Elev= 30
  4858.4 1164.99  4872.5 1163.34  4943.2 1161.00  4957.4 1157.66  4964.4 1157.15
  4971.5 1154.56  4993.7 1148.26  4994.1 1147.76  4998.4 1147.76  4998.8 1148.26
  5003.1 1148.26  5006.9 1151.55  5013.5 1152.14  5021.2 1153.92  5027.8 1152.79
  5035.4 1153.91  5042.0 1152.81  5049.7 1153.63  5070.6 1154.28  5134.2 1155.13
  5170.4 1157.35  5177.0 1158.29  5215.7 1160.03  5304.4 1165.07  5312.0 1166.15
  5318.6 1165.99  5361.4 1170.28  5390.0 1171.93  5432.8 1178.23  5460.8 1179.40
#Mann=4,-1,0
  4858.4    0.12       0  4993.7    0.05       0  4998.8    0.12       0
  5215.7   0.063       0
Bank Sta=4993.7,4998.8
Exp/Cntr=0.3,0.1

Type RM Length L Ch R = 1,465,416,416,416
BEGIN DESCRIPTION:
Rebecca Tributary 6 1.0
END DESCRIPTION:
XS GIS Cut Line= 3
      2161975.00     13890325.00      2161575.00     13890375.00
      2161475.01     13890424.99
#Sta/Elev= 30
  4596.4 1162.90  4615.6 1162.48  4634.2 1160.87  4677.0 1160.39  4697.2 1158.86
  4719.8 1156.23  4727.4 1154.66  4757.6 1152.15  4787.9 1146.49  4805.4 1145.41
  4805.8 1144.91  4810.6 1145.41  4818.1 1145.92  4848.3 1151.28  4858.4 1151.76
  4876.1 1150.19  4881.1 1151.23  4898.7 1151.53  4979.4 1150.77  4989.4 1150.16
  4997.0 1147.93  5002.3 1147.93  5007.9 1145.49  5013.5 1145.57  5021.9 1149.23
  5035.8 1158.09  5044.2 1161.66  5052.6 1163.25  5066.6 1164.38  5111.3 1166.69
#Mann=4,-1,0
  4596.4    0.07       0  4615.6    0.12       0  4805.4    0.05       0
  4810.6    0.12       0
Bank Sta=4805.4,4810.6
Exp/Cntr=0.3,0.1

Type RM Length L Ch R = 1,49,0,0,0
BEGIN DESCRIPTION:
Rebecca Tributary 6 0.0
END DESCRIPTION:
XS GIS Cut Line= 3
      2162055.01     13890219.40      2161378.60     13890023.51
      2161320.27     13890406.19
#Sta/Elev= 30
  4295.8 1160.01  4384.9 1158.88  4431.1 1158.36  4483.2 1152.86  4509.3 1154.25
  4524.8 1153.77  4535.3 1152.64  4550.7 1147.94  4608.1 1147.27  4654.1 1145.17
  4687.6 1147.63  4733.1 1146.13  4832.4 1147.80  4930.9 1147.66  4962.1 1146.99
  4972.0 1143.13  4977.2 1144.56  4980.3 1141.19  4980.7 1140.69  4985.5 1141.19
  4993.3 1145.22  5011.6 1147.32  5113.4 1148.11  5244.3 1149.16  5252.8 1151.06
  5257.8 1149.83  5284.7 1160.37  5294.9 1163.33  5321.3 1165.68  5387.1 1168.48
#Mann=6,-1,0
  4295.8    0.07       0  4384.9    0.12       0  4550.7   0.035       0
  4980.3   0.035       0  4985.5   0.035       0  5113.4    0.12       0
Bank Sta=4980.3,4985.5
Exp/Cntr=0.3,0.1

Chan Stop Cuts=-1