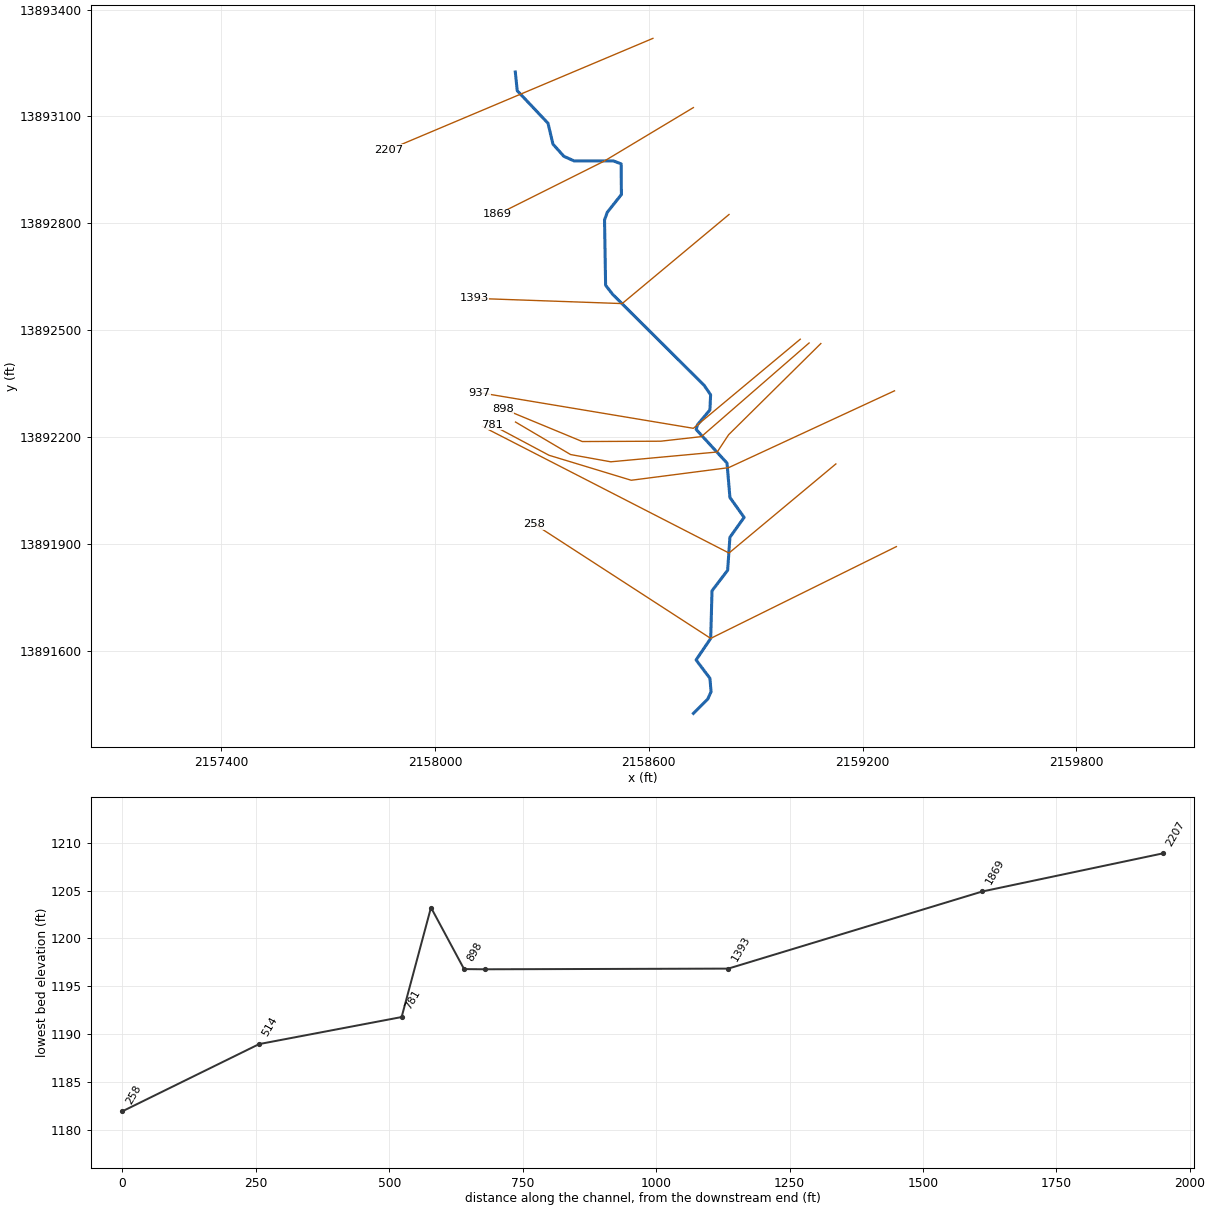
--- Rebecca Tributary 9.prj (project) ---

Proj Title=Rebecca Tributary 9 Base Level Engineering
Current Plan=p01
Default Exp/Contr=0.3,0.1
English Units
Geom File=g01
Flow File=f01
Plan File=p01
BEGIN DESCRIPTION:
Rebecca Tributary 9
END DESCRIPTION:

--- Rebecca Tributary 9.p01 (plan) ---

Plan Title=Multiple Run
Short Identifier=Multiple
Geom File=g01
Flow File=f01
Subcritical Flow
K Sum by GR= 0
Std Step Tol= 0.01
Critical Tol= 0.01
Num of Std Step Trials= 20
Max Error Tol= 0.3
Flow Tol Ratio= 0.001
Split Flow NTrial= 30
Split Flow Tol= 0.02
Split Flow Ratio= 0.02
Log Output Level= 0
Friction Slope Method= 1
Unsteady Friction Slope Method= 2
Unsteady Bridges Friction Slope Method= 1
Parabolic Critical Depth
Global Vel Dist=  1 , 1 , 1
Global Log Level= 0
CheckData=True
Encroach Param= -1, 0, 0, 0
BEGIN DESCRIPTION:
Multiple Run
END DESCRIPTION:

--- Rebecca Tributary 9.f01 (steady flow) ---

Flow Title=Multiple
Number of Profiles=7
Profile Names=10-year,25-year,50-year,1pct_min,100-year,1pct_plu,500-year
River Rch & RM= Rebecca Tributar,Reach-1,2207
     877    1477    2046    1376    2746    5480    4888
River Rch & RM= Rebecca Tributar,Reach-1,1869
    1131    1932    2701    1831    3654    7290    6613
Boundary for River Rch & Prof#=Rebecca Tributar,Reach-1,1
Up Type=0
Dn Type=3
Dn Slope=0.005
Boundary for River Rch & Prof#=Rebecca Tributar,Reach-1,2
Up Type=0
Dn Type=3
Dn Slope=0.005
Boundary for River Rch & Prof#=Rebecca Tributar,Reach-1,3
Up Type=0
Dn Type=3
Dn Slope=0.005
Boundary for River Rch & Prof#=Rebecca Tributar,Reach-1,4
Up Type=0
Dn Type=3
Dn Slope=0.005
Boundary for River Rch & Prof#=Rebecca Tributar,Reach-1,5
Up Type=0
Dn Type=3
Dn Slope=0.005
Boundary for River Rch & Prof#=Rebecca Tributar,Reach-1,6
Up Type=0
Dn Type=3
Dn Slope=0.005
Boundary for River Rch & Prof#=Rebecca Tributar,Reach-1,7
Up Type=0
Dn Type=3
Dn Slope=0.005

--- Rebecca Tributary 9.g01 (geometry) ---

Geom Title=Existing Conditions

River Reach=Rebecca Tributar,Reach-1
Reach XY= 30
      2158225.00     13893225.00      2158230.33     13893172.49
      2158316.83     13893081.03      2158330.74     13893022.42
      2158361.34     13892988.23      2158390.06     13892975.35
      2158500.43     13892975.38      2158522.18     13892967.05
      2158522.88     13892881.07      2158483.15     13892831.06
      2158475.52     13892809.79      2158478.53     13892626.46
      2158497.86     13892601.47      2158755.57     13892345.09
      2158773.34     13892318.95      2158771.41     13892276.65
      2158736.39     13892234.87      2158732.84     13892221.60
      2158819.45     13892127.43      2158827.56     13892030.90
      2158867.44     13891975.00      2158827.55     13891919.11
      2158821.15     13891826.60      2158777.27     13891769.06
      2158773.61     13891635.44      2158732.57     13891574.99
      2158771.40     13891523.42      2158774.61     13891485.68
      2158765.36     13891465.21      2158725.00     13891425.00

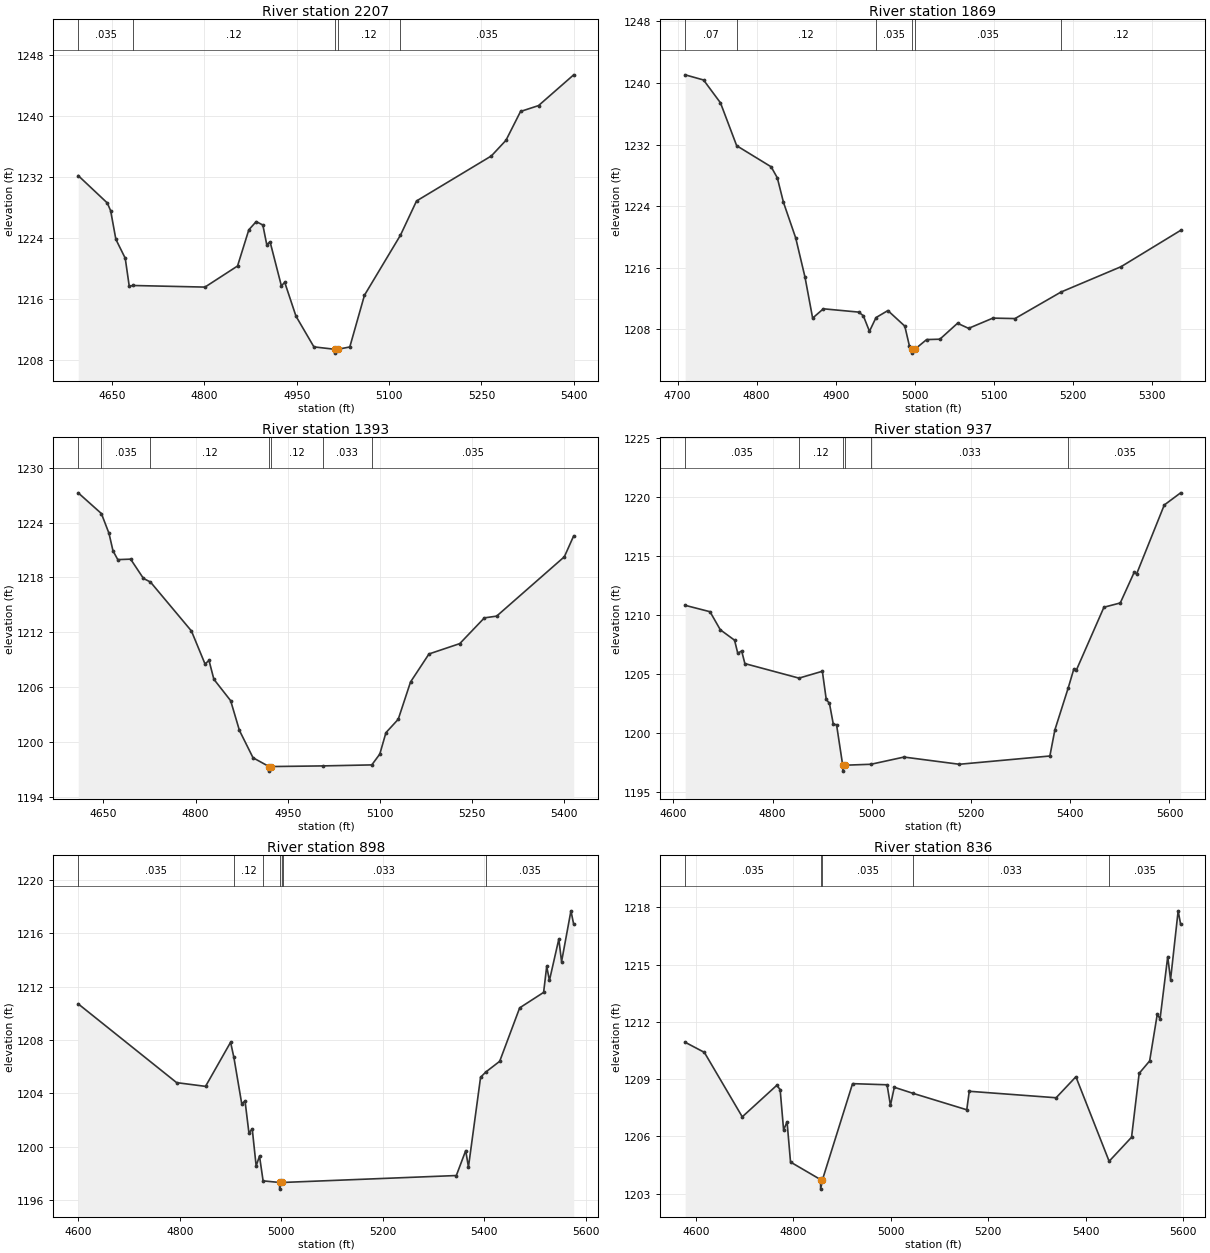
Type RM Length L Ch R = 1,2207,338,338,338
BEGIN DESCRIPTION:
Rebecca Tributary 9 5.0
END DESCRIPTION:
XS GIS Cut Line= 2
      2158611.40     13893319.24      2157869.84     13893006.78
#Sta/Elev= 30
  4595.1 1232.18  4642.3 1228.59  4647.8 1227.57  4656.3 1223.81  4671.5 1221.33
  4678.0 1217.66  4684.3 1217.75  4801.0 1217.54  4853.9 1220.31  4872.2 1225.06
  4884.2 1226.14  4895.0 1225.69  4901.3 1223.12  4906.7 1223.49  4925.1 1217.70
  4930.5 1218.17  4948.8 1213.72  4977.9 1209.69  5012.4 1209.37  5012.7 1208.87
  5016.4 1209.37  5036.2 1209.68  5060.0 1216.47  5118.5 1224.36  5144.6 1228.85
  5266.1 1234.76  5289.8 1236.81  5313.5 1240.60  5342.7 1241.37  5399.8 1245.41
#Mann=5,-1,0
  4595.1   0.035       0  4684.3    0.12       0  5012.4    0.05       0
  5016.4    0.12       0  5118.5   0.035       0
Bank Sta=5012.4,5016.4
Exp/Cntr=0.3,0.1

Type RM Length L Ch R = 1,1869,476,476,476
BEGIN DESCRIPTION:
Rebecca Tributary 9 4.0
END DESCRIPTION:
XS GIS Cut Line= 3
      2158724.98     13893124.99      2158475.00     13892975.00
      2158175.03     13892825.01
#Sta/Elev= 30
  4709.5 1241.06  4732.8 1240.39  4754.2 1237.42  4774.7 1231.85  4818.3 1229.11
  4826.1 1227.68  4833.9 1224.49  4849.4 1219.86  4861.1 1214.79  4870.8 1209.45
  4884.4 1210.66  4929.1 1210.23  4934.9 1209.76  4942.7 1207.74  4951.0 1209.52
  4966.0 1210.43  4987.4 1208.41  4993.2 1205.85  4996.1 1205.40  4996.4 1204.90
  5000.1 1205.40  5015.0 1206.66  5031.8 1206.71  5054.1 1208.78  5068.1 1208.12
  5098.9 1209.45  5126.8 1209.39  5185.1 1212.84  5261.0 1216.13  5336.4 1220.85
#Mann=6,-1,0
  4709.5    0.07       0  4774.7    0.12       0  4951.0   0.035       0
  4996.1   0.035       0  5000.1   0.035       0  5185.1    0.12       0
Bank Sta=4996.1,5000.1
Exp/Cntr=0.3,0.1

Type RM Length L Ch R = 1,1393,456,456,456
BEGIN DESCRIPTION:
Rebecca Tributary 9 3.0
END DESCRIPTION:
XS GIS Cut Line= 3
      2158825.01     13892825.01      2158525.00     13892575.00
      2158109.79     13892589.72
#Sta/Elev= 30
  4609.1 1227.24  4646.8 1224.98  4659.2 1222.82  4665.7 1220.91  4673.5 1219.95
  4694.4 1220.00  4715.2 1217.90  4726.7 1217.50  4793.3 1212.16  4815.4 1208.56
  4821.9 1208.94  4829.8 1206.89  4857.1 1204.55  4871.4 1201.30  4893.5 1198.32
  4919.5 1197.36  4919.8 1196.86  4923.5 1197.36  5006.9 1197.43  5086.7 1197.54
  5099.7 1198.72  5109.7 1201.06  5129.7 1202.52  5149.7 1206.59  5179.7 1209.65
  5229.8 1210.78  5269.8 1213.59  5289.8 1213.78  5399.9 1220.26  5415.1 1222.54
#Mann=7,-1,0
  4609.1    0.07       0  4646.8   0.035       0  4726.7    0.12       0
  4919.5    0.05       0  4923.5    0.12       0  5006.9   0.033       0
  5086.7   0.035       0
Bank Sta=4919.5,4923.5
Exp/Cntr=0.3,0.1

Type RM Length L Ch R = 1,937,39,39,39
BEGIN DESCRIPTION:
Rebecca Tributary 9 2.0
END DESCRIPTION:
XS GIS Cut Line= 3
      2159025.00     13892475.00      2158725.00     13892225.00
      2158124.99     13892325.00
#Sta/Elev= 30
  4623.7 1210.82  4673.8 1210.28  4694.6 1208.75  4723.3 1207.87  4729.8 1206.76
  4737.6 1206.96  4744.1 1205.89  4853.2 1204.66  4900.3 1205.24  4908.1 1202.86
  4914.6 1202.52  4922.4 1200.75  4928.9 1200.72  4941.3 1197.29  4941.5 1196.79
  4945.3 1197.29  4998.2 1197.37  5064.9 1197.98  5176.4 1197.37  5358.9 1198.07
  5369.0 1200.28  5396.1 1203.86  5407.1 1205.42  5412.1 1205.32  5467.9 1210.66
  5500.8 1211.02  5528.7 1213.60  5533.8 1213.48  5589.5 1219.31  5622.5 1220.34
#Mann=6,-1,0
  4623.7   0.035       0  4853.2    0.12       0  4941.3   0.033       0
  4945.3    0.12       0  4998.2   0.033       0  5396.1   0.035       0
Bank Sta=4941.3,4945.3
Exp/Cntr=0.3,0.1

Type RM Length L Ch R = 1,898,62,62,62
BEGIN DESCRIPTION:
Rebecca Tributary 9 1.3
END DESCRIPTION:
XS GIS Cut Line= 5
      2159049.89     13892464.44      2158747.51     13892201.66
      2158633.24     13892188.79      2158413.07     13892187.87
      2158190.16     13892280.09
#Sta/Elev= 30
  4599.4 1210.71  4793.5 1204.80  4850.5 1204.52  4899.9 1207.83  4906.4 1206.69
  4921.8 1203.23  4928.4 1203.42  4936.0 1201.04  4942.6 1201.32  4950.3 1198.55
  4956.9 1199.29  4964.0 1197.43  4996.4 1197.31  4996.6 1196.81  5000.4 1197.31
  5002.4 1197.31  5345.0 1197.83  5363.5 1199.70  5368.9 1198.47  5392.8 1205.20
  5402.9 1205.59  5430.5 1206.40  5469.9 1210.41  5517.1 1211.57  5523.2 1213.52
  5528.6 1212.47  5547.1 1215.57  5552.5 1213.87  5571.0 1217.69  5576.4 1216.68
#Mann=7,-1,0
  4599.4   0.035       0  4906.4    0.12       0  4964.0   0.035       0
  4996.4   0.035       0  5000.4   0.035       0  5002.4   0.033       0
  5402.9   0.035       0
Bank Sta=4996.4,5000.4
Exp/Cntr=0.3,0.1

Type RM Length L Ch R = 1,836,55,55,55
BEGIN DESCRIPTION:
Rebecca Tributary 9 1.2
END DESCRIPTION:
XS GIS Cut Line= 6
      2159082.85     13892462.86      2158823.87     13892206.93
      2158791.93     13892158.52      2158493.05     13892130.99
      2158380.28     13892151.33      2158225.58     13892242.58
#Sta/Elev= 30
  4577.9 1210.93  4617.3 1210.40  4695.1 1207.02  4765.8 1208.67  4772.8 1208.45
  4779.9 1206.33  4787.0 1206.76  4794.1 1204.65  4855.7 1203.73  4855.9 1203.23
  4859.7 1203.73  4921.4 1208.76  4992.2 1208.70  4999.1 1207.62  5007.0 1208.57
  5045.7 1208.25  5155.7 1207.39  5160.8 1208.36  5339.0 1208.02  5379.6 1209.12
  5447.8 1204.69  5493.8 1205.95  5509.4 1209.30  5530.9 1209.95  5546.5 1212.39
  5552.3 1212.16  5568.0 1215.42  5573.8 1214.21  5589.4 1217.82  5594.5 1217.11
#Mann=5,-1,0
  4577.9   0.035       0  4855.7   0.035       0  4859.7   0.035       0
  5045.7   0.033       0  5447.8   0.035       0
Bank Sta=4855.7,4859.7
Exp/Cntr=0.3,0.1

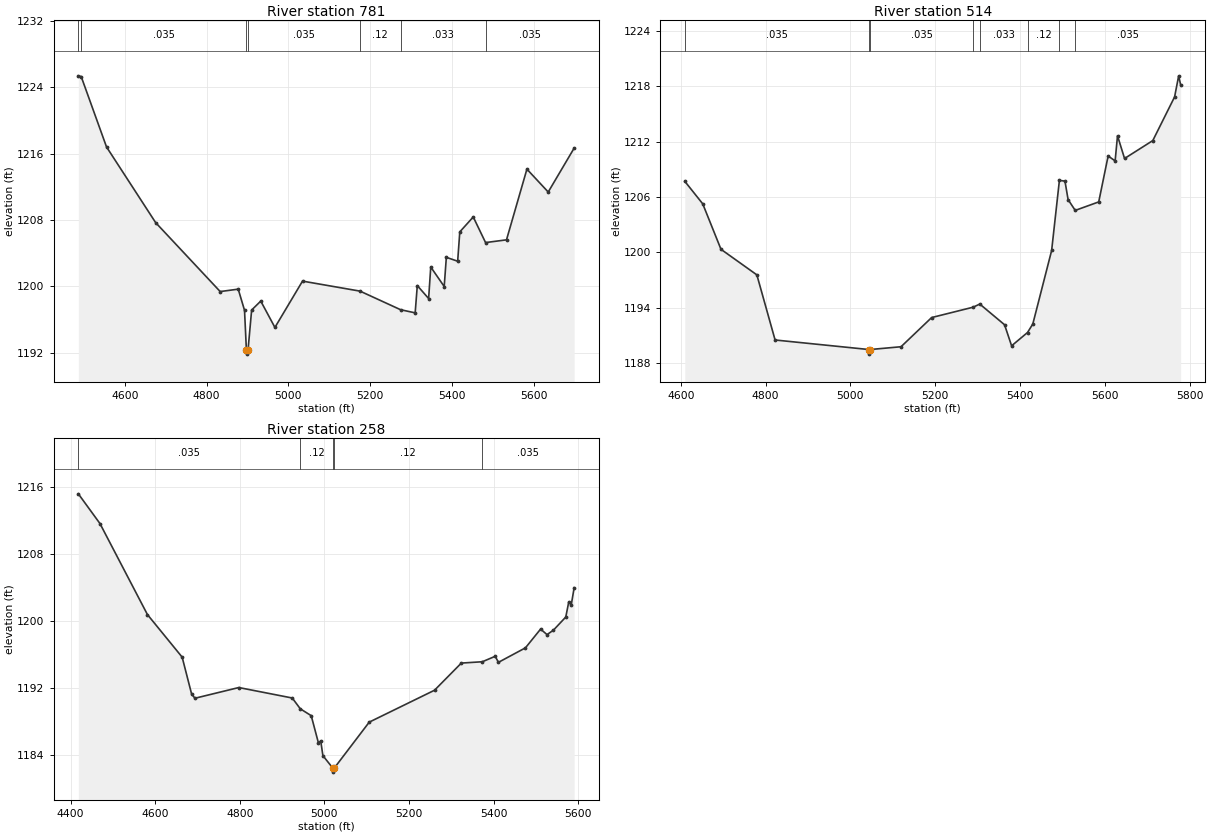
Type RM Length L Ch R = 1,781,267,267,267
BEGIN DESCRIPTION:
Rebecca Tributary 9 1.1
END DESCRIPTION:
XS GIS Cut Line= 5
      2159289.71     13892330.23      2158823.83     13892114.52
      2158550.48     13892079.22      2158319.61     13892149.34
      2158159.04     13892234.81
#Sta/Elev= 30
  4486.6 1225.39  4493.6 1225.30  4555.5 1216.81  4675.6 1207.68  4833.4 1199.36
  4877.5 1199.65  4892.9 1197.10  4897.5 1192.31  4897.8 1191.81  4901.5 1192.31
  4910.3 1197.13  4932.6 1198.21  4967.2 1195.03  5034.7 1200.62  5175.4 1199.41
  5274.4 1197.17  5310.1 1196.79  5315.3 1200.08  5343.0 1198.52  5348.2 1202.32
  5381.1 1199.97  5386.3 1203.49  5414.0 1203.02  5419.2 1206.56  5452.1 1208.36
  5482.2 1205.27  5533.4 1205.60  5583.3 1214.13  5635.4 1211.37  5698.8 1216.67
#Mann=7,-1,0
  4486.6   0.063       0  4493.6   0.035       0  4897.5   0.035       0
  4901.5   0.035       0  5175.4    0.12       0  5274.4   0.033       0
  5482.2   0.035       0
Bank Sta=4897.5,4901.5
Exp/Cntr=0.3,0.1

Type RM Length L Ch R = 1,514,256,256,256
BEGIN DESCRIPTION:
Rebecca Tributary 9 1.0
END DESCRIPTION:
XS GIS Cut Line= 3
      2159125.03     13892125.02      2158825.00     13891875.00
      2158132.37     13892230.32
#Sta/Elev= 30
  4609.5 1207.70  4651.8 1205.26  4694.8 1200.34  4779.4 1197.57  4822.4 1190.52
  5043.0 1189.49  5043.3 1188.99  5047.0 1189.49  5119.3 1189.79  5191.5 1192.95
  5289.2 1194.07  5305.0 1194.41  5363.4 1192.17  5380.0 1189.89  5417.5 1191.33
  5430.0 1192.25  5474.4 1200.21  5492.7 1207.80  5505.8 1207.72  5513.2 1205.72
  5530.0 1204.55  5585.4 1205.47  5607.6 1210.44  5624.1 1209.91  5629.7 1212.63
  5646.3 1210.17  5712.9 1212.11  5764.3 1216.84  5773.9 1219.12  5778.5 1218.15
#Mann=8,-1,0
  4609.5   0.035       0  5043.0   0.035       0  5047.0   0.035       0
  5289.2    0.12       0  5305.0   0.033       0  5417.5    0.12       0
  5492.7   0.033       0  5530.0   0.035       0
Bank Sta=5043,5047
Exp/Cntr=0.3,0.1

Type RM Length L Ch R = 1,258,0,0,0
BEGIN DESCRIPTION:
Rebecca Tributary 9 0.1
END DESCRIPTION:
XS GIS Cut Line= 3
      2159294.94     13891893.04      2158773.61     13891635.44
      2158278.36     13891956.30
#Sta/Elev= 30
  4418.5 1215.22  4469.6 1211.67  4581.8 1200.80  4663.8 1195.72  4686.1 1191.33
  4694.0 1190.81  4797.7 1192.09  4924.0 1190.84  4943.0 1189.55  4968.8 1188.73
  4985.7 1185.50  4991.3 1185.71  4996.4 1183.96  5019.5 1182.49  5019.7 1181.99
  5023.5 1182.49  5105.9 1187.96  5260.2 1191.77  5323.5 1195.01  5373.1 1195.17
  5403.5 1195.82  5411.2 1195.10  5475.0 1196.83  5510.8 1199.07  5526.0 1198.41
  5541.1 1198.94  5570.3 1200.51  5577.4 1202.33  5583.3 1201.98  5590.1 1204.01
#Mann=5,-1,0
  4418.5   0.035       0  4943.0    0.12       0  5019.5    0.05       0
  5023.5    0.12       0  5373.1   0.035       0
Bank Sta=5019.5,5023.5
Exp/Cntr=0.3,0.1

Chan Stop Cuts=-1