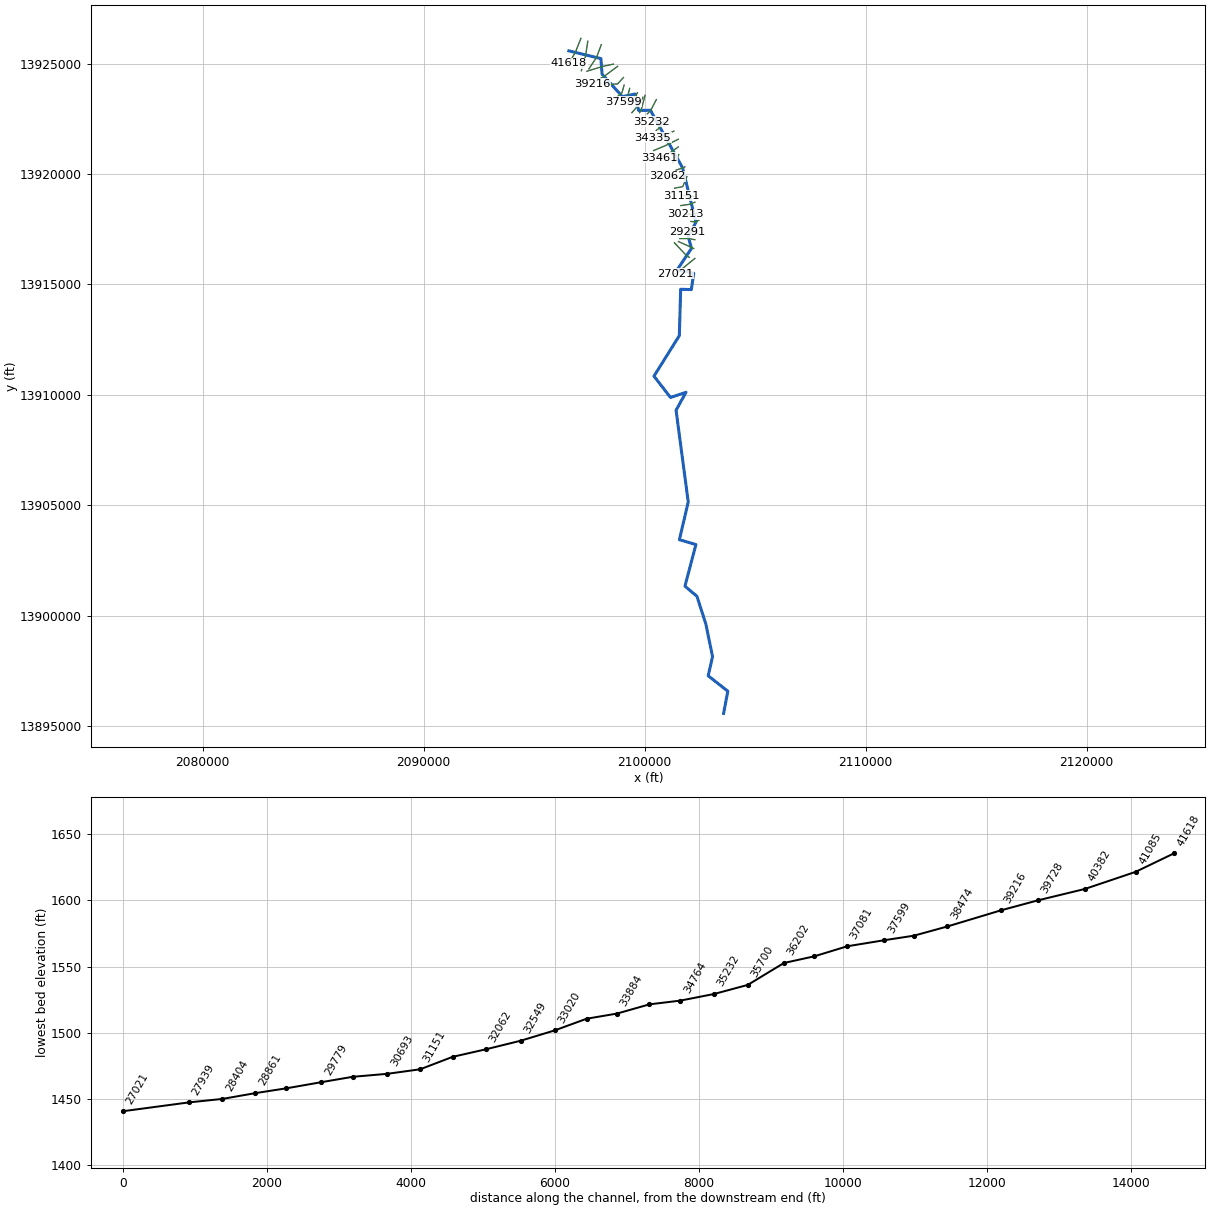
--- SHEPS CREEK.prj (project) ---

Proj Title=SHEPS CREEK Base Level Engineering
Current Plan=p01
Default Exp/Contr=0.3,0.1
English Units
Geom File=g01
Flow File=f01
Plan File=p01
Y Axis Title=Elevation
X Axis Title(PF)=Main Channel Distance
X Axis Title(XS)=Station
BEGIN DESCRIPTION:
SHEPS CREEK
END DESCRIPTION:
DSS Export Rating Curves= 0
DSS Export Rating Curve Sorted= 0
DSS Export Volume Flow Curves= 0
DXF OffsetX= 0
DXF OffsetY= 0
DXF ScaleX= 1
DXF ScaleY= 10

--- SHEPS CREEK.p01 (plan) ---

Plan Title=Multiple Run
Short Identifier=Multiple
Geom File=g01
Flow File=f01
Subcritical Flow
K Sum by GR= 0
Std Step Tol= 0.01
Critical Tol= 0.01
Num of Std Step Trials= 20
Max Error Tol= 0.3
Flow Tol Ratio= 0.001
Split Flow NTrial= 30
Split Flow Tol= 0.02
Split Flow Ratio= 0.02
Log Output Level= 0
Friction Slope Method= 1
Unsteady Friction Slope Method= 2
Unsteady Bridges Friction Slope Method= 1
Parabolic Critical Depth
Global Vel Dist=  1 , 1 , 1
Global Log Level= 0
CheckData=True
Encroach Param= -1, 0, 0, 0
BEGIN DESCRIPTION:
Multiple Run
END DESCRIPTION:

--- SHEPS CREEK.f01 (steady flow) ---

Flow Title=Multiple
Number of Profiles=7
Profile Names=10-year,25-year,50-year,1pct_min,100-year,1pct_plu,500-year
River Rch & RM= SHEPS CREEK,Reach-1,41618
    1367    2392    3401    2347    4683    9344    8803
River Rch & RM= SHEPS CREEK,Reach-1,38007
    2004    3557    5103    3547    7077   14120   13501
River Rch & RM= SHEPS CREEK,Reach-1,31151
    2433    4355    6283    4389    8757   17472   16874
River Rch & RM= SHEPS CREEK,Reach-1,29291
    2620    4706    6805    4763    9504   18962   18389
River Rch & RM= SHEPS CREEK,Reach-1,28861
    2793    5016    7252    5072   10121   20193   19557
River Rch & RM= SHEPS CREEK,Reach-1,25214
    2972    5332    7703    5380   10734   21417   20685
River Rch & RM= SHEPS CREEK,Reach-1,19734
    3760    6790    9848    6893   13753   27442   26576
River Rch & RM= SHEPS CREEK,Reach-1,17050
    4304    7780   11292    7906   15775   31475   30491
River Rch & RM= SHEPS CREEK,Reach-1,13791
    4610    8336   12100    8469   16899   33718   32645
River Rch & RM= SHEPS CREEK,Reach-1,7744
    4869    8797   12763    8925   17807   35530   34333
Boundary for River Rch & Prof#=SHEPS CREEK,Reach-1,1
Up Type=0
Dn Type=3
Dn Slope=0.005
Boundary for River Rch & Prof#=SHEPS CREEK,Reach-1,2
Up Type=0
Dn Type=3
Dn Slope=0.005
Boundary for River Rch & Prof#=SHEPS CREEK,Reach-1,3
Up Type=0
Dn Type=3
Dn Slope=0.005
Boundary for River Rch & Prof#=SHEPS CREEK,Reach-1,4
Up Type=0
Dn Type=3
Dn Slope=0.005
Boundary for River Rch & Prof#=SHEPS CREEK,Reach-1,5
Up Type=0
Dn Type=3
Dn Slope=0.005
Boundary for River Rch & Prof#=SHEPS CREEK,Reach-1,6
Up Type=0
Dn Type=3
Dn Slope=0.005
Boundary for River Rch & Prof#=SHEPS CREEK,Reach-1,7
Up Type=0
Dn Type=3
Dn Slope=0.005

--- SHEPS CREEK.g01 (geometry) ---

Geom Title=Existing Conditions
Program Version=4.10

River Reach=SHEPS CREEK     ,Reach-1
Reach XY= 30
        2096575.       13925575.        2098025.       13925225.
        2098075.       13924525.      2098994.44     13923504.45
      2099573.54     13923621.48        2099730.     13922879.99
      2100264.61     13922885.11      2101721.54      13920273.5
      2102323.79     13917815.41      2101976.06     13917165.37
      2102121.25     13916626.55      2101476.04     13915664.56
      2102225.37      13915504.8      2102114.66     13914764.87
      2101632.79     13914778.45      2101572.76     13912680.93
      2100425.05     13910845.02      2101172.57     13909880.52
      2101873.97     13910114.57      2101424.76     13909302.46
      2101975.28     13905147.85      2101575.52     13903440.22
      2102323.02     13903219.33      2101826.21     13901334.59
      2102369.55     13900877.47      2102772.94     13899619.14
      2103075.51     13898147.76      2102878.75     13897276.55
      2103766.77     13896578.23        2103575.       13895575.

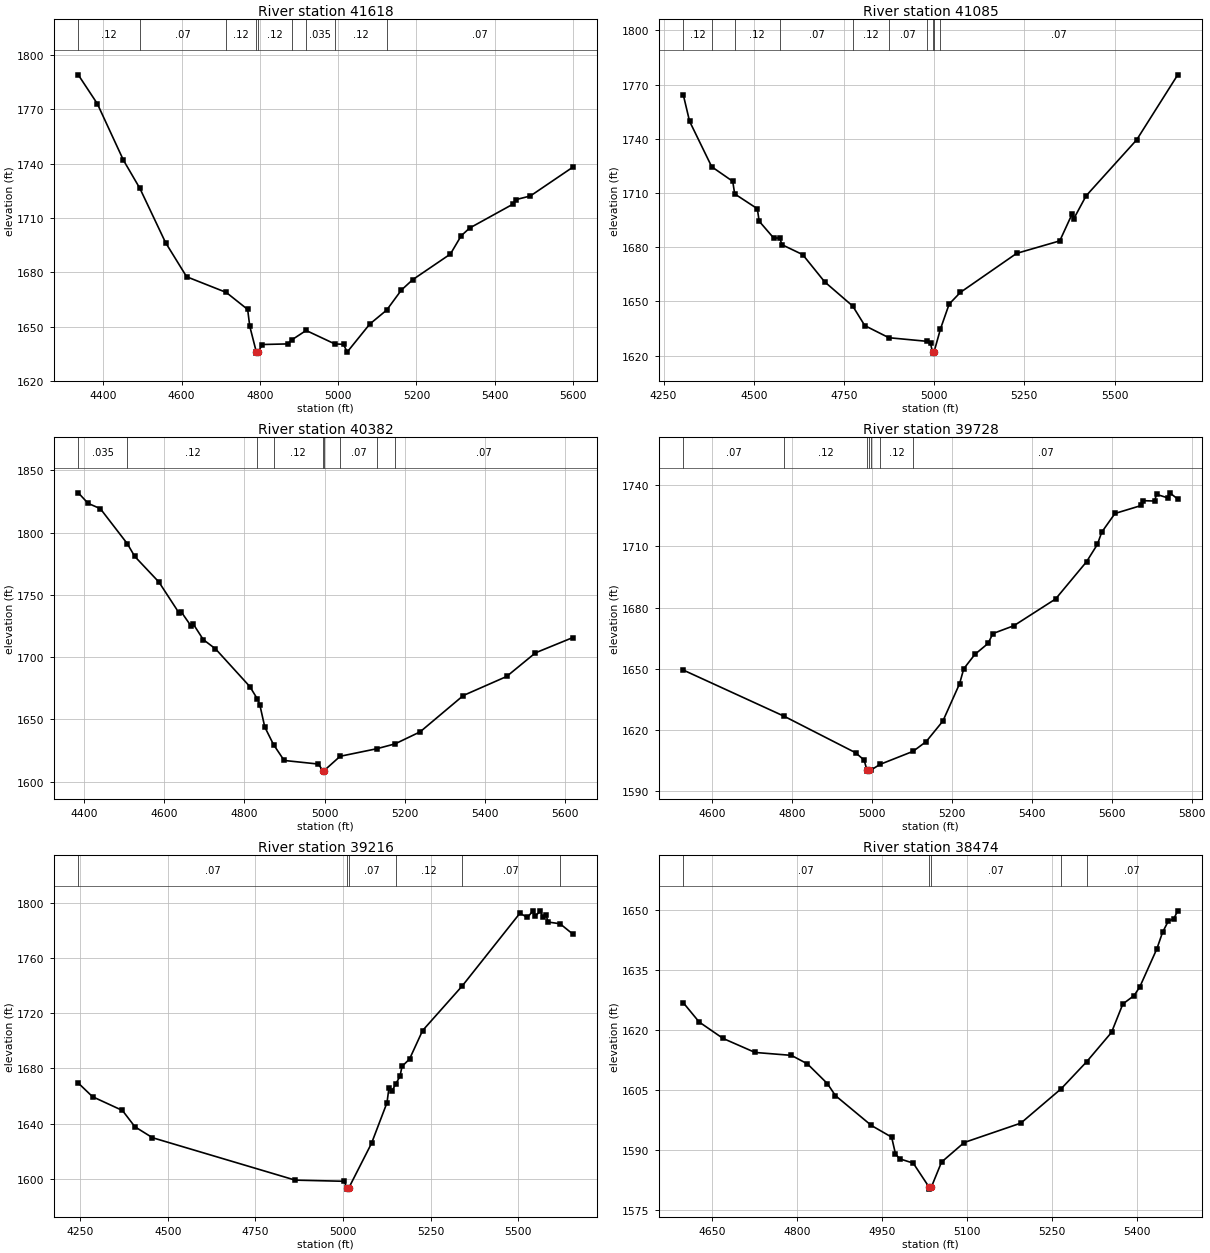
Type RM Length L Ch R = 1 ,41618   ,533,533,533
BEGIN DESCRIPTION:
SHEPS CREEK 78.0
END DESCRIPTION:
XS GIS Cut Line= 3
      2097119.02     13926142.43        2096875.       13925525.
      2096576.51     13925005.32
#Sta/Elev= 30
  4336.1 1789.07  4384.8  1773.1  4451.6 1741.87  4493.6 1726.31  4559.1  1696.4
  4612.9 1677.54  4714.1 1668.89  4768.8 1659.48  4774.2 1650.21  4791.1 1635.85
  4791.4 1635.35  4795.1 1635.85  4806.5 1640.11    4871 1640.44  4882.2 1642.76
  4918.2 1647.87  4991.2 1640.46  5013.7 1640.19  5023.1 1635.95  5080.7 1651.38
    5124 1659.13  5161.5 1670.18  5190.5 1675.93  5286.8 1690.08  5314.2 1700.13
  5335.7 1704.41  5447.9  1717.8  5453.6 1720.11    5491 1722.15  5599.3 1738.03
#Mann= 9 ,-1 , 0
  4336.1     .12       0  4493.6     .07       0  4714.1     .12       0
  4791.1     .05       0  4795.1     .12       0  4882.2     .07       0
  4918.2    .035       0  4991.2     .12       0    5124     .07       0
Bank Sta=4791.1,4795.1
XS Rating Curve= 0 ,0
Exp/Cntr=0.3,0.1

Type RM Length L Ch R = 1 ,41085   ,703,703,703
BEGIN DESCRIPTION:
SHEPS CREEK 77.0
END DESCRIPTION:
XS GIS Cut Line= 3
      2097431.54     13926012.29        2097325.       13925325.
      2097140.73     13924675.43
#Sta/Elev= 30
  4304.5  1764.4    4322 1749.68  4383.4 1724.51  4441.7 1716.44    4447 1709.51
  4509.8 1701.29  4514.9  1694.4  4554.7 1685.18  4572.3    1685  4577.9 1681.42
  4635.7 1675.88  4696.4 1660.86  4774.4 1647.41  4807.7 1636.63  4874.4 1629.93
  4980.3 1627.93  4989.9 1626.84  4995.5  1621.9  4995.7  1621.4  4999.5  1621.9
  5017.5 1634.78  5041.6 1648.54  5072.8 1655.02  5228.7  1676.6  5348.2  1683.5
  5382.1 1698.24  5387.3 1695.83  5421.2 1708.43  5561.3 1739.38  5675.2 1775.37
#Mann= 10 ,-1 , 0
  4304.5     .12       0  4383.4     .07       0    4447     .12       0
  4572.3     .07       0  4774.4     .12       0  4874.4     .07       0
  4980.3     .12       0  4995.5     .05       0  4999.5     .12       0
  5017.5     .07       0
Bank Sta=4995.5,4999.5
XS Rating Curve= 0 ,0
Exp/Cntr=0.3,0.1

Type RM Length L Ch R = 1 ,40382   ,654,654,654
BEGIN DESCRIPTION:
SHEPS CREEK 76.0
END DESCRIPTION:
XS GIS Cut Line= 3
      2098039.19     13925851.71        2097825.       13925275.
      2097480.34     13924759.51
#Sta/Elev= 30
  4384.8 1831.98  4409.6 1823.49  4439.9 1819.27  4507.5 1791.07  4525.7 1780.99
  4586.4 1760.29  4636.5 1735.56  4641.8 1736.48  4666.8 1724.94  4672.2 1726.57
  4697.2 1714.09  4727.6 1706.72  4813.3 1676.46  4832.3 1666.47  4838.3 1661.87
  4850.7 1643.98  4872.6 1629.85  4899.1  1617.1  4984.8  1614.2  4995.3 1609.03
  4995.6 1608.53  4999.3 1609.03    5039 1620.45  5130.4  1626.5  5176.2 1630.41
  5238.7 1640.04  5346.8 1669.25  5454.9 1684.52    5527 1703.51  5620.1 1715.74
#Mann= 9 ,-1 , 0
  4384.8    .035       0  4507.5     .12       0  4832.3     .07       0
  4872.6     .12       0  4995.3     .05       0  4999.3     .12       0
    5039     .07       0  5130.4     .12       0  5176.2     .07       0
Bank Sta=4995.3,4999.3
XS Rating Curve= 0 ,0
Exp/Cntr=0.3,0.1

Type RM Length L Ch R = 1 ,39728   ,512,512,512
BEGIN DESCRIPTION:
SHEPS CREEK 75.0
END DESCRIPTION:
XS GIS Cut Line= 3
      2098586.09     13924974.94        2098125.       13924875.
      2097392.48     13924653.76
#Sta/Elev= 30
  4528.2 1649.42  4780.2 1626.83  4959.1 1608.94  4980.5 1605.37  4987.8 1600.41
    4988 1599.91  4991.8 1600.41  4999.1  1600.6  5020.5 1603.21    5103  1609.6
  5135.8 1614.36  5177.6  1624.4  5219.4 1642.69  5229.9 1650.05  5257.7 1657.08
  5290.6 1662.44  5302.9  1667.3  5355.2 1671.13  5459.6 1684.23    5537 1702.45
  5564.1 1710.94  5575.2 1716.99  5608.2 1726.12  5674.1 1730.03  5679.3 1732.38
  5707.1 1732.21  5712.3 1735.46    5740 1733.78  5745.3 1736.23  5765.2 1733.19
#Mann= 7 ,-1 , 0
  4528.2     .07       0  4780.2     .12       0  4987.8     .05       0
  4991.8     .12       0  4999.1     .07       0  5020.5     .12       0
    5103     .07       0
Bank Sta=4987.8,4991.8
XS Rating Curve= 0 ,0
Exp/Cntr=0.3,0.1

Type RM Length L Ch R = 1 ,39216   ,742,742,742
BEGIN DESCRIPTION:
SHEPS CREEK 74.0
END DESCRIPTION:
XS GIS Cut Line= 3
      2098781.39     13924875.13        2098175.       13924425.
      2097609.77     13924094.03
#Sta/Elev= 30
  4244.8 1669.42  4285.4 1659.52  4370.8  1649.5  4406.4 1637.66  4456.5 1629.73
  4863.3 1598.94  5002.9 1598.09  5011.6  1592.9  5011.9  1592.4  5015.6  1592.9
  5081.1 1625.63  5125.2 1655.11    5131  1666.1  5139.1 1663.39    5150 1668.69
  5162.2 1674.21  5168.1 1681.49  5189.6 1686.88  5226.8 1707.53  5339.6 1739.85
  5504.4 1792.74  5525.9 1789.63  5541.5 1794.46  5547.3 1790.42    5563 1794.34
  5568.8 1789.91  5578.7 1791.63  5584.5 1786.33  5618.8 1785.07    5655 1777.62
#Mann= 6 ,-1 , 0
  4244.8     .07       0  5011.6     .05       0  5015.6     .07       0
    5150     .12       0  5339.6     .07       0  5618.8     .12       0
Bank Sta=5011.6,5015.6
XS Rating Curve= 0 ,0
Exp/Cntr=0.3,0.1

Type RM Length L Ch R = 1 ,38474   ,467,467,467
BEGIN DESCRIPTION:
SHEPS CREEK 73.0
END DESCRIPTION:
XS GIS Cut Line= 3
      2099042.58     13924366.76        2098775.       13924075.
      2098298.16     13924066.33
#Sta/Elev= 30
  4599.4 1626.77  4627.5 1621.95  4669.6 1617.86  4726.1 1614.36  4790.3 1613.63
  4818.6  1611.5  4853.8 1606.59    4868 1603.59  4931.5 1596.14  4967.2 1593.23
    4974 1589.05  4981.4 1587.82  5005.3 1586.75  5033.3 1580.76  5033.5 1580.26
  5037.3 1580.76  5055.3 1587.01  5095.3 1591.89  5195.3 1596.73  5266.3 1605.28
  5311.2    1612  5355.3 1619.36  5375.3 1626.45  5395.3 1628.56  5405.3 1630.73
  5435.4 1640.22  5445.4 1644.33  5455.4 1647.08  5465.4 1647.75  5472.2 1649.69
#Mann= 5 ,-1 , 0
  4599.4     .07       0  5033.3     .05       0  5037.3     .07       0
  5266.3    .035       0  5311.2     .07       0
Bank Sta=5033.3,5037.3
XS Rating Curve= 0 ,0
Exp/Cntr=0.3,0.1

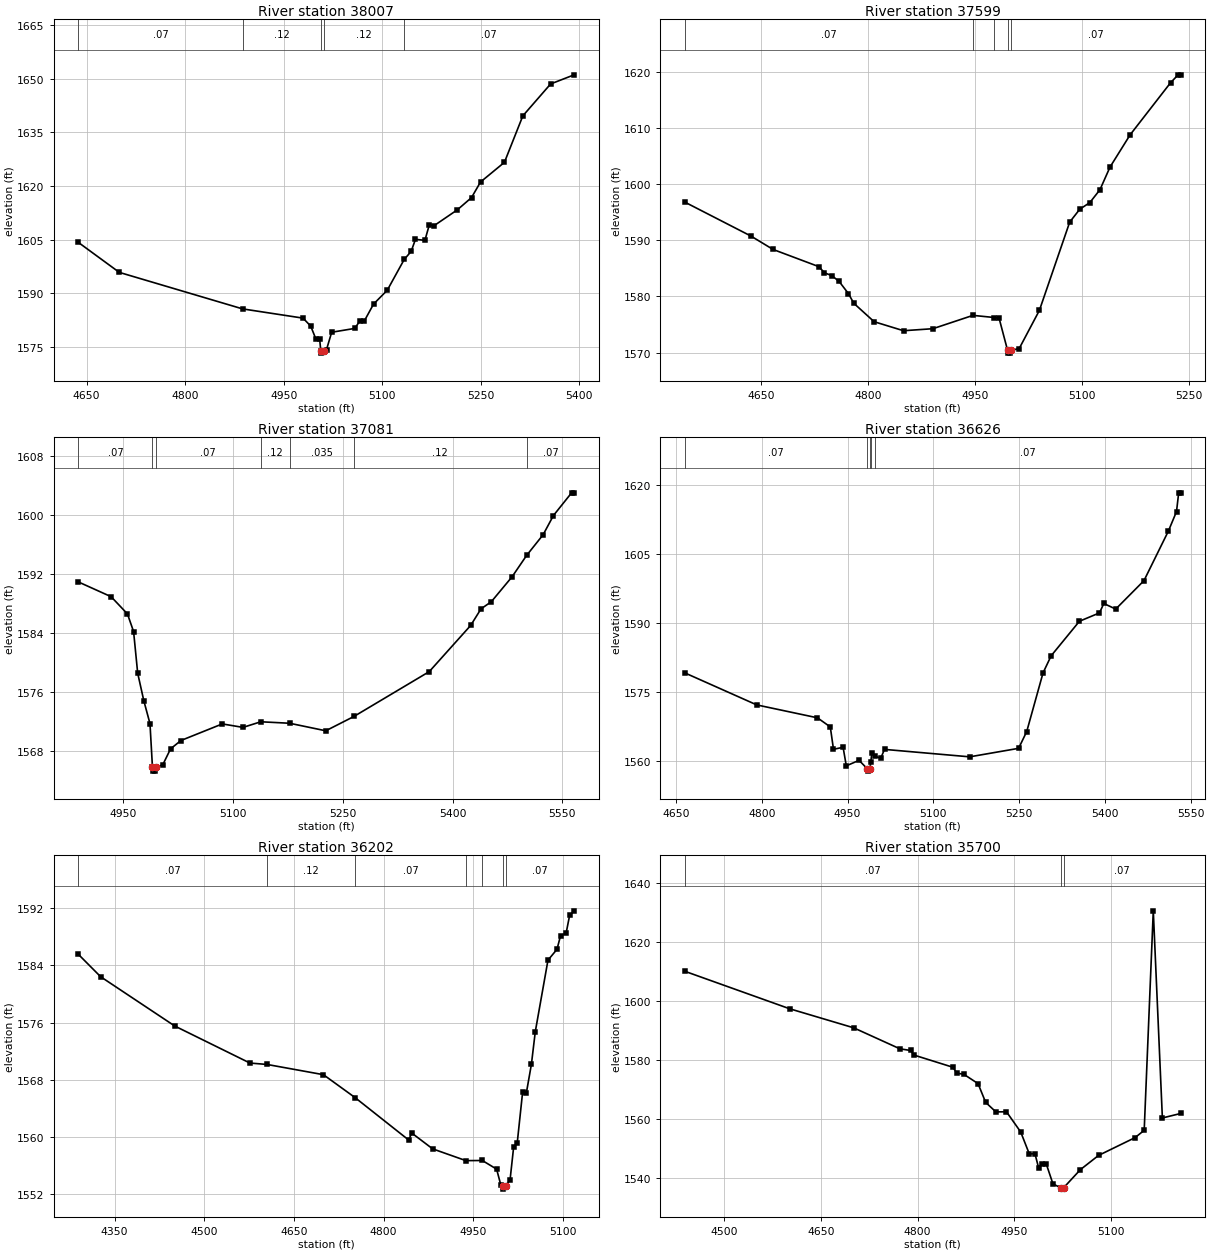
Type RM Length L Ch R = 1 ,38007   ,408,408,408
BEGIN DESCRIPTION:
SHEPS CREEK 72.0
END DESCRIPTION:
XS GIS Cut Line= 3
        2099075.     13924024.99        2098975.       13923675.
        2098675.       13923425.
#Sta/Elev= 30
  4637.5 1604.24  4699.9 1595.85  4887.5 1585.64  4979.4 1583.06  4991.1 1580.84
  4998.9 1577.25  5004.7 1577.25  5006.5 1573.77  5006.8 1573.27  5010.7 1573.77
  5015.2 1574.28    5023 1579.11  5058.1 1580.18  5065.9 1582.25  5072.4 1582.17
  5086.8    1587  5107.6 1590.86  5133.4 1599.47    5144 1601.74  5150.5  1605.1
  5164.9 1604.81  5171.4 1609.05  5179.2 1608.96  5214.3 1613.36  5235.8 1616.77
  5249.5 1621.13  5285.9 1626.64  5313.9 1639.63  5356.2 1648.56    5392 1651.11
#Mann= 5 ,-1 , 0
  4637.5     .07       0  4887.5     .12       0  5006.5     .05       0
  5010.7     .12       0  5133.4     .07       0
Bank Sta=5006.5,5010.7
XS Rating Curve= 0 ,0
Exp/Cntr=0.3,0.1

Type RM Length L Ch R = 1 ,37599   ,518,518,518
BEGIN DESCRIPTION:
SHEPS CREEK 71.0
END DESCRIPTION:
XS GIS Cut Line= 3
      2099324.99     13923874.96        2099225.       13923475.
      2099025.01     13923275.01
#Sta/Elev= 30
  4542.9 1596.85  4635.6 1590.79  4666.6  1588.4    4731 1585.32  4738.7 1584.22
    4749 1583.73  4759.3 1582.68  4772.2 1580.53  4779.9 1578.78  4808.3  1575.5
  4849.5 1573.89  4890.7 1574.25  4946.9 1576.63  4976.6 1576.25  4983.5 1576.13
  4995.4 1570.39  4995.7 1569.89  4999.4 1569.89  4999.7 1570.39  5011.7 1570.71
    5040 1577.52  5082.5 1593.28  5096.6 1595.58  5110.7 1596.76  5124.9 1599.06
    5139  1603.1  5167.3 1608.88  5223.9 1618.16  5234.5 1619.57    5238 1619.57
#Mann= 5 ,-1 , 0
  4542.9     .07       0  4946.9     .12       0  4976.6     .07       0
  4995.4     .05       0  4999.7     .07       0
Bank Sta=4995.4,4999.7
XS Rating Curve= 0 ,0
Exp/Cntr=0.3,0.1

Type RM Length L Ch R = 1 ,37081   ,455,455,455
BEGIN DESCRIPTION:
SHEPS CREEK 70.0
END DESCRIPTION:
XS GIS Cut Line= 3
      2099675.01     13923675.03        2099625.       13923575.
      2099225.01     13923175.01
#Sta/Elev= 30
  4888.7 1590.89  4933.5 1588.89  4955.8 1586.56  4964.2 1584.17  4969.8 1578.54
  4978.2  1574.8  4986.6 1571.71    4990 1565.78  4990.3 1565.28    4994 1565.28
  4994.3 1565.78  5004.1 1566.14  5014.7 1568.29  5028.8 1569.42  5085.4 1571.67
  5113.7  1571.2    5138 1571.96  5177.4 1571.76  5226.8 1570.74  5265.3 1572.68
  5368.2 1578.75  5424.8    1585  5438.9 1587.24  5453.1 1588.22  5481.4 1591.59
  5501.4  1594.5  5523.8 1597.28  5537.9 1599.88  5562.7 1602.95  5566.2 1602.95
#Mann= 7 ,-1 , 0
  4888.7     .07       0    4990     .05       0  4994.3     .07       0
    5138     .12       0  5177.4    .035       0  5265.3     .12       0
  5501.4     .07       0
Bank Sta=4990,4994.3
XS Rating Curve= 0 ,0
Exp/Cntr=0.3,0.1

Type RM Length L Ch R = 1 ,36626   ,424,424,424
BEGIN DESCRIPTION:
SHEPS CREEK 69.0
END DESCRIPTION:
XS GIS Cut Line= 3
      2099925.02     13923475.04        2099775.       13923175.
      2099424.98     13922774.97
#Sta/Elev= 30
  4665.4 1579.12  4791.2 1572.15  4897.4 1569.34  4919.8 1567.36  4925.4 1562.49
  4942.2 1562.93  4947.8 1558.89  4970.1 1560.09  4984.6 1558.24    4985 1557.74
  4989.1 1558.24  4990.5 1559.64  4992.5 1561.65  4998.5 1560.95    5008 1560.55
  5014.6 1562.47  5163.6 1560.85  5249.1  1562.7  5263.3 1566.36  5291.8 1579.11
    5306 1582.84  5355.4 1590.35  5390.5 1592.17  5398.1 1594.22  5418.9    1593
  5468.3 1599.19    5511 1609.98  5525.2 1614.22    5529  1618.3  5532.4  1618.3
#Mann= 5 ,-1 , 0
  4665.4     .07       0  4984.6     .05       0  4989.1     .07       0
  4990.5    .035       0  4998.5     .07       0
Bank Sta=4984.6,4989.1
XS Rating Curve= 0 ,0
Exp/Cntr=0.3,0.1

Type RM Length L Ch R = 1 ,36202   ,502,502,502
BEGIN DESCRIPTION:
SHEPS CREEK 68.0
END DESCRIPTION:
XS GIS Cut Line= 3
      2100022.84     13923561.09      2099840.55      13922876.2
        2099775.       13922775.
#Sta/Elev= 30
  4289.3 1585.56  4326.6 1582.42  4450.7 1575.51  4576.3 1570.33  4605.1 1570.13
  4699.2  1568.7    4752  1565.5  4841.8 1559.55  4846.9 1560.53  4881.9 1558.31
  4937.6 1556.66    4965 1556.68  4988.9 1555.47  4996.1  1553.2    5000 1553.17
  5000.3 1552.67  5004.5 1553.17  5011.4 1553.97  5017.4 1558.57  5023.3 1559.08
  5032.5 1566.34  5038.5 1566.07  5047.1 1570.16  5053.6 1574.73  5074.8 1584.74
  5089.9 1586.26  5095.9 1588.19  5105.1  1588.5    5111 1591.01  5118.6 1591.65
#Mann= 7 ,-1 , 0
  4289.3     .07       0  4605.1     .12       0    4752     .07       0
  4937.6    .035       0    4965     .07       0    5000     .05       0
  5004.5     .07       0
Bank Sta=5000,5004.5
XS Rating Curve= 0 ,0
Exp/Cntr=0.3,0.1

Type RM Length L Ch R = 1 ,35700   ,468,468,468
BEGIN DESCRIPTION:
SHEPS CREEK 67.0
END DESCRIPTION:
XS GIS Cut Line= 3
      2100533.26     13923368.39        2100275.       13922875.
      2100125.02     13922725.02
#Sta/Elev= 30
  4438.9 1610.09  4601.6 1597.36  4700.7 1590.91  4772.5 1583.77    4789 1583.21
  4794.6 1581.63  4854.7 1577.51  4860.8 1575.51  4871.6 1575.13  4893.7 1571.96
  4905.5  1565.6  4921.4 1562.35  4937.8  1562.4  4959.9 1555.53  4973.2 1548.09
  4981.9  1548.2  4987.6 1543.42    4993 1544.83  4999.3 1544.83  5009.9 1537.91
  5021.6 1536.64    5022 1536.14  5026.6 1536.64  5052.4 1542.75  5080.6 1547.58
  5137.2 1553.62  5151.4  1556.1  5165.5 1630.61  5179.6 1560.29  5207.9 1561.82
#Mann= 3 ,-1 , 0
  4438.9     .07       0  5021.6     .05       0  5026.6     .07       0
Bank Sta=5021.6,5026.6
XS Rating Curve= 0 ,0
Exp/Cntr=0.3,0.1

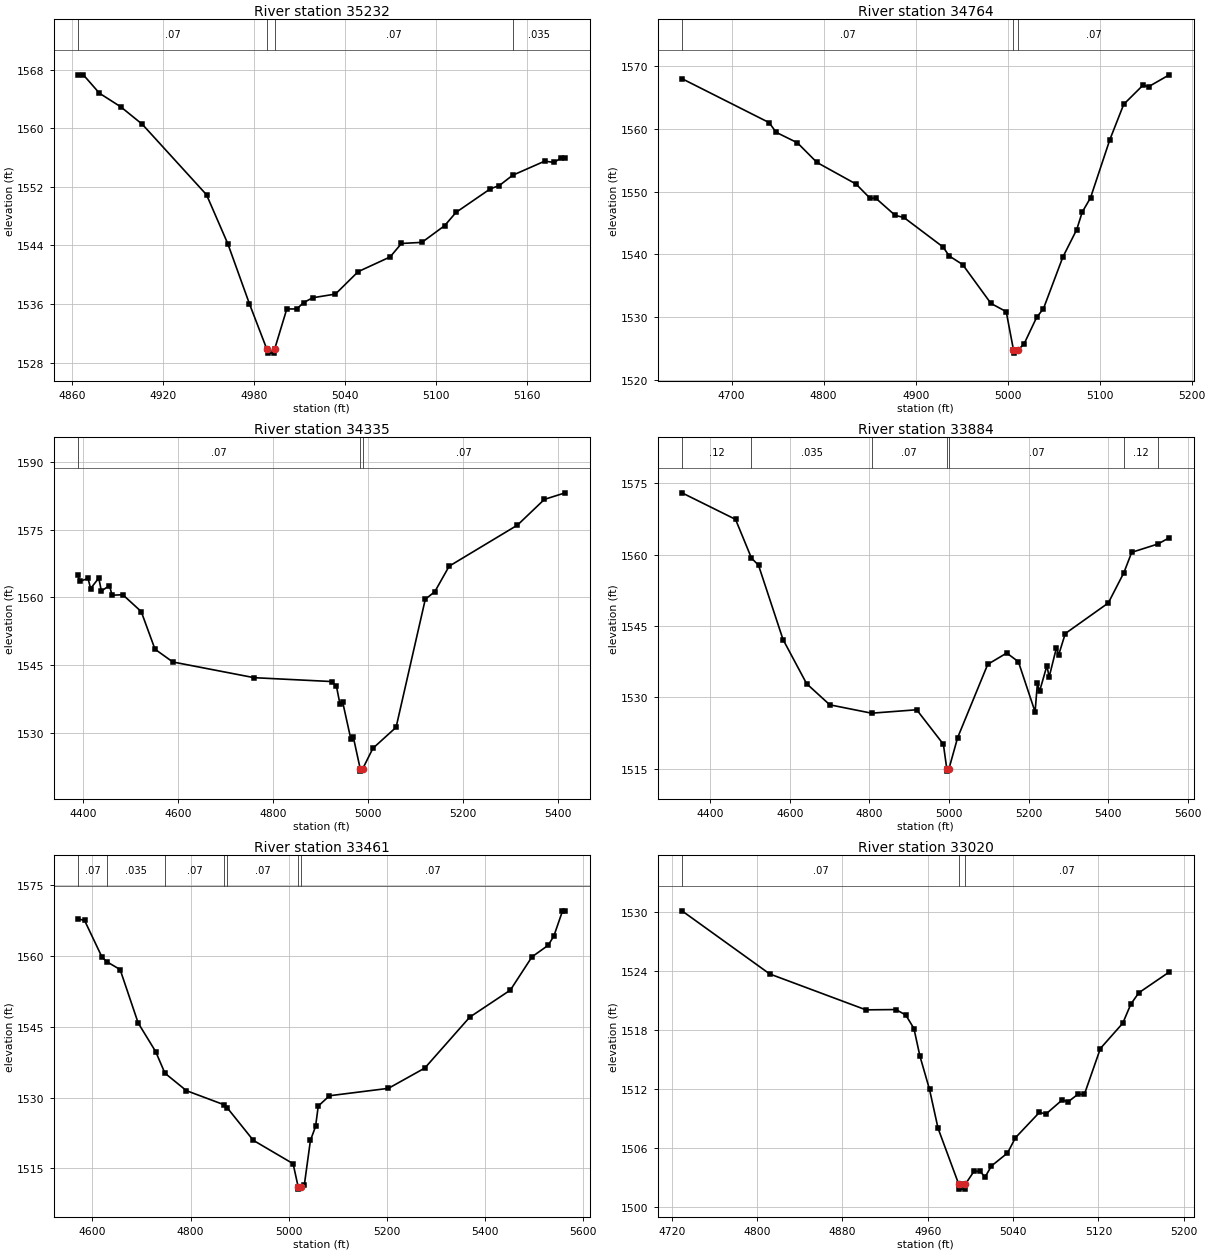
Type RM Length L Ch R = 1 ,35232   ,468,468,468
BEGIN DESCRIPTION:
SHEPS CREEK 66.0
END DESCRIPTION:
XS GIS Cut Line= 3
      2100575.03     13922575.03        2100475.       13922475.
      2100325.04     13922375.03
#Sta/Elev= 30
  4863.6 1567.28  4867.2 1567.28  4877.8 1564.77  4891.9 1562.91  4906.1 1560.53
  4948.5 1550.91  4962.6  1544.2  4976.8 1536.04  4988.4 1529.79  4988.8 1529.29
  4993.1 1529.29  4993.4 1529.79  5001.5 1535.32  5008.1 1535.32  5012.6 1536.19
  5018.6 1536.85  5033.6 1537.35  5048.6 1540.41  5069.7 1542.42  5077.2 1544.26
  5090.7 1544.41  5105.7 1546.69  5113.2  1548.5  5135.8 1551.71  5141.8 1552.17
  5150.6 1553.57  5171.8  1555.5  5177.8 1555.32  5182.3 1555.89  5185.3 1555.89
#Mann= 4 ,-1 , 0
  4863.6     .07       0  4988.4     .05       0  4993.4     .07       0
  5150.6    .035       0
Bank Sta=4988.4,4993.4
XS Rating Curve= 0 ,0
Exp/Cntr=0.3,0.1

Type RM Length L Ch R = 1 ,34764   ,429,429,429
BEGIN DESCRIPTION:
SHEPS CREEK 65.0
END DESCRIPTION:
XS GIS Cut Line= 3
      2100858.84     13922372.06        2100675.       13922075.
      2100525.02     13921975.02
#Sta/Elev= 30
    4646 1567.97  4740.7 1560.98  4748.4 1559.43  4771.4 1557.77  4792.7 1554.64
  4835.2  1551.2  4850.6 1548.91  4856.5 1548.97  4877.7 1546.22  4887.2 1545.88
  4929.8 1541.18  4936.5 1539.75    4951  1538.4  4981.8 1532.21  4998.4  1530.9
  5006.3  1524.8  5006.7  1524.3  5011.4  1524.8  5017.9  1525.8  5031.4 1529.97
  5038.9 1531.39  5059.9 1539.57    5075 1543.95    5081 1546.74    5090 1549.01
    5111 1558.26  5126.1 1563.89  5147.1 1566.94  5153.1 1566.69  5175.6 1568.58
#Mann= 3 ,-1 , 0
    4646     .07       0  5006.3     .05       0  5011.4     .07       0
Bank Sta=5006.3,5011.4
XS Rating Curve= 0 ,0
Exp/Cntr=0.3,0.1

Type RM Length L Ch R = 1 ,34335   ,451,451,451
BEGIN DESCRIPTION:
SHEPS CREEK 64.0
END DESCRIPTION:
XS GIS Cut Line= 3
      2101324.94     13921941.31        2100775.       13921675.
      2100361.36     13921641.82
#Sta/Elev= 30
  4388.9 1564.86  4393.1 1563.57  4410.2  1564.2  4415.7 1561.97  4432.8 1564.29
  4438.3 1561.42  4455.3 1562.62  4460.9 1560.49  4483.5 1560.59  4522.2 1556.86
  4551.2 1548.51  4588.8 1545.68    4760  1542.2  4923.7 1541.34  4933.3 1540.26
  4940.7 1536.31  4946.2 1536.86  4963.3 1528.69  4968.8 1529.01  4983.3 1521.98
  4983.7 1521.48  4988.4 1521.98    5010 1526.54  5058.8  1531.2  5120.3 1559.59
  5140.4 1561.28  5170.5 1566.92  5314.3 1576.03  5371.1 1581.74  5414.9 1583.19
#Mann= 3 ,-1 , 0
  4388.9     .07       0  4983.3     .05       0  4988.4     .07       0
Bank Sta=4983.3,4988.4
XS Rating Curve= 0 ,0
Exp/Cntr=0.3,0.1

Type RM Length L Ch R = 1 ,33884   ,423,423,423
BEGIN DESCRIPTION:
SHEPS CREEK 63.0
END DESCRIPTION:
XS GIS Cut Line= 3
      2101525.45     13921574.11        2100925.       13921275.
      2100413.45     13921063.69
#Sta/Elev= 30
  4329.2 1573.03  4463.8 1567.45  4503.9 1559.29  4521.5 1557.82  4583.1 1542.19
  4642.5 1532.89  4700.6 1528.46  4805.7  1526.7  4918.9 1527.42    4986 1520.17
  4994.5 1515.02  4994.9 1514.52    5000 1515.02  5021.7 1521.54  5097.4 1536.97
  5145.1 1539.35  5174.4 1537.53  5216.4 1526.97  5222.2 1532.98  5227.7 1531.32
  5246.2 1536.71  5251.6 1534.26  5270.1 1540.49  5275.5 1538.92  5292.2 1543.44
  5400.3 1549.87  5439.6 1556.27  5459.1 1560.52  5524.6 1562.26  5553.5 1563.58
#Mann= 7 ,-1 , 0
  4329.2     .12       0  4503.9    .035       0  4805.7     .07       0
  4994.5     .05       0    5000     .07       0  5439.6     .12       0
  5524.6     .07       0
Bank Sta=4994.5,5000
XS Rating Curve= 0 ,0
Exp/Cntr=0.3,0.1

Type RM Length L Ch R = 1 ,33461   ,441,441,441
BEGIN DESCRIPTION:
SHEPS CREEK 62.0
END DESCRIPTION:
XS GIS Cut Line= 3
      2101525.04     13921225.03        2101175.       13920975.
      2100663.43     13920738.16
#Sta/Elev= 30
  4570.3 1567.92  4583.9 1567.58  4619.5 1559.79  4629.3 1558.82  4656.4 1557.17
  4693.2 1545.84  4728.9 1539.77  4747.8 1535.19  4791.6 1531.49  4868.4  1528.5
  4875.4 1527.78    4928 1520.96  5009.2    1516  5019.5 1511.11    5020 1510.61
  5025.6 1511.11  5032.1 1511.48  5044.5 1520.93    5055 1523.89  5060.5 1528.22
  5083.4 1530.41  5203.6 1531.98  5277.8 1536.28  5369.5 1547.08  5452.3 1552.81
  5496.4 1559.86  5529.4 1562.31    5541 1564.27  5558.4 1569.51  5564.2 1569.62
#Mann= 7 ,-1 , 0
  4570.3     .07       0  4629.3    .035       0  4747.8     .07       0
  4868.4    .035       0  4875.4     .07       0  5019.5     .05       0
  5025.6     .07       0
Bank Sta=5019.5,5025.6
XS Rating Curve= 0 ,0
Exp/Cntr=0.3,0.1

Type RM Length L Ch R = 1 ,33020   ,471,471,471
BEGIN DESCRIPTION:
SHEPS CREEK 61.0
END DESCRIPTION:
XS GIS Cut Line= 3
      2101546.29     13920873.62        2101425.       13920625.
      2101275.01       13920525.
#Sta/Elev= 30
  4729.5 1530.14  4811.8 1523.72    4902 1520.07  4930.1  1520.1  4939.4 1519.54
    4947 1518.17  4952.6 1515.37  4961.6 1511.98  4969.6 1508.03    4989 1502.34
  4989.5 1501.84  4994.7 1501.84  4995.2 1502.34  5003.3 1503.65  5009.1 1503.65
  5013.6 1503.05  5019.7  1504.2  5034.7 1505.51  5042.2 1507.07  5064.7 1509.65
  5070.7 1509.47  5085.8 1510.89  5091.8 1510.74  5100.8 1511.49  5106.8 1511.48
  5121.8 1516.14  5142.8 1518.71  5150.4 1520.66  5157.9 1521.81  5186.4 1523.92
#Mann= 3 ,-1 , 0
  4729.5     .07       0    4989     .05       0  4995.2     .07       0
Bank Sta=4989,4995.2
XS Rating Curve= 0 ,0
Exp/Cntr=0.3,0.1

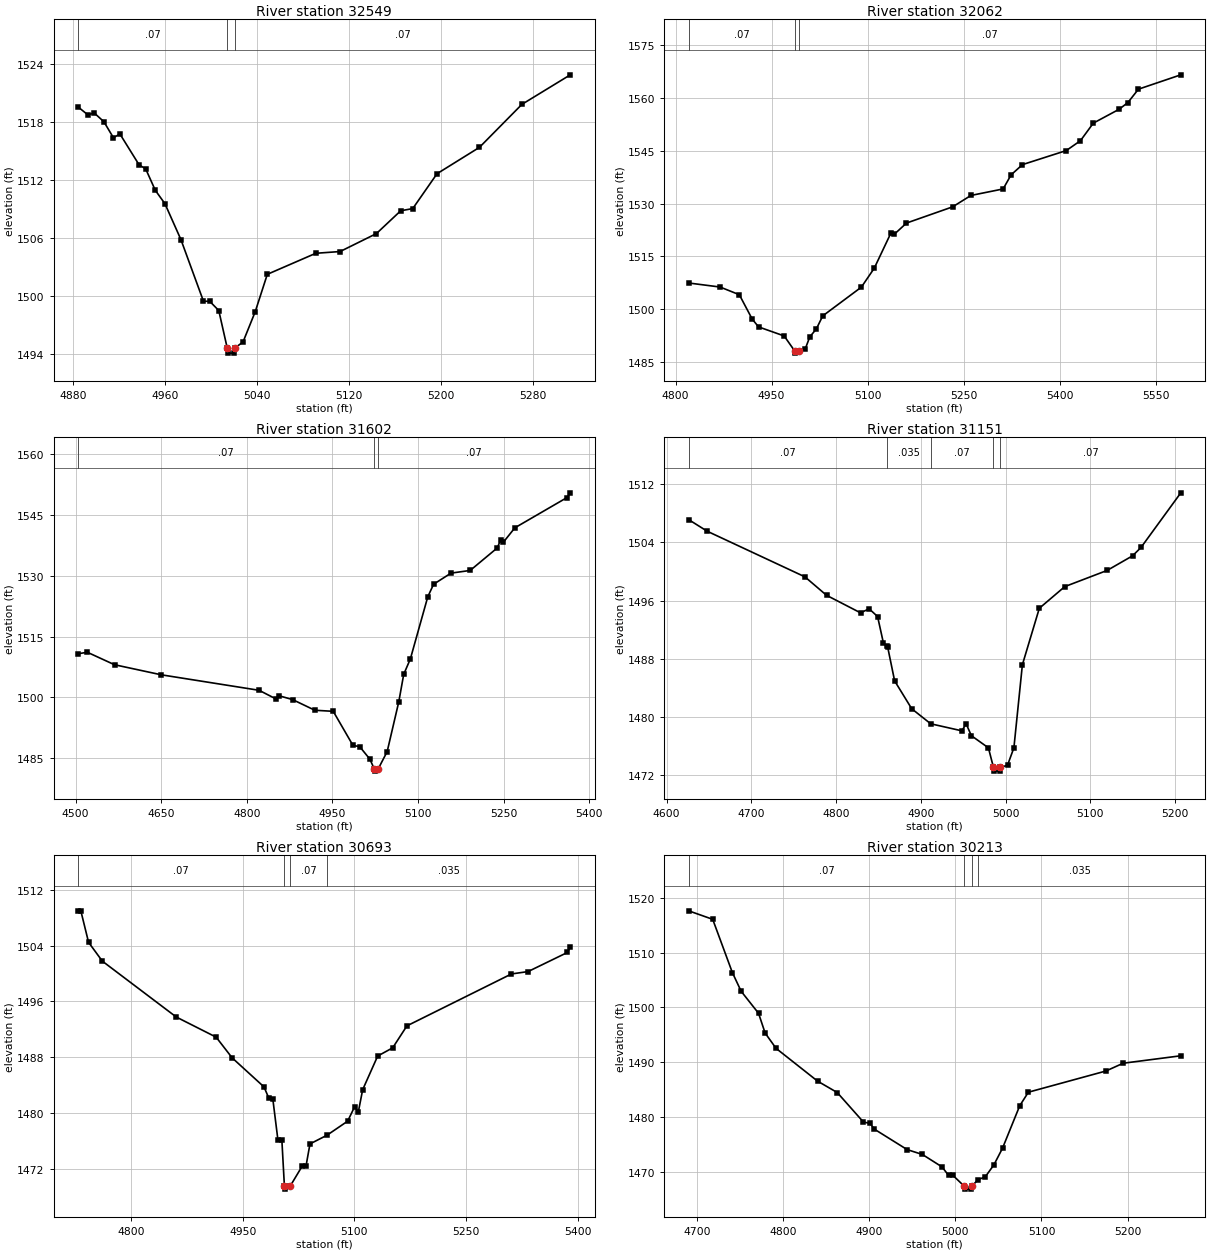
Type RM Length L Ch R = 1 ,32549   ,487,487,487
BEGIN DESCRIPTION:
SHEPS CREEK 60.0
END DESCRIPTION:
XS GIS Cut Line= 3
        2101825.       13920325.        2101725.       13920275.
      2101425.03     13920175.01
#Sta/Elev= 30
  4884.4 1519.56  4892.8 1518.75  4898.4 1518.94  4906.8 1518.03  4915.1 1516.37
  4920.7 1516.77  4937.5 1513.55  4943.1 1513.16  4951.5 1510.93  4959.9 1509.54
  4973.8 1505.82  4993.4 1499.44  4998.8 1499.44  5006.7 1498.48  5014.1 1494.57
  5014.6 1494.07  5019.9 1494.07  5020.4 1494.57  5027.8 1495.23  5038.4 1498.36
  5048.9 1502.23  5091.1 1504.41  5112.2 1504.59  5143.8 1506.45  5164.9 1508.81
  5175.4 1509.04  5196.5 1512.65  5233.4 1515.38  5270.3 1519.83  5312.4 1522.89
#Mann= 3 ,-1 , 0
  4884.4     .07       0  5014.1     .05       0  5020.4     .07       0
Bank Sta=5014.1,5020.4
XS Rating Curve= 0 ,0
Exp/Cntr=0.3,0.1

Type RM Length L Ch R = 1 ,32062   ,460,460,460
BEGIN DESCRIPTION:
SHEPS CREEK 59.0
END DESCRIPTION:
XS GIS Cut Line= 3
      2101804.08     13919829.32        2101625.       13919825.
      2101039.24     13919889.13
#Sta/Elev= 30
  4820.5 1507.47  4869.6 1506.32  4899.6 1504.14  4919.6 1497.25  4929.6    1495
  4969.6 1492.43  4986.5 1488.05    4987 1487.55  4992.8 1488.05  5002.2  1488.6
  5009.7  1492.2  5019.8  1494.4  5029.8 1498.12  5090.2  1506.3  5110.3 1511.68
  5136.4 1521.71  5141.5  1521.3  5160.6 1524.49  5232.7  1529.1  5261.2 1532.33
  5311.5 1534.18  5323.9 1538.18  5341.7 1541.09  5410.1 1545.08  5432.2 1547.88
  5452.3 1552.87  5492.6 1556.81  5506.3 1558.72  5522.7 1562.51  5588.9 1566.59
#Mann= 3 ,-1 , 0
  4820.5     .07       0  4986.5     .05       0  4992.8     .07       0
Bank Sta=4986.5,4992.8
XS Rating Curve= 0 ,0
Exp/Cntr=0.3,0.1

Type RM Length L Ch R = 1 ,31602   ,451,451,451
BEGIN DESCRIPTION:
SHEPS CREEK 58.0
END DESCRIPTION:
XS GIS Cut Line= 3
      2101915.23     13919877.34        2101725.       13919425.
      2101359.39     13919358.08
#Sta/Elev= 30
  4504.4 1510.77  4520.6 1511.12  4568.1 1508.06  4650.1 1505.58  4821.5 1501.77
    4851 1499.65  4856.4 1500.43  4880.1 1499.49  4919.2 1496.86  4951.4  1496.6
    4986 1488.21  4997.7 1487.92  5015.5 1484.85  5023.5 1482.39    5024 1481.89
    5030 1482.39  5045.9 1486.69  5066.3 1498.97  5074.9  1505.7  5086.6 1509.51
  5117.1 1524.78  5127.3 1527.86  5157.8 1530.59  5191.4 1531.25  5239.1 1536.82
  5244.6 1538.82  5249.7 1538.22  5269.6 1541.73  5361.2 1549.19  5366.8 1550.34
#Mann= 3 ,-1 , 0
  4504.4     .07       0  5023.5     .05       0    5030     .07       0
Bank Sta=5023.5,5030
XS Rating Curve= 0 ,0
Exp/Cntr=0.3,0.1

Type RM Length L Ch R = 1 ,31151   ,458,458,458
BEGIN DESCRIPTION:
SHEPS CREEK 57.0
END DESCRIPTION:
XS GIS Cut Line= 3
      2102246.79     13918985.57        2101875.       13919025.
        2101668.     13919022.06
#Sta/Elev= 30
    4626 1507.14  4647.9 1505.54  4763.2 1499.26  4788.7 1496.72  4828.9  1494.3
    4839 1494.86    4849 1493.79  4855.9 1490.13  4859.8 1489.71  4860.9 1489.59
  4869.1 1484.93  4889.3 1481.09  4911.7 1479.02  4948.5 1478.05  4953.5 1479.02
  4959.7 1477.38  4979.8 1475.71  4985.8    1473  4986.3  1472.5  4993.4  1472.5
  4993.9    1473  5002.4 1473.32  5009.9 1475.72  5019.9 1487.15  5039.9 1494.93
  5069.9 1497.91  5119.9 1500.14  5149.9 1502.15  5159.9  1503.3  5206.9 1510.83
#Mann= 5 ,-1 , 0
    4626     .07       0  4859.8    .035       0  4911.7     .07       0
  4985.8     .05       0  4993.9     .07       0
Bank Sta=4985.8,4993.9
XS Rating Curve= 0 ,0
Exp/Cntr=0.3,0.1

Type RM Length L Ch R = 1 ,30693   ,480,480,480
BEGIN DESCRIPTION:
SHEPS CREEK 56.0
END DESCRIPTION:
XS GIS Cut Line= 3
      2102278.07     13918722.56        2102025.       13918625.
      2101638.75      13918569.1
#Sta/Elev= 30
  4728.8    1509  4732.4    1509  4742.8 1504.48  4761.3 1501.78  4860.7 1493.76
  4914.3 1490.87  4935.8  1487.9  4978.6 1483.73    4985 1482.14  4990.4 1482.05
  4997.3 1476.13  5002.6 1476.13    5006 1469.56  5006.5 1469.06  5014.2 1469.56
  5030.1 1472.39  5035.2 1472.45  5040.4 1475.55  5063.2 1476.79    5091 1478.81
  5100.4 1480.88  5105.4 1480.14  5111.2 1483.32  5131.4 1488.16  5151.6 1489.34
  5170.7 1492.49  5311.2 1499.94  5333.5 1500.28  5386.5 1503.03  5390.3 1503.87
#Mann= 4 ,-1 , 0
  4728.8     .07       0    5006     .05       0  5014.2     .07       0
  5063.2    .035       0
Bank Sta=5006,5014.2
XS Rating Curve= 0 ,0
Exp/Cntr=0.3,0.1

Type RM Length L Ch R = 1 ,30213   ,434,434,434
BEGIN DESCRIPTION:
SHEPS CREEK 55.0
END DESCRIPTION:
XS GIS Cut Line= 3
      2102425.03     13918225.01        2102125.       13918175.
      2101858.11      13918170.5
#Sta/Elev= 30
  4690.6 1517.63  4718.5 1516.08  4741.3 1506.36  4751.5 1502.94  4771.7 1498.92
  4779.3 1495.32    4792 1492.52  4840.2 1486.53    4863 1484.45  4893.4 1479.06
    4901 1478.82  4906.1 1477.76  4944.1 1474.03  4961.8 1473.14  4984.6 1470.87
  4992.2 1469.32  4997.3 1469.32  5010.6 1467.31  5011.1 1466.81  5018.4 1466.81
  5018.9 1467.31  5026.5 1468.54  5034.8 1469.06  5044.8 1471.24  5054.8 1474.28
  5074.8 1482.04  5084.8 1484.51  5174.8 1488.38  5194.8  1489.8  5261.7 1491.16
#Mann= 4 ,-1 , 0
  4690.6     .07       0  5010.6     .05       0  5018.9     .07       0
  5026.5    .035       0
Bank Sta=5010.6,5018.9
XS Rating Curve= 0 ,0
Exp/Cntr=0.3,0.1

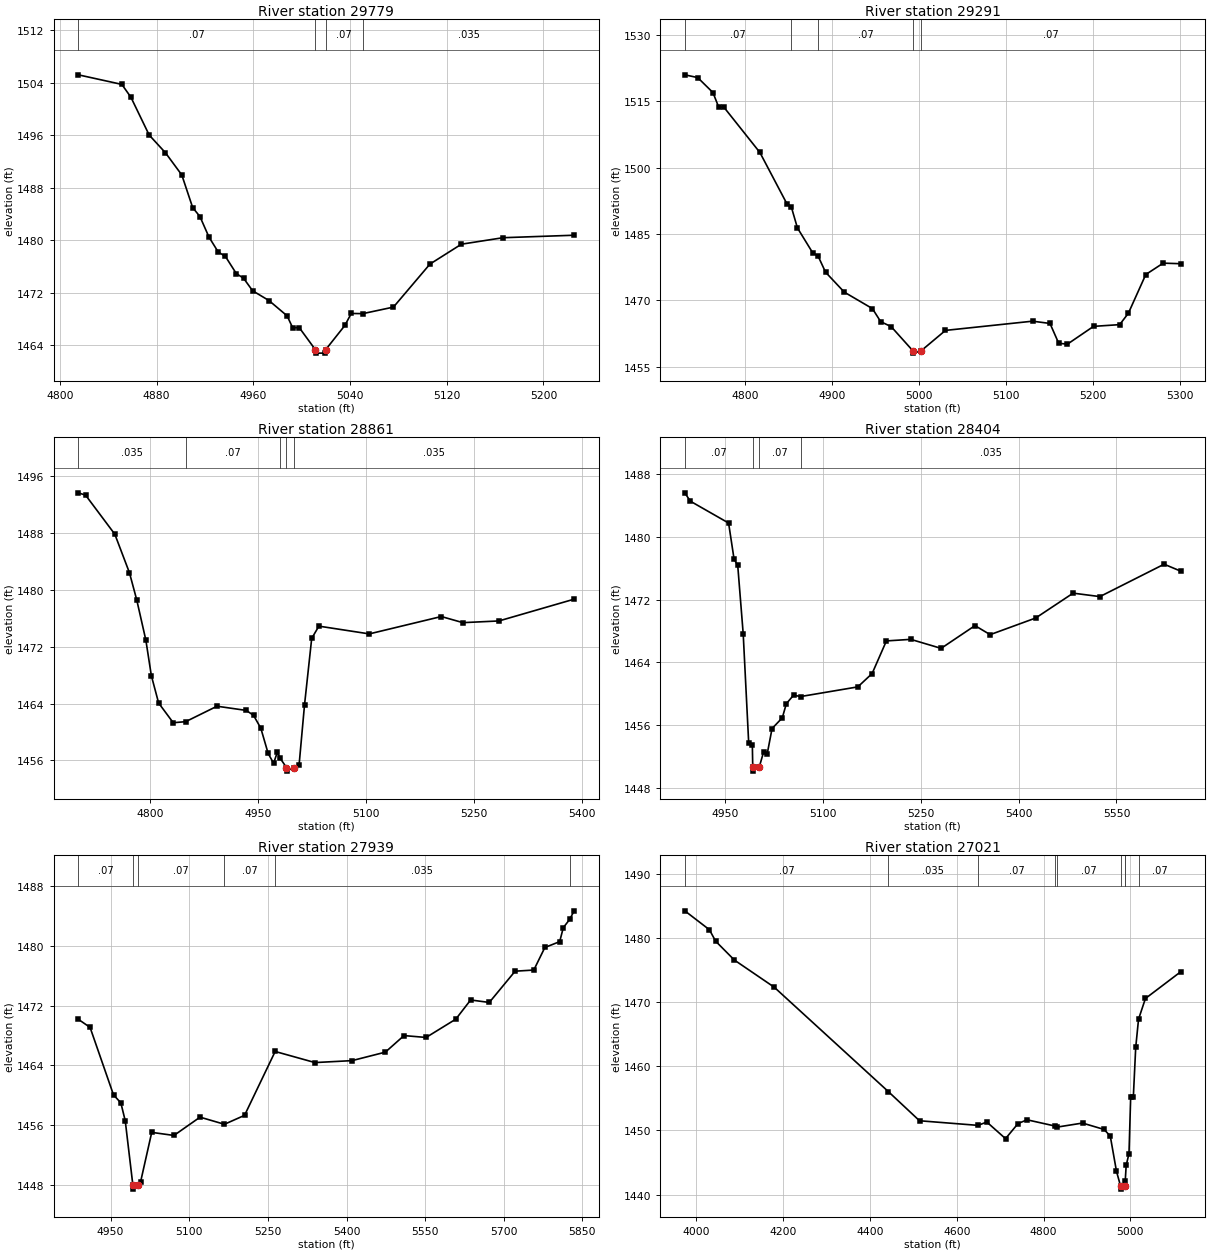
Type RM Length L Ch R = 1 ,29779   ,488,488,488
BEGIN DESCRIPTION:
SHEPS CREEK 54.0
END DESCRIPTION:
XS GIS Cut Line= 3
      2102474.98     13917924.99        2102325.       13917825.
      2102096.43     13917850.08
#Sta/Elev= 30
  4815.2 1505.21  4851.2 1503.75  4858.7 1501.79  4873.8 1496.03  4887.3 1493.32
  4900.8 1489.94  4909.8 1484.96  4915.8  1483.6  4923.3 1480.46  4930.9  1478.2
  4936.9 1477.51  4945.9  1474.9  4951.9 1474.19  4959.4 1472.28  4972.9 1470.79
  4987.9 1468.46  4992.5 1466.65    4998 1466.65  5011.4 1463.27  5011.9 1462.77
  5019.2 1462.77  5019.7 1463.27  5035.7 1466.99    5041 1468.82  5050.5 1468.79
  5075.9 1469.79  5106.1 1476.35  5132.1 1479.38  5166.5 1480.37  5225.4 1480.75
#Mann= 4 ,-1 , 0
  4815.2     .07       0  5011.4     .05       0  5019.7     .07       0
  5050.5    .035       0
Bank Sta=5011.4,5019.7
XS Rating Curve= 0 ,0
Exp/Cntr=0.3,0.1

Type RM Length L Ch R = 1 ,29291   ,430,430,430
BEGIN DESCRIPTION:
SHEPS CREEK 53.0
END DESCRIPTION:
XS GIS Cut Line= 3
      2102475.02     13917274.99        2102225.       13917375.
      2101924.98       13917375.
#Sta/Elev= 30
    4731 1520.93  4745.8 1520.31  4763.3 1516.93  4770.1 1513.56  4775.5 1513.72
  4817.2 1503.41  4848.2 1491.84  4853.2 1491.19  4860.3 1486.38  4877.8 1480.78
  4884.1    1480  4892.6 1476.39  4914.1 1471.89  4946.4 1468.17  4955.9 1465.23
    4968 1464.09    4993 1458.62  4993.5 1458.12  5002.2 1458.62  5030.3 1463.25
  5130.3 1465.33  5150.3 1464.82  5160.3 1460.35  5170.3 1460.14  5200.3 1464.16
  5230.3 1464.55  5240.3 1467.12  5260.3 1475.86  5280.3 1478.43  5300.3  1478.3
#Mann= 5 ,-1 , 0
    4731     .07       0  4853.2    .035       0  4884.1     .07       0
    4993     .05       0  5002.2     .07       0
Bank Sta=4993,5002.2
XS Rating Curve= 0 ,0
Exp/Cntr=0.3,0.1

Type RM Length L Ch R = 1 ,28861   ,457,457,457
BEGIN DESCRIPTION:
SHEPS CREEK 52.0
END DESCRIPTION:
XS GIS Cut Line= 3
        2102275.       13917025.        2101975.       13917075.
      2101590.54     13917076.72
#Sta/Elev= 30
  4700.5  1493.6  4710.6 1493.27  4751.2 1487.78  4771.5 1482.37  4781.6 1478.56
  4794.3 1472.89  4801.9 1467.92    4812 1464.07  4832.3  1461.3  4849.6 1461.45
  4893.1 1463.62  4933.7 1463.03  4943.8 1462.34  4953.9 1460.54  4964.1 1456.99
  4971.7  1455.6  4976.8 1457.14  4980.8 1456.31  4989.6    1455  4990.1  1454.5
  4999.4    1455  5007.1 1455.38  5014.6 1463.78  5024.6 1473.15  5034.6 1474.87
  5104.6 1473.78  5204.6 1476.22  5234.6 1475.36  5284.6  1475.6  5389.1 1478.66
#Mann= 5 ,-1 , 0
  4700.5    .035       0  4849.6     .07       0  4980.8    .035       0
  4989.6    .035       0  4999.4    .035       0
Bank Sta=4989.6,4999.4
XS Rating Curve= 0 ,0
Exp/Cntr=0.3,0.1

Type RM Length L Ch R = 1 ,28404   ,465,465,465
BEGIN DESCRIPTION:
SHEPS CREEK 51.0
END DESCRIPTION:
XS GIS Cut Line= 3
      2102225.03     13916624.98        2102125.       13916675.
      2101533.24      13916938.7
#Sta/Elev= 30
  4888.6 1485.61    4897 1484.55  4955.7 1481.76  4964.1 1477.15  4969.7 1476.36
  4978.1 1467.62  4986.5 1453.72  4992.1 1453.44  4992.7 1450.63  4993.2 1450.13
  5002.6 1450.63  5009.3 1452.56  5014.8  1452.3  5022.3 1455.56    5038 1456.93
  5044.2 1458.73  5055.2 1459.81  5066.2 1459.64  5153.7 1460.87  5175.6 1462.57
  5197.5 1466.73  5234.8 1466.93  5281.3 1465.78  5333.2 1468.68  5356.5 1467.53
  5426.2 1469.65  5483.6 1472.82  5524.6 1472.38    5623 1476.51  5648.3 1475.63
#Mann= 4 ,-1 , 0
  4888.6     .07       0  4992.7     .05       0  5002.6     .07       0
  5066.2    .035       0
Bank Sta=4992.7,5002.6
XS Rating Curve= 0 ,0
Exp/Cntr=0.3,0.1

Type RM Length L Ch R = 1 ,27939   ,918,918,918
BEGIN DESCRIPTION:
SHEPS CREEK 50.0
END DESCRIPTION:
XS GIS Cut Line= 3
      2102025.03     13916224.98        2101925.       13916275.
      2101351.62     13916880.71
#Sta/Elev= 30
  4888.4 1470.16  4910.8 1469.08  4955.5 1460.08  4969.5 1459.02  4977.9 1456.62
  4992.5 1448.01    4993 1447.51  5002.4 1448.01  5007.3 1448.52  5028.4 1455.08
  5070.8 1454.67  5120.6 1457.11  5167.1 1456.16  5205.5 1457.35  5263.9 1465.87
  5339.8 1464.39  5410.6 1464.65  5474.1 1465.78  5509.7 1467.99  5551.8 1467.74
  5608.5 1470.18  5636.8 1472.74  5672.4 1472.41  5721.7 1476.58  5757.3 1476.73
  5778.4 1479.74  5806.7 1480.52  5813.6 1482.39  5825.8 1483.49  5834.3 1484.63
#Mann= 6 ,-1 , 0
  4888.4     .07       0  4992.5     .05       0  5002.4     .07       0
  5167.1     .07       0  5263.9    .035       0  5825.8     .07       0
Bank Sta=4992.5,5002.4
XS Rating Curve= 0 ,0
Exp/Cntr=0.3,0.1

Type RM Length L Ch R = 1 ,27021   ,864,864,864
BEGIN DESCRIPTION:
SHEPS CREEK 49.0
END DESCRIPTION:
XS GIS Cut Line= 3
      2102274.99     13916174.99        2101475.       13915525.
      2101374.97     13915474.98
#Sta/Elev= 30
  3973.3 1484.27    4030 1481.32  4044.4 1479.53  4087.5 1476.59  4179.4 1472.35
  4442.2 1456.07  4514.2 1451.51  4648.9 1450.79  4669.3 1451.31  4712.4 1448.72
  4741.2 1451.07    4762 1451.66  4826.1 1450.69  4831.3 1450.52  4889.8 1451.15
  4939.6 1450.15  4953.8 1449.11  4968.1 1443.62  4977.4 1441.34  4977.9 1440.84
  4987.6 1441.34  4988.3 1442.14  4990.4 1444.53  4996.9 1446.39  5000.8 1455.18
  5006.9 1455.18  5012.4 1462.95  5018.9 1467.35  5034.8 1470.59  5115.9 1474.75
#Mann= 9 ,-1 , 0
  3973.3     .07       0  4442.2    .035       0  4648.9     .07       0
  4826.1    .035       0  4831.3     .07       0  4977.4    .035       0
  4987.6     .07       0  4988.3    .035       0  5018.9     .07       0
Bank Sta=4977.4,4987.6
XS Rating Curve= 0 ,0
Exp/Cntr=0.3,0.1