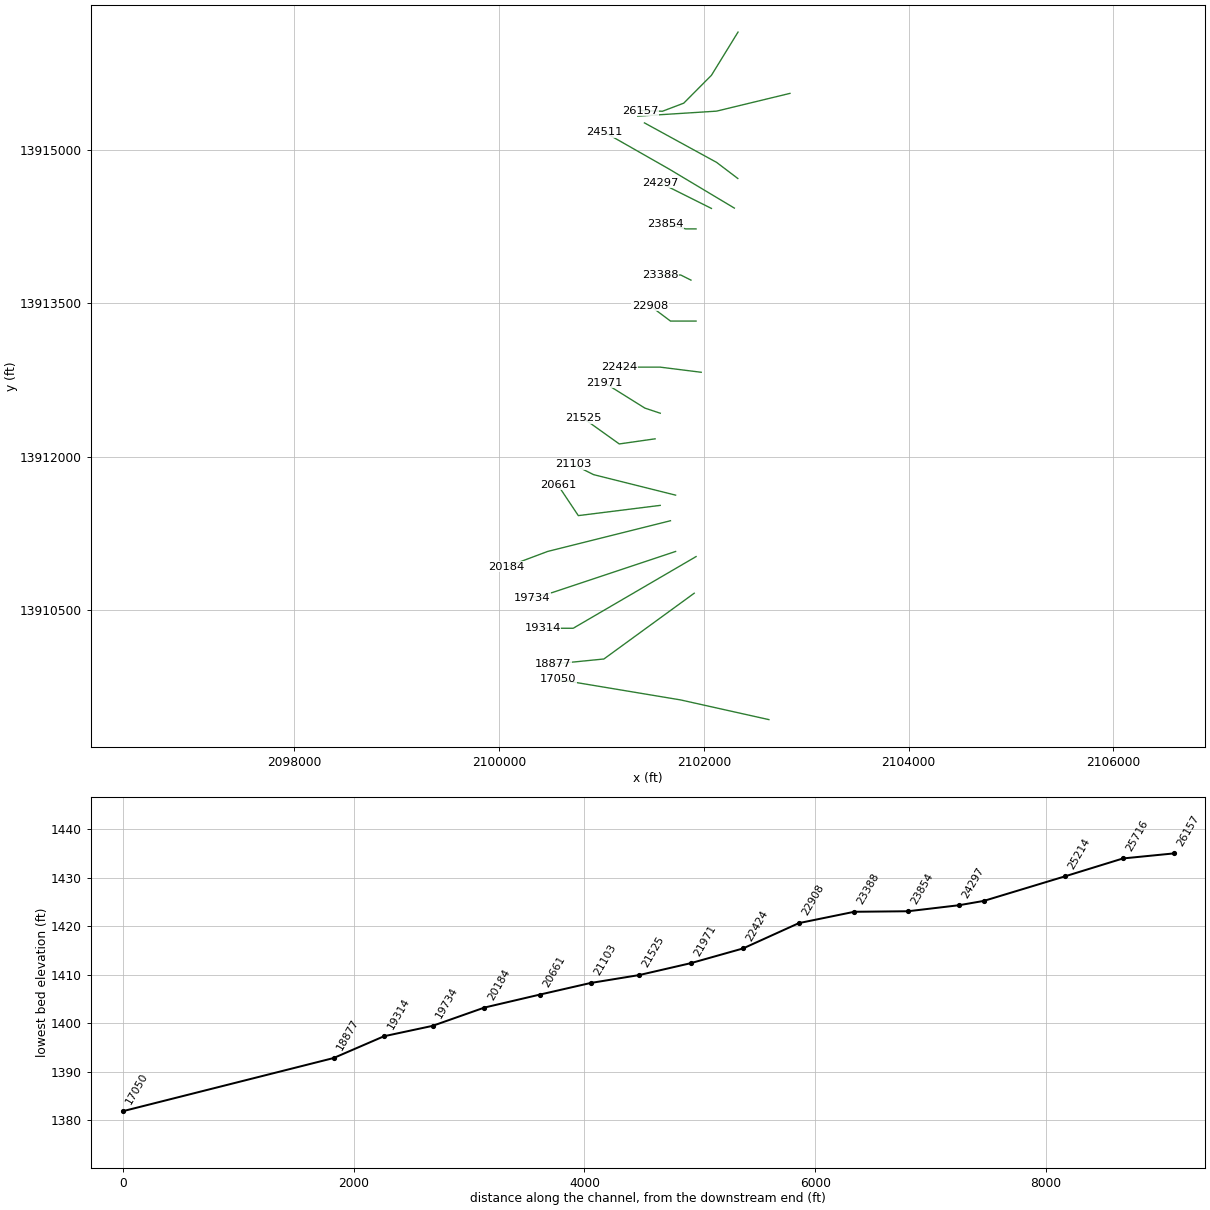
HEC-RAS study SHEPS CREEK.prj: SHEPS CREEK Base Level Engineering

--- SHEPS CREEK.g01 (geometry) --- (continued)

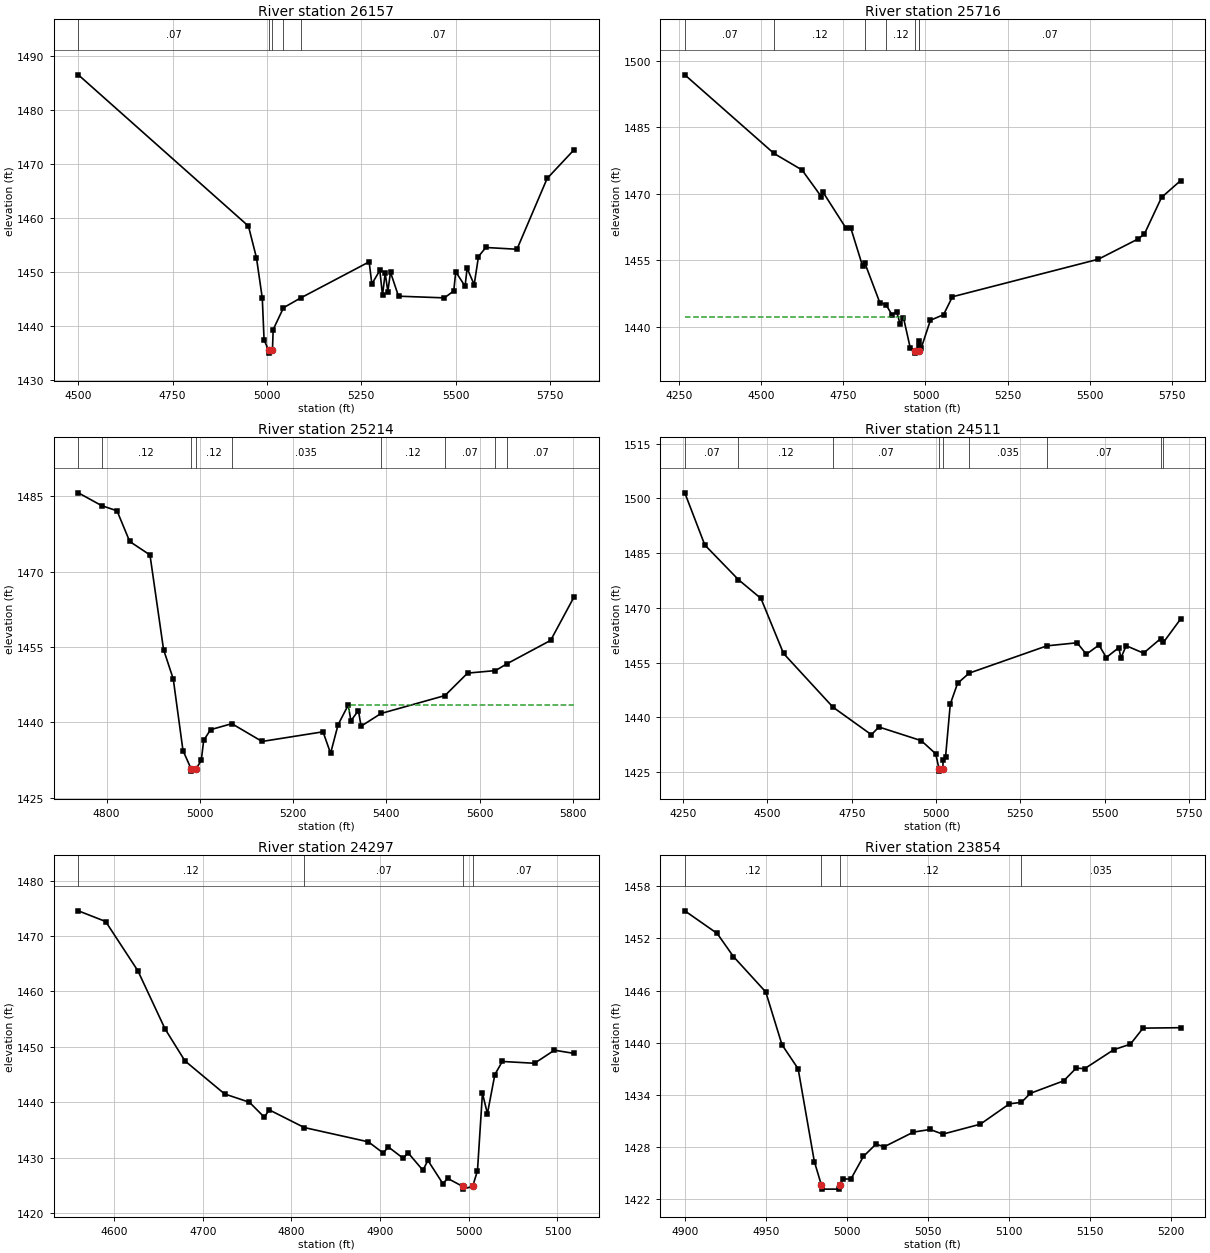
Type RM Length L Ch R = 1 ,26157   ,441,441,441
BEGIN DESCRIPTION:
SHEPS CREEK 48.0
END DESCRIPTION:
XS GIS Cut Line= 5
      2102334.56     13916147.03        2102075.       13915725.
      2101804.43     13915452.93      2101596.72     13915374.01
       2101383.4     13915380.88
#Sta/Elev= 30
  4499.8  1486.5  4950.9 1458.52  4972.1 1452.68  4987.6 1445.21  4992.3 1437.51
  5004.3 1435.53  5004.8 1435.03  5014.5 1435.53  5016.5 1439.39  5043.8 1443.42
    5089 1445.22    5271 1451.91  5278.1 1447.82  5299.3 1450.33  5306.4 1445.73
  5313.5 1449.84  5320.5 1446.42  5327.6 1449.99  5348.8 1445.56  5470.5 1445.25
  5495.3 1446.53  5500.6 1450.06  5525.4  1447.4  5530.7 1450.74  5549.5 1447.69
  5560.9 1452.89  5580.3 1454.57  5662.9 1454.24    5743 1467.34  5814.6 1472.66
#Mann= 5 ,-1 , 0
  4499.8     .07       0  5004.3     .05       0  5014.5     .07       0
  5043.8    .035       0    5089     .07       0
Bank Sta=5004.3,5014.5
XS Rating Curve= 0 ,0
Exp/Cntr=0.3,0.1

Type RM Length L Ch R = 1 ,25716   ,502,502,502
BEGIN DESCRIPTION:
SHEPS CREEK 47.0
END DESCRIPTION:
XS GIS Cut Line= 3
       2102841.7     13915548.47        2102125.       13915375.
      2101355.04     13915326.14
#Sta/Elev= 30
  4267.6 1496.86    4539  1479.1  4624.3 1475.37  4683.5 1469.29  4688.7  1470.3
  4758.1 1462.22  4772.3 1462.37    4809 1453.56  4815.4 1454.37  4861.1 1445.39
  4879.7 1444.97  4897.8 1442.67  4912.4 1443.29  4922.7  1440.6    4933 1442.03
  4953.5 1435.23  4968.8 1434.49  4969.3 1433.99  4979.4 1434.49  4980.4 1435.51
  4981.5 1436.64  4986.6 1435.04    5015 1441.41  5055.1 1442.68    5082 1446.72
    5526  1455.2  5646.3 1459.75  5666.3 1460.91  5718.5 1469.17  5776.5 1472.97
#Mann= 7 ,-1 , 0
  4267.6     .07       0    4539     .12       0  4815.4     .07       0
  4879.7     .12       0  4968.8     .05       0  4979.4     .12       0
  4980.4     .07       0
#XS Ineff= 2 , 0
       0 4934.93 1442.12               0
Permanent Ineff=
       F       F
Bank Sta=4968.8,4979.4
XS Rating Curve= 0 ,0
Exp/Cntr=0.3,0.1

Type RM Length L Ch R = 1 ,25214   ,703,703,703
BEGIN DESCRIPTION:
SHEPS CREEK 46.0
END DESCRIPTION:
XS GIS Cut Line= 3
      2102332.76     13914717.32        2102125.       13914875.
      2101420.81     13915260.44
#Sta/Elev= 30
  4739.3 1485.72  4789.3 1483.17  4822.3 1482.14  4849.5 1476.03    4893 1473.35
  4922.1 1454.51  4942.9 1448.66  4963.8  1434.4    4981  1430.8  4981.5  1430.3
  4992.1  1430.8    5003 1432.42  5008.2 1436.43  5022.9 1438.55  5068.6 1439.75
  5133.4 1436.21  5264.2 1438.13  5280.4 1433.85  5296.5 1439.54  5318.3 1443.46
    5324 1440.32  5340.1 1442.37  5345.8 1439.25  5388.6 1441.78  5525.8 1445.35
  5574.3 1449.82  5634.1 1450.32  5659.2  1451.7  5752.5 1456.34  5802.9 1465.03
#Mann= 9 ,-1 , 0
  4739.3     .07       0  4789.3     .12       0    4981     .05       0
  4992.1     .12       0  5068.6    .035       0  5388.6     .12       0
  5525.8     .07       0  5634.1     .12       0  5659.2     .07       0
#XS Ineff= 2 , 0
       0                 5320.77       0 1443.46
Permanent Ineff=
       F       F
Bank Sta=4981,4992.1
XS Rating Curve= 0 ,0
Exp/Cntr=0.3,0.1

Type RM Length L Ch R = 1 ,24511   ,214,214,214
BEGIN DESCRIPTION:
SHEPS CREEK 45.0
END DESCRIPTION:
XS GIS Cut Line= 3
      2102298.86     13914428.29      2101663.46     13914808.49
      2101029.39      13915169.7
#Sta/Elev= 30
  4255.1 1501.51  4314.4 1487.22  4413.9 1477.73    4481 1472.55  4547.8 1457.49
  4694.5 1442.76  4808.4 1435.21  4830.6 1437.33  4956.3 1433.58  4999.1 1429.98
  5009.2 1425.73  5009.7 1425.23  5020.6 1425.73  5020.7 1428.17  5028.3 1429.12
  5042.3 1443.62  5063.9 1449.29  5098.3 1452.09  5328.8 1459.57  5418.4 1460.41
  5445.7 1457.26  5483.2  1459.8  5504.8 1456.37  5542.3  1459.1    5548  1456.2
  5563.9  1459.6  5615.3 1457.57  5666.6 1461.58  5674.3 1460.51  5725.3 1466.93
#Mann= 9 ,-1 , 0
  4255.1     .07       0  4413.9     .12       0  4694.5     .07       0
  5009.2     .05       0  5020.6     .07       0  5098.3    .035       0
  5328.8     .07       0  5666.6    .035       0  5674.3     .07       0
Bank Sta=5009.2,5020.6
XS Rating Curve= 0 ,0
Exp/Cntr=0.3,0.1

Type RM Length L Ch R = 1 ,24297   ,443,443,443
BEGIN DESCRIPTION:
SHEPS CREEK 44.0
END DESCRIPTION:
XS GIS Cut Line= 3
      2102075.02     13914424.99        2101675.       13914625.
      2101575.03     13914674.98
#Sta/Elev= 30
  4559.8 1474.54  4590.6 1472.61  4626.9 1463.73  4657.6 1453.23    4680 1447.47
  4724.7 1441.51  4752.7 1440.01  4769.5 1437.31    4775 1438.64  4814.5 1435.45
  4886.8 1432.87  4903.6 1430.84  4909.2 1431.96    4926 1429.91  4931.6 1430.88
  4948.3 1427.74  4953.9 1429.52  4970.7 1425.35  4976.3 1426.27    4993 1424.84
  4993.5 1424.34  5004.4 1424.84  5009.8 1427.67  5015.4 1441.64    5021 1437.95
  5029.4 1445.01  5037.8 1447.37  5074.1 1447.04  5096.5  1449.4  5118.8 1448.82
#Mann= 4 ,-1 , 0
  4559.8     .12       0  4814.5     .07       0    4993     .05       0
  5004.4     .07       0
Bank Sta=4993,5004.4
XS Rating Curve= 0 ,0
Exp/Cntr=0.3,0.1

Type RM Length L Ch R = 1 ,23854   ,466,466,466
BEGIN DESCRIPTION:
SHEPS CREEK 43.0
END DESCRIPTION:
XS GIS Cut Line= 3
      2101925.01       13914225.        2101825.       13914225.
      2101624.96     13914275.01
#Sta/Elev= 30
    4900 1455.19    4920 1452.58    4930 1449.92    4950 1445.83    4960 1439.75
    4970 1436.97    4980 1426.27  4984.3 1423.59  4984.8 1423.09  4995.3 1423.09
  4995.8 1423.59  4997.5 1424.26  5002.6 1424.26  5010.3 1426.86    5018 1428.27
  5023.2 1427.98  5041.2 1429.67  5051.5 1429.97  5059.3 1429.43  5082.5 1430.58
  5100.5 1432.93  5107.9  1433.1  5113.4 1434.14    5134 1435.58  5141.7 1437.05
  5146.9 1436.98  5164.9 1439.17  5175.2 1439.81    5183 1441.66  5206.2 1441.71
#Mann= 4 ,-1 , 0
    4900     .12       0  4984.3     .05       0  4995.8     .12       0
  5107.9    .035       0
Bank Sta=4984.3,4995.8
XS Rating Curve= 0 ,0
Exp/Cntr=0.3,0.1

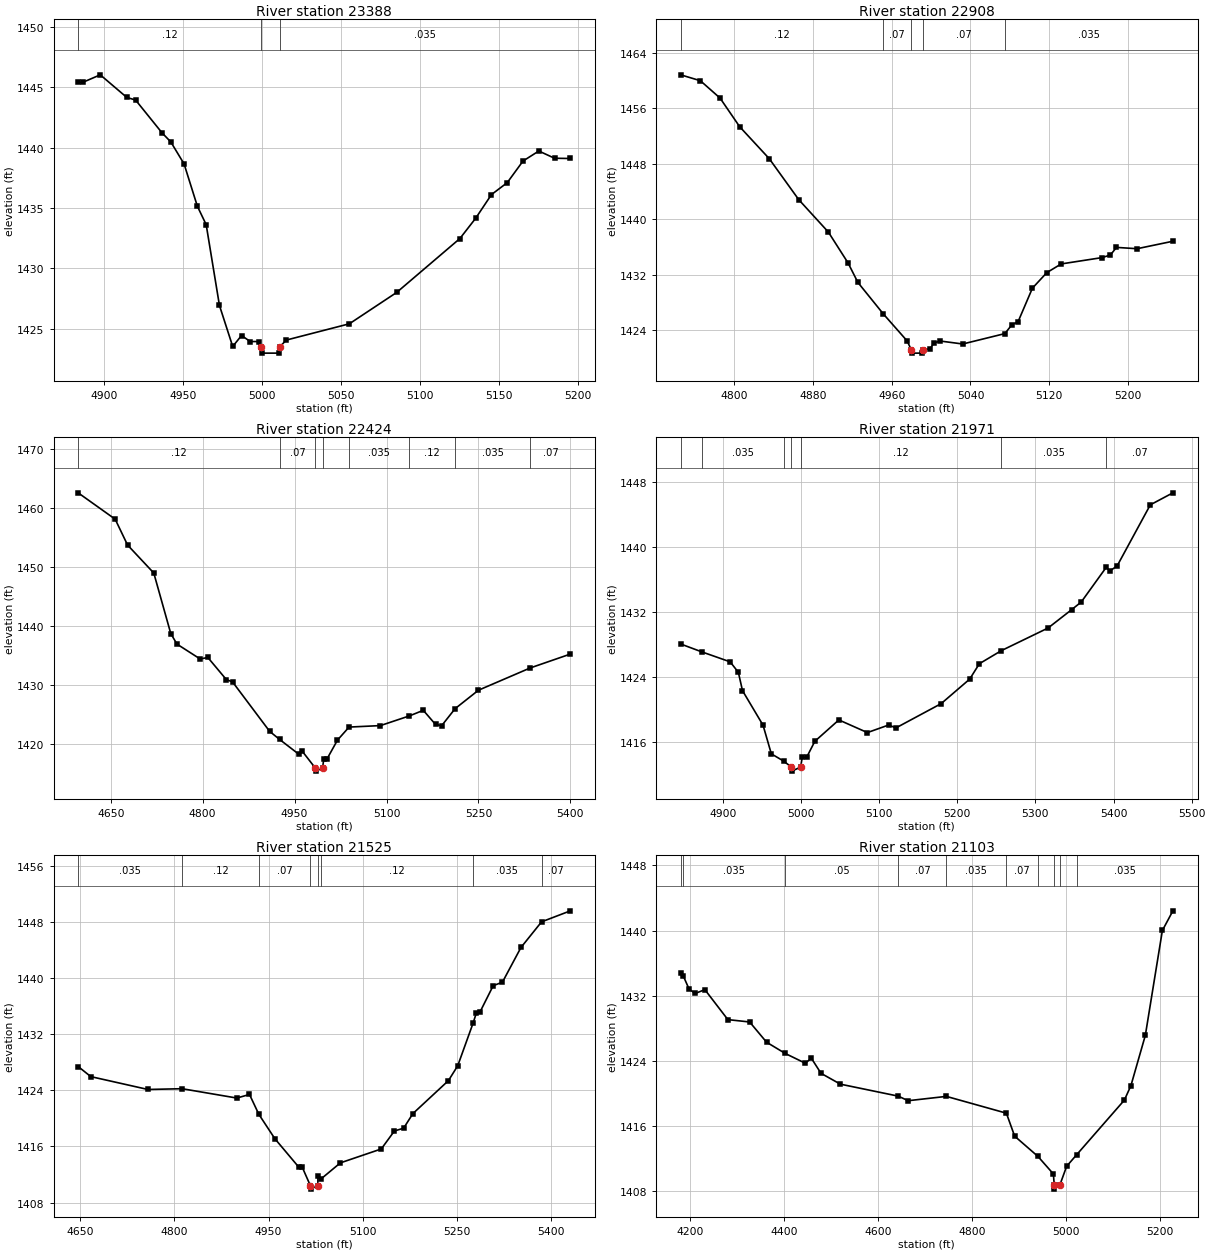
Type RM Length L Ch R = 1 ,23388   ,480,480,480
BEGIN DESCRIPTION:
SHEPS CREEK 42.0
END DESCRIPTION:
XS GIS Cut Line= 3
      2101875.04     13913724.98        2101775.       13913775.
      2101575.04       13913775.
#Sta/Elev= 30
  4883.5  1445.4  4886.3  1445.4  4897.5 1446.03  4914.3 1444.16  4919.9 1443.94
  4936.6 1441.23  4942.2 1440.47  4950.6 1438.65    4959 1435.15  4964.6 1433.62
    4973 1426.93  4981.4 1423.53    4987 1424.44  4992.5 1423.94  4997.8 1423.94
  4999.6 1423.48  5000.1 1422.98  5010.6 1422.98  5011.1 1423.48  5015.3 1424.06
  5055.3 1425.41  5085.3 1428.01  5125.3 1432.47  5135.3 1434.15  5145.3 1436.11
  5155.3  1437.1  5165.3 1438.89  5175.3 1439.72  5185.3 1439.12  5195.3  1439.1
#Mann= 3 ,-1 , 0
  4883.5     .12       0  4999.6     .05       0  5011.1    .035       0
Bank Sta=4999.6,5011.1
XS Rating Curve= 0 ,0
Exp/Cntr=0.3,0.1

Type RM Length L Ch R = 1 ,22908   ,484,484,484
BEGIN DESCRIPTION:
SHEPS CREEK 41.0
END DESCRIPTION:
XS GIS Cut Line= 3
      2101925.03       13913325.        2101675.       13913325.
      2101475.02     13913474.98
#Sta/Elev= 30
  4745.6 1460.86  4765.6 1460.01  4785.6  1457.5  4805.6 1453.35  4835.6 1448.74
  4865.6 1442.81  4895.6 1438.14  4915.6 1433.68  4925.6 1430.86  4951.3 1426.33
  4975.6 1422.41  4979.8 1421.14  4980.3 1420.64  4990.9 1420.64  4991.4 1421.14
  4998.8 1421.23  5002.9 1422.12  5009.2 1422.39  5032.1 1421.96  5074.9 1423.46
  5082.1 1424.75  5088.3 1425.17  5102.9 1430.03  5117.5 1432.27  5132.1 1433.53
  5173.8 1434.45  5182.1 1434.82  5188.3 1435.92  5209.2 1435.73  5245.6 1436.81
#Mann= 5 ,-1 , 0
  4745.6     .12       0  4951.3     .07       0  4979.8     .05       0
  4991.4     .07       0  5074.9    .035       0
Bank Sta=4979.8,4991.4
XS Rating Curve= 0 ,0
Exp/Cntr=0.3,0.1

Type RM Length L Ch R = 1 ,22424   ,453,453,453
BEGIN DESCRIPTION:
SHEPS CREEK 40.0
END DESCRIPTION:
XS GIS Cut Line= 3
      2101974.96       13912825.        2101575.       13912875.
      2101174.97       13912875.
#Sta/Elev= 30
  4596.9  1462.6  4657.3 1458.13  4677.5 1453.75  4720.3    1449    4748 1438.74
  4758.1 1436.95  4795.9 1434.43  4808.5 1434.68  4838.7 1430.93  4848.8 1430.54
  4909.3 1422.16  4925.6 1420.78  4957.1 1418.26  4962.2 1418.83    4984 1415.91
  4984.5 1415.41  4995.7 1415.91  4997.5  1417.4  5002.5  1417.4    5020 1420.67
  5038.9 1422.88    5090 1423.13  5137.5 1424.78    5160 1425.72    5180 1423.32
    5190 1423.12  5211.9    1426    5250 1429.13  5334.6 1432.91    5400 1435.26
#Mann= 8 ,-1 , 0
  4596.9     .12       0  4925.6     .07       0    4984     .05       0
  4995.7     .07       0  5038.9    .035       0  5137.5     .12       0
  5211.9    .035       0  5334.6     .07       0
Bank Sta=4984,4995.7
XS Rating Curve= 0 ,0
Exp/Cntr=0.3,0.1

Type RM Length L Ch R = 1 ,21971   ,446,446,446
BEGIN DESCRIPTION:
SHEPS CREEK 39.0
END DESCRIPTION:
XS GIS Cut Line= 3
      2101575.03     13912424.99        2101425.       13912475.
      2101025.03     13912724.98
#Sta/Elev= 30
  4846.2 1428.04  4872.9 1427.08  4909.5 1425.84    4920 1424.55  4925.3 1422.29
  4951.6 1418.03  4962.2  1414.5  4977.9 1413.61  4987.9 1412.87  4988.4 1412.37
  4999.7 1412.87  5001.7 1414.06  5007.3 1414.06  5017.9 1416.05  5048.6 1418.68
  5085.1 1417.12  5112.2 1418.05  5121.7  1417.7  5179.5 1420.69    5216 1423.71
  5228.4 1425.61  5256.5 1427.22  5316.3 1430.01  5346.3 1432.26  5358.7 1433.21
  5390.8  1437.5  5395.3 1437.03  5404.7 1437.67  5447.1 1445.19    5476 1446.67
#Mann= 7 ,-1 , 0
  4846.2     .12       0  4872.9    .035       0  4977.9     .12       0
  4987.9     .05       0  4999.7     .12       0  5256.5    .035       0
  5390.8     .07       0
Bank Sta=4987.9,4999.7
XS Rating Curve= 0 ,0
Exp/Cntr=0.3,0.1

Type RM Length L Ch R = 1 ,21525   ,422,422,422
BEGIN DESCRIPTION:
SHEPS CREEK 38.0
END DESCRIPTION:
XS GIS Cut Line= 3
      2101525.01       13912175.        2101175.       13912125.
      2100824.99     13912375.01
#Sta/Elev= 30
  4646.8 1427.38    4667 1425.94  4757.9 1424.11  4812.2 1424.22  4899.4 1422.89
  4919.6  1423.4  4934.5 1420.57    4960  1417.1  4997.8 1413.08  5003.4 1413.08
  5016.5 1410.42    5017 1409.92  5028.4 1410.42  5028.6 1411.81    5034 1411.41
  5064.3 1413.66  5129.4 1415.64  5150.3  1418.2    5165  1418.6  5179.8 1420.68
  5236.3 1425.37  5251.1 1427.48  5275.7 1433.59  5280.6 1434.95  5286.7 1435.16
  5307.6 1438.89  5322.3 1439.39  5351.8 1444.33  5384.6 1447.98  5430.5 1449.55
#Mann= 8 ,-1 , 0
  4646.8    .035       0  4812.2     .12       0  4934.5     .07       0
  5016.5     .05       0  5028.4     .07       0    5034     .12       0
  5275.7    .035       0  5384.6     .07       0
Bank Sta=5016.5,5028.4
XS Rating Curve= 0 ,0
Exp/Cntr=0.3,0.1

Type RM Length L Ch R = 1 ,21103   ,442,442,442
BEGIN DESCRIPTION:
SHEPS CREEK 37.0
END DESCRIPTION:
XS GIS Cut Line= 3
      2101724.98       13911625.        2100925.       13911825.
      2100725.01       13911925.
#Sta/Elev= 30
  4179.4 1434.79  4185.4 1434.38  4197.4 1432.82  4210.3 1432.29  4230.9 1432.76
  4279.9 1429.08  4326.3 1428.79  4362.3 1426.31    4402 1424.93  4444.8 1423.73
  4457.7 1424.34  4478.3 1422.49  4519.5 1421.16  4642.8 1419.69  4663.8 1419.13
  4745.2 1419.66    4873  1417.6  4890.6 1414.78  4940.1  1412.3  4973.1 1410.14
  4974.9 1408.78  4975.4 1408.28  4986.8 1408.78  5001.4 1411.09  5022.5 1412.49
  5124.2  1419.2  5138.2 1420.98  5168.9 1427.15  5205.2 1440.02  5227.6 1442.43
#Mann= 10 ,-1 , 0
  4179.4     .07       0  4185.4    .035       0    4402     .05       0
  4642.8     .07       0  4745.2    .035       0    4873     .07       0
  4940.1     .12       0  4974.9     .05       0  4986.8     .12       0
  5022.5    .035       0
Bank Sta=4974.9,4986.8
XS Rating Curve= 0 ,0
Exp/Cntr=0.3,0.1

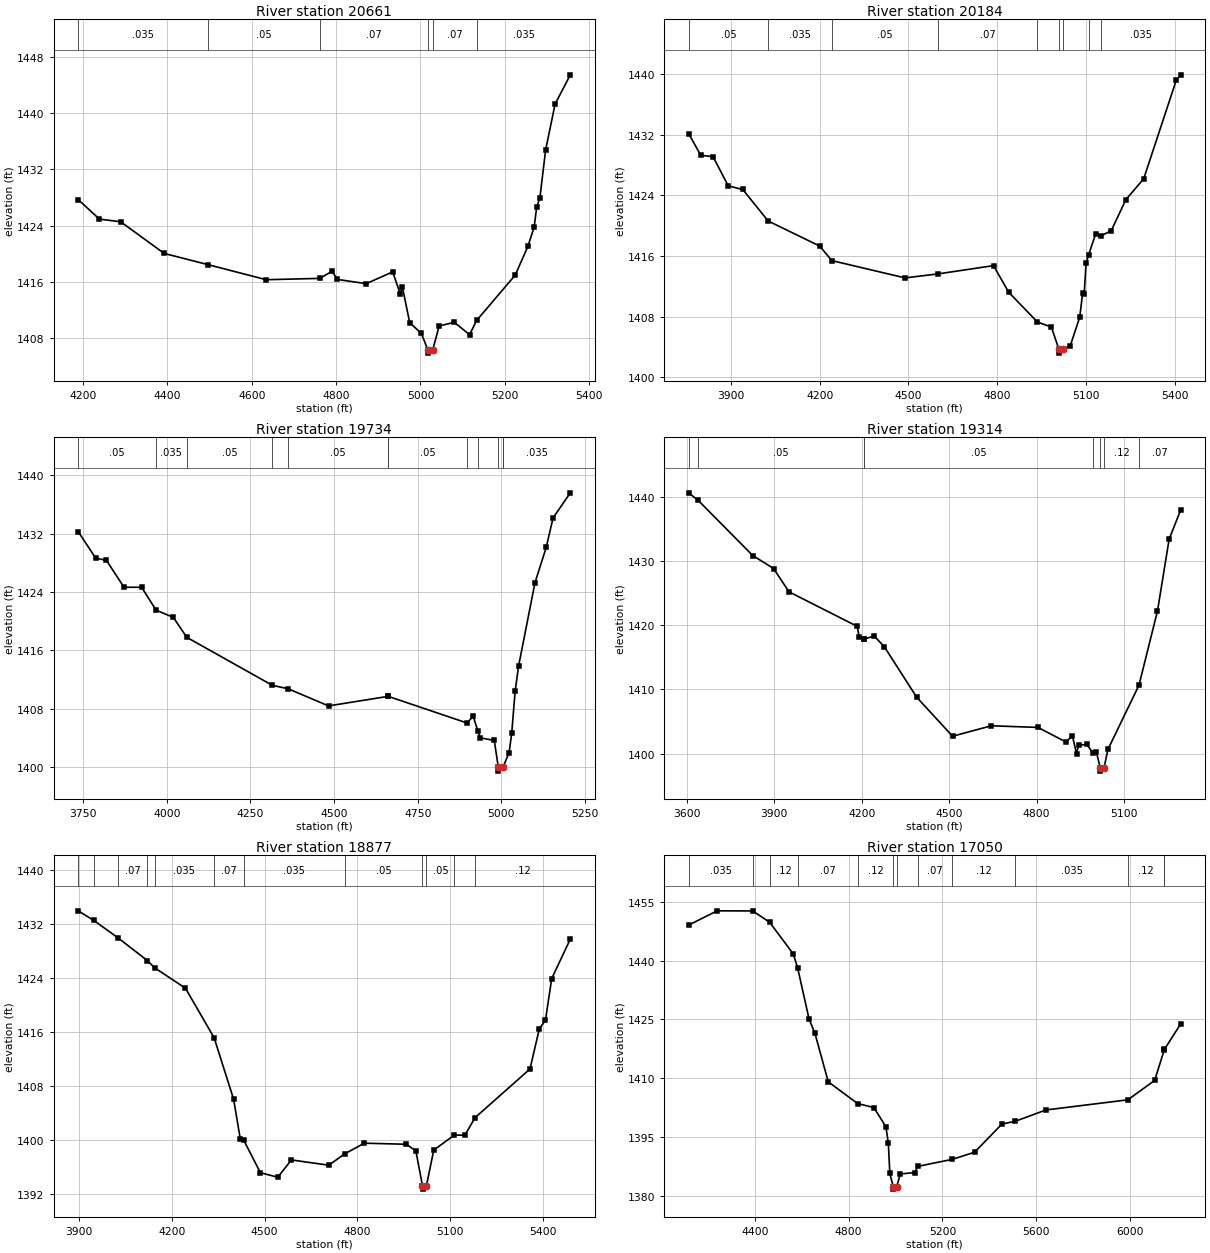
Type RM Length L Ch R = 1 ,20661   ,477,477,477
BEGIN DESCRIPTION:
SHEPS CREEK 36.0
END DESCRIPTION:
XS GIS Cut Line= 3
      2101574.98       13911525.        2100775.       13911425.
      2100574.98     13911725.03
#Sta/Elev= 30
  4188.4 1427.69  4238.8 1424.91  4289.2 1424.53  4392.5 1420.03  4495.7 1418.45
  4634.3  1416.3  4761.2 1416.49  4790.5  1417.5  4803.1 1416.34  4871.2 1415.74
  4934.1 1417.41  4951.8 1414.32  4956.8 1415.32  4974.5 1410.19  5002.1 1408.67
  5017.2 1406.37  5017.7 1405.87  5029.2 1406.37  5044.2 1409.72  5080.2 1410.25
  5116.3 1408.49  5133.3 1410.53  5224.5 1416.95  5254.5 1421.02  5269.5 1423.78
  5275.5 1426.63  5283.1 1427.95  5296.6 1434.71  5319.1 1441.26  5355.2 1445.41
#Mann= 6 ,-1 , 0
  4188.4    .035       0  4495.7     .05       0  4761.2     .07       0
  5017.2     .05       0  5029.2     .07       0  5133.3    .035       0
Bank Sta=5017.2,5029.2
XS Rating Curve= 0 ,0
Exp/Cntr=0.3,0.1

Type RM Length L Ch R = 1 ,20184   ,450,450,450
BEGIN DESCRIPTION:
SHEPS CREEK 35.0
END DESCRIPTION:
XS GIS Cut Line= 3
        2101675.       13911375.        2100475.       13911075.
      2100075.03     13910925.01
#Sta/Elev= 30
  3757.1 1432.16  3798.3 1429.29  3839.6 1429.12  3891.1 1425.26  3940.1 1424.79
  4026.1 1420.63  4200.3 1417.33  4241.3 1415.41  4488.9 1413.13  4600.9 1413.66
  4787.9 1414.75  4839.4 1411.23  4936.3 1407.32  4983.7 1406.64    5009 1403.71
  5009.5 1403.21  5021.7 1403.71  5047.4 1404.18  5079.5 1407.96  5089.3 1411.15
  5094.6 1411.05  5100.8 1415.04  5109.6 1416.19  5132.9 1418.89  5152.9  1418.7
  5186.3 1419.37  5235.2 1423.44  5295.7  1426.2  5406.1 1439.23  5421.2 1439.91
#Mann= 9 ,-1 , 0
  3757.1     .05       0  4026.1    .035       0  4241.3     .05       0
  4600.9     .07       0  4936.3    .035       0    5009    .035       0
  5021.7    .035       0  5109.6     .07       0  5152.9    .035       0
Bank Sta=5009,5021.7
XS Rating Curve= 0 ,0
Exp/Cntr=0.3,0.1

Type RM Length L Ch R = 1 ,19734   ,420,420,420
BEGIN DESCRIPTION:
SHEPS CREEK 34.0
END DESCRIPTION:
XS GIS Cut Line= 3
      2101724.97     13911074.99        2100525.       13910675.
      2100325.04     13910625.01
#Sta/Elev= 30
  3735.1 1432.27  3787.8 1428.61  3819.4 1428.34  3872.1 1424.64  3924.8 1424.63
    3968  1421.5  4019.7  1420.5  4059.8 1417.77  4315.2  1411.2  4363.2 1410.71
  4483.5 1408.37  4661.6 1409.68  4661.9 1409.68  4897.9 1406.02  4915.7 1406.97
    4930 1404.91  4936.7    1404  4978.9 1403.63  4990.9 1399.93  4991.4 1399.43
  5003.7 1399.93  5005.5 1400.03  5023.2 1401.98  5030.9 1404.62  5041.2 1410.39
  5051.5 1413.84  5100.5 1425.26    5134 1430.09  5154.6 1434.15  5206.1 1437.58
#Mann= 12 ,-1 , 0
  3735.1     .05       0    3968    .035       0  4059.8     .05       0
  4315.2    .035       0  4363.2     .05       0  4661.6     .07       0
  4661.9     .05       0  4897.9     .07       0    4930     .12       0
  4990.9     .05       0  5003.7     .12       0  5005.5    .035       0
Bank Sta=4990.9,5003.7
XS Rating Curve= 0 ,0
Exp/Cntr=0.3,0.1

Type RM Length L Ch R = 1 ,19314   ,437,437,437
BEGIN DESCRIPTION:
SHEPS CREEK 33.0
END DESCRIPTION:
XS GIS Cut Line= 3
      2101924.98     13911024.99        2100725.       13910325.
      2100425.02       13910325.
#Sta/Elev= 30
    3606 1440.61  3639.1 1439.42  3825.9 1430.85  3897.5 1428.83  3950.4  1425.2
  4184.8 1419.82    4191  1418.2  4207.1  1417.8  4207.7 1417.83  4242.7 1418.32
  4277.4 1416.67  4388.7 1408.79  4511.9 1402.72    4645 1404.35  4805.4 1404.09
  4901.4 1401.81  4922.9 1402.81  4937.3 1400.03  4944.4 1401.31  4972.1 1401.45
  4994.5 1400.08  5005.2  1400.3  5018.8 1397.79  5019.3 1397.29  5031.6 1397.79
  5045.2 1400.68  5151.5 1410.65  5215.2 1422.23  5255.2 1433.41  5295.2 1437.99
#Mann= 8 ,-1 , 0
    3606     .07       0  3639.1     .05       0  4207.1    .035       0
  4207.7     .05       0  4994.5     .12       0  5018.8     .05       0
  5031.6     .12       0  5151.5     .07       0
Bank Sta=5018.8,5031.6
XS Rating Curve= 0 ,0
Exp/Cntr=0.3,0.1

Type RM Length L Ch R = 1 ,18877   ,1827,1827,1827
BEGIN DESCRIPTION:
SHEPS CREEK 32.0
END DESCRIPTION:
XS GIS Cut Line= 3
      2101906.96     13910667.26        2101025.       13910025.
      2100525.02       13909975.
#Sta/Elev= 30
  3896.3 1433.98  3946.2 1432.58  4024.2 1430.02  4120.6 1426.61  4143.5 1425.56
  4243.6 1422.53  4336.6 1415.19  4399.7 1406.08  4421.4 1400.18  4432.5 1400.03
  4486.3 1395.22  4542.7 1394.55  4586.7 1397.11    4708 1396.33  4758.9    1398
  4823.1 1399.59  4959.1 1399.43  4989.8 1398.44  5011.1 1393.29  5011.6 1392.79
  5023.9 1393.29  5047.6 1398.56  5114.8 1400.81  5148.1 1400.75  5181.4 1403.37
  5359.2 1410.57  5389.3 1416.49  5409.4 1417.81  5429.5 1423.95  5489.8  1429.8
#Mann= 12 ,-1 , 0
  3896.3     .07       0  3946.2     .12       0  4024.2     .07       0
  4120.6     .12       0  4143.5    .035       0  4336.6     .07       0
  4432.5    .035       0  4758.9     .05       0  5011.1     .05       0
  5023.9     .05       0  5114.8    .035       0  5181.4     .12       0
Bank Sta=5011.1,5023.9
XS Rating Curve= 0 ,0
Exp/Cntr=0.3,0.1

Type RM Length L Ch R = 1 ,17050   ,540,540,540
BEGIN DESCRIPTION:
SHEPS CREEK 31.0
END DESCRIPTION:
XS GIS Cut Line= 3
      2102636.11     13909432.88        2101775.       13909625.
      2100575.04     13909824.99
#Sta/Elev= 30
  4117.7 1449.02  4239.5 1452.65  4391.3 1452.62  4463.4 1449.72  4564.1 1441.66
  4582.7 1438.08  4631.1 1425.13  4656.2 1421.49  4713.1 1409.12  4838.1  1403.6
  4907.8 1402.56    4959 1397.68  4969.2 1393.53  4975.7  1385.8  4990.5 1382.31
    4991 1381.81  5004.4 1382.31  5020.3 1385.67  5081.1 1386.01  5095.3 1387.61
  5241.9 1389.39  5337.1  1391.2  5453.7 1398.37    5511 1399.09  5641.2 1401.96
  5990.6 1404.54    6105 1409.48  6145.9 1417.25  6146.6 1417.38  6216.5 1423.91
#Mann= 13 ,-1 , 0
  4117.7    .035       0  4391.3     .07       0  4463.4     .12       0
  4582.7     .07       0  4838.1     .12       0  4990.5     .05       0
  5004.4     .12       0  5095.3     .07       0  5241.9     .12       0
    5511    .035       0  5990.6     .12       0  6145.9     .07       0
  6146.6     .12       0
Bank Sta=4990.5,5004.4
XS Rating Curve= 0 ,0
Exp/Cntr=0.3,0.1