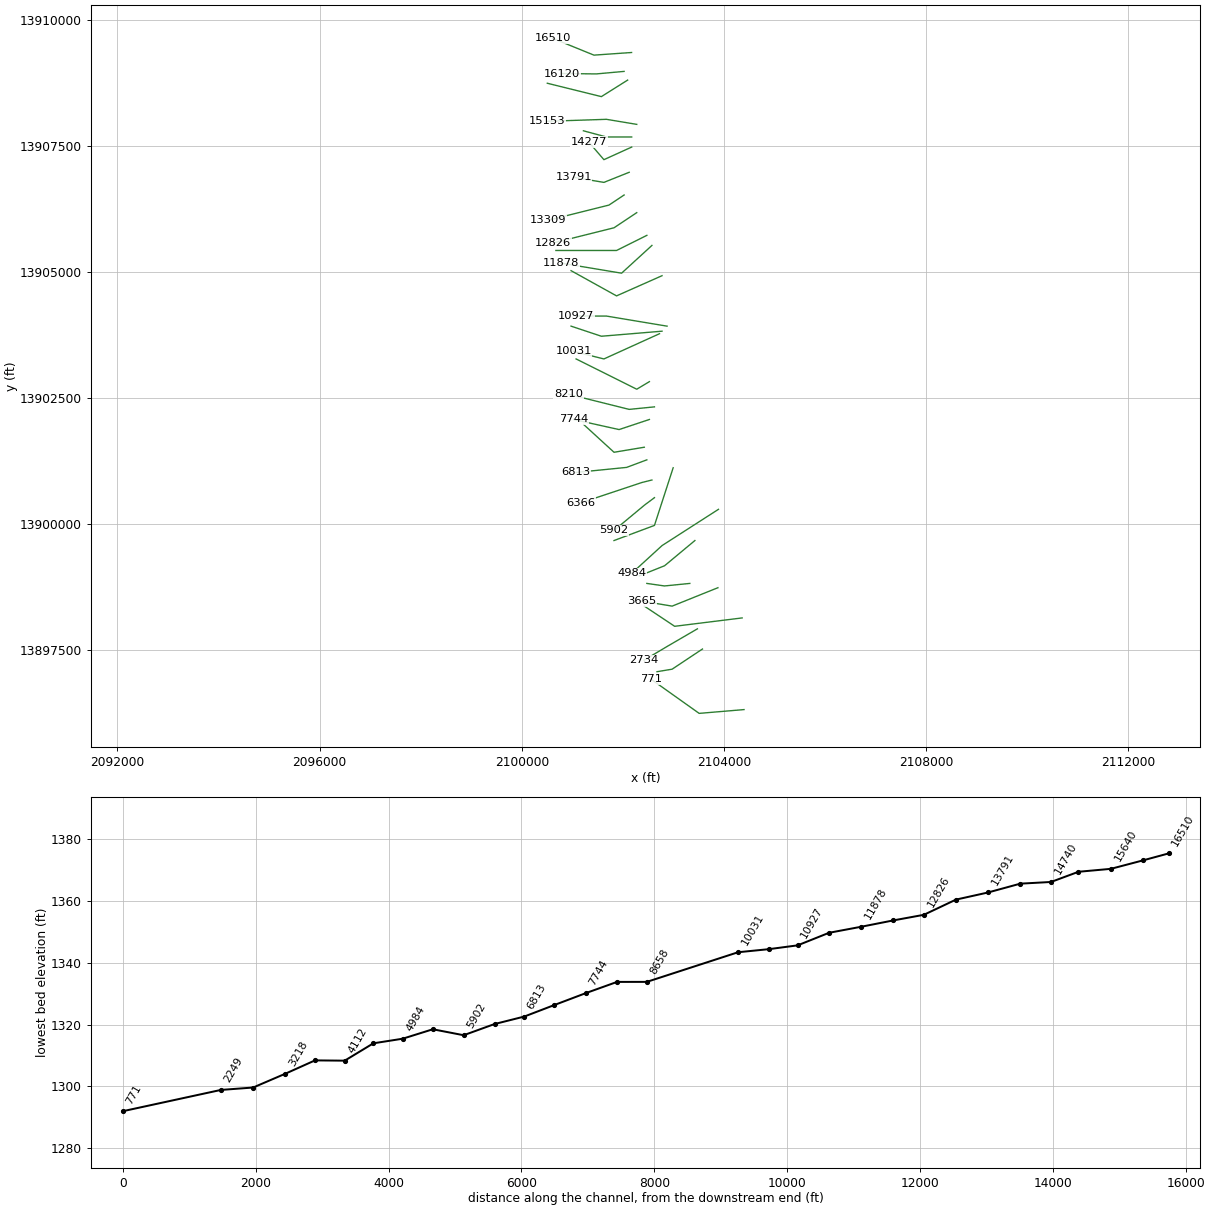
HEC-RAS study SHEPS CREEK.prj: SHEPS CREEK Base Level Engineering

--- SHEPS CREEK.g01 (geometry) --- (continued)

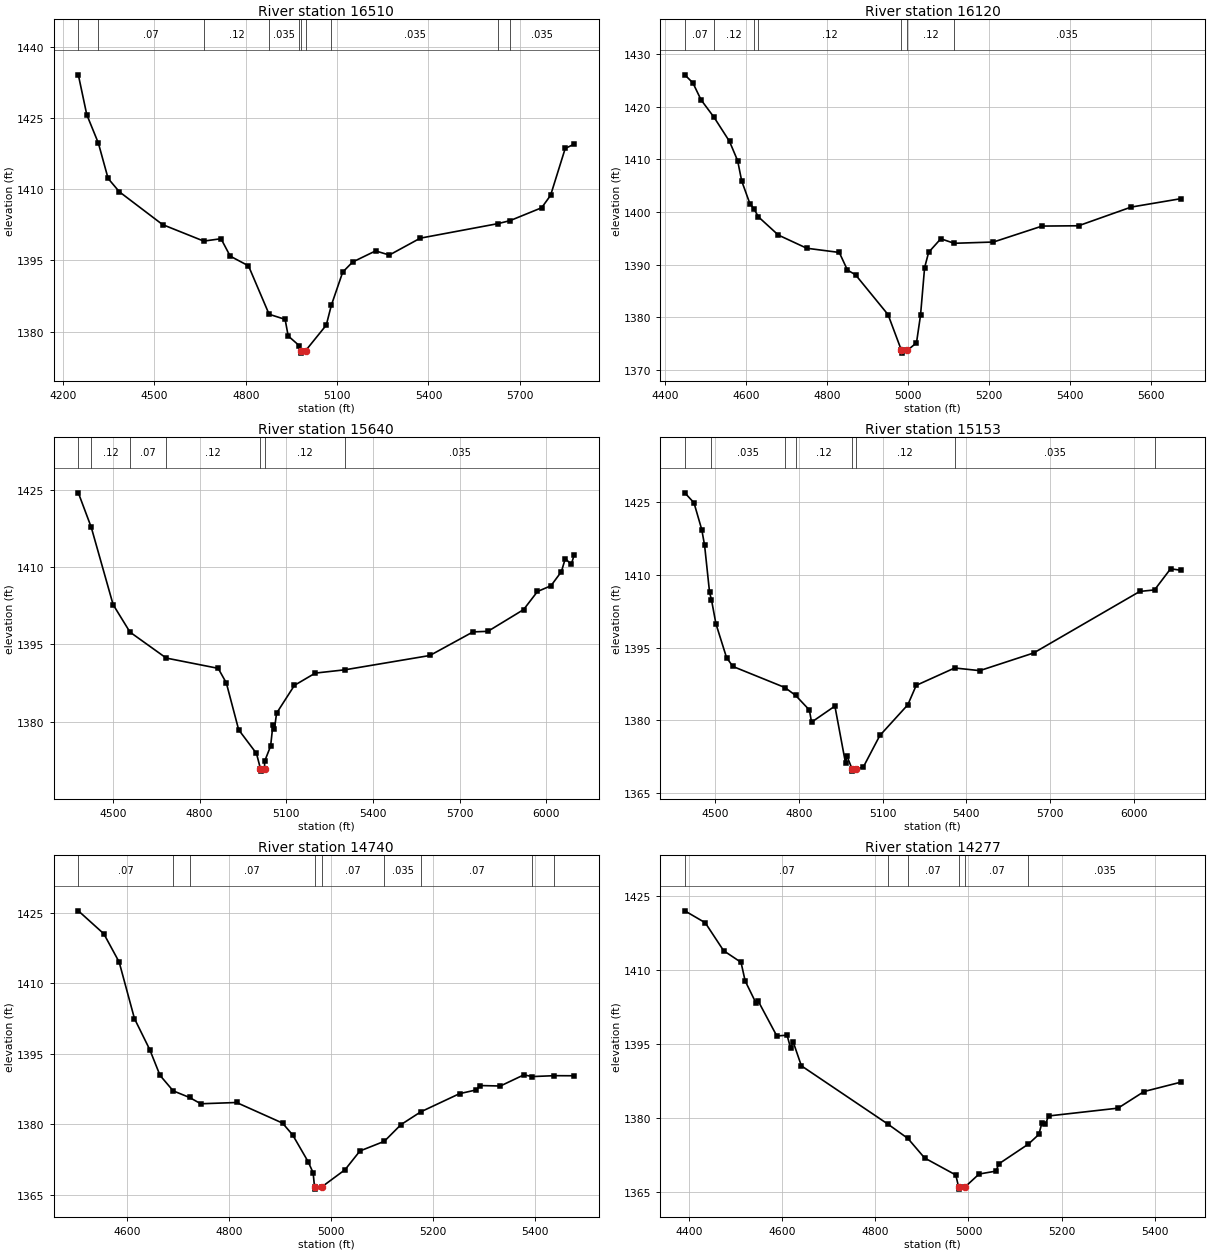
Type RM Length L Ch R = 1 ,16510   ,390,390,390
BEGIN DESCRIPTION:
SHEPS CREEK 30.0
END DESCRIPTION:
XS GIS Cut Line= 3
      2102172.59     13909349.55      2101427.79     13909297.46
      2100611.06      13909630.4
#Sta/Elev= 30
    4250 1434.16  4277.7 1425.76  4315.9 1419.74  4347.8  1412.3  4384.9 1409.48
  4526.7 1402.57  4661.9 1399.09  4718.7 1399.59  4748.8 1395.92  4808.9 1393.87
  4876.6 1383.66  4929.2 1382.58  4939.3 1379.08  4975.2 1377.06  4982.4 1375.96
  4982.9 1375.46  4996.3 1375.96  5064.4 1381.37    5081 1385.55  5118.4 1392.55
  5150.8 1394.67  5226.4 1397.02  5271.6 1396.15  5373.2 1399.71    5628 1402.77
  5667.8  1403.4  5771.7 1406.12  5801.1 1408.73  5849.2 1418.63  5878.6 1419.54
#Mann= 10 ,-1 , 0
    4250     .12       0  4315.9     .07       0  4661.9     .12       0
  4876.6    .035       0  4975.2     .12       0  4982.4     .05       0
  4996.3     .12       0    5081    .035       0    5628     .12       0
  5667.8    .035       0
Bank Sta=4982.4,4996.3
XS Rating Curve= 0 ,0
Exp/Cntr=0.3,0.1

Type RM Length L Ch R = 1 ,16120   ,480,480,480
BEGIN DESCRIPTION:
SHEPS CREEK 29.0
END DESCRIPTION:
XS GIS Cut Line= 3
      2102024.96       13908975.        2101475.       13908925.
      2100802.78     13908932.88
#Sta/Elev= 30
  4448.1 1426.06  4468.1 1424.53  4488.2 1421.31  4520.5 1417.97  4558.5 1413.41
  4578.6 1409.74  4588.6 1405.89  4608.7 1401.61  4618.7 1400.62  4629.8 1399.08
    4679 1395.62  4749.3 1393.11  4829.6 1392.31  4849.7 1388.97  4869.8 1388.06
  4950.1 1380.49  4983.2 1373.68  4983.7 1373.18  4997.4 1373.68  5020.3 1375.14
  5030.3 1380.41  5040.3 1389.41  5050.3 1392.34  5080.3 1394.91  5113.3 1394.05
  5210.3 1394.29  5330.4 1397.32  5420.4 1397.38  5550.4 1400.93  5672.6 1402.52
#Mann= 7 ,-1 , 0
  4448.1     .07       0  4520.5     .12       0  4618.7     .07       0
  4629.8     .12       0  4983.2     .05       0  4997.4     .12       0
  5113.3    .035       0
Bank Sta=4983.2,4997.4
XS Rating Curve= 0 ,0
Exp/Cntr=0.3,0.1

Type RM Length L Ch R = 1 ,15640   ,487,487,487
BEGIN DESCRIPTION:
SHEPS CREEK 28.0
END DESCRIPTION:
XS GIS Cut Line= 3
      2102094.41     13908802.65        2101575.       13908475.
      2100505.18     13908740.13
#Sta/Elev= 30
  4380.5 1424.37  4425.3 1417.68  4500.9 1402.71  4559.3 1397.39  4684.9 1392.36
  4864.6 1390.37  4892.8 1387.54  4935.5 1378.47  4997.2 1373.88  5010.7 1370.96
  5011.2 1370.46    5025 1370.96  5025.5 1372.38  5046.1 1375.31  5054.1 1379.43
  5059.3 1378.57  5066.7 1381.68  5128.6 1387.08  5200.7 1389.45  5303.6 1390.09
  5597.4 1392.86  5746.7 1397.43  5798.2 1397.54  5921.8 1401.75  5969.9 1405.26
  6016.4 1406.36  6052.7 1409.11  6066.1 1411.64  6086.7 1410.49  6096.8 1412.33
#Mann= 7 ,-1 , 0
  4380.5    .035       0  4425.3     .12       0  4559.3     .07       0
  4684.9     .12       0  5010.7     .05       0    5025     .12       0
  5303.6    .035       0
Bank Sta=5010.7,5025
XS Rating Curve= 0 ,0
Exp/Cntr=0.3,0.1

Type RM Length L Ch R = 1 ,15153   ,413,413,413
BEGIN DESCRIPTION:
SHEPS CREEK 27.0
END DESCRIPTION:
XS GIS Cut Line= 3
      2102274.98       13907925.        2101675.       13908025.
        2100509.      13907986.1
#Sta/Elev= 30
  4391.9 1426.95  4424.8 1424.89  4452.7 1419.34  4462.8 1416.09  4480.6 1406.38
  4487.2 1404.93  4503.4 1399.91  4541.4 1392.93  4564.2 1391.11    4750 1386.77
  4788.6 1385.14  4837.9 1382.12  4845.6 1379.61  4929.2 1382.93  4967.2 1371.18
  4972.3 1372.63  4990.3 1370.01  4990.8 1369.51  5004.9 1370.01  5030.2 1370.27
  5090.2 1376.87  5190.3 1383.21  5220.3 1387.21    5358  1390.8  5447.7 1390.25
  5640.5 1393.89  6020.7  1406.6  6073.4 1406.91  6130.8 1411.27  6166.8 1410.98
#Mann= 8 ,-1 , 0
  4391.9     .12       0  4487.2    .035       0    4750     .07       0
  4788.6     .12       0  4990.3     .05       0  5004.9     .12       0
    5358    .035       0  6073.4     .12       0
Bank Sta=4990.3,5004.9
XS Rating Curve= 0 ,0
Exp/Cntr=0.3,0.1

Type RM Length L Ch R = 1 ,14740   ,463,463,463
BEGIN DESCRIPTION:
SHEPS CREEK 26.0
END DESCRIPTION:
XS GIS Cut Line= 3
      2102174.97       13907675.        2101675.       13907675.
      2101219.74     13907797.39
#Sta/Elev= 30
  4504.6 1425.45  4554.6 1420.55  4584.6 1414.54  4614.6  1402.5  4644.6 1395.89
  4664.6 1390.43  4690.4 1387.13  4722.4 1385.72  4744.6 1384.38  4814.6 1384.65
  4904.6 1380.27  4924.6 1377.73  4954.6 1372.09  4964.6  1369.7  4967.3 1366.71
  4967.8 1366.21  4981.9 1366.71  5027.1 1370.34  5056.3 1374.33  5104.1 1376.39
  5136.7 1379.94  5175.5 1382.66  5251.4 1386.53  5284.2 1387.33  5291.4 1388.26
  5331.4 1388.16  5377.4 1390.53    5394 1390.17  5437.4 1390.36    5476 1390.34
#Mann= 9 ,-1 , 0
  4504.6     .07       0  4690.4    .035       0  4722.4     .07       0
  4967.3     .05       0  4981.9     .07       0  5104.1    .035       0
  5175.5     .07       0    5394    .035       0  5437.4     .07       0
Bank Sta=4967.3,4981.9
XS Rating Curve= 0 ,0
Exp/Cntr=0.3,0.1

Type RM Length L Ch R = 1 ,14277   ,486,486,486
BEGIN DESCRIPTION:
SHEPS CREEK 25.0
END DESCRIPTION:
XS GIS Cut Line= 3
      2102174.97     13907474.98        2101625.       13907225.
      2101324.99     13907575.01
#Sta/Elev= 30
  4390.6 1421.92  4434.5 1419.51    4474 1413.86  4511.4 1411.51  4520.2 1407.76
  4543.2 1403.34  4548.7  1403.6  4588.3 1396.62  4610.3 1396.78  4617.9 1394.15
  4623.4 1395.42    4641 1390.59  4826.8 1378.81  4869.9  1375.9  4905.7 1371.96
  4972.7 1368.52  4978.6 1366.16  4979.1 1365.66  4993.3 1366.16  5022.7 1368.71
  5058.9  1369.3  5065.5 1370.79  5128.6 1374.76  5151.1 1376.71  5157.7 1379.02
  5165.4 1378.79    5172 1380.45  5321.2 1382.03  5377.2 1385.39  5455.7 1387.27
#Mann= 6 ,-1 , 0
  4390.6     .07       0  4826.8    .035       0  4869.9     .07       0
  4978.6     .05       0  4993.3     .07       0  5128.6    .035       0
Bank Sta=4978.6,4993.3
XS Rating Curve= 0 ,0
Exp/Cntr=0.3,0.1

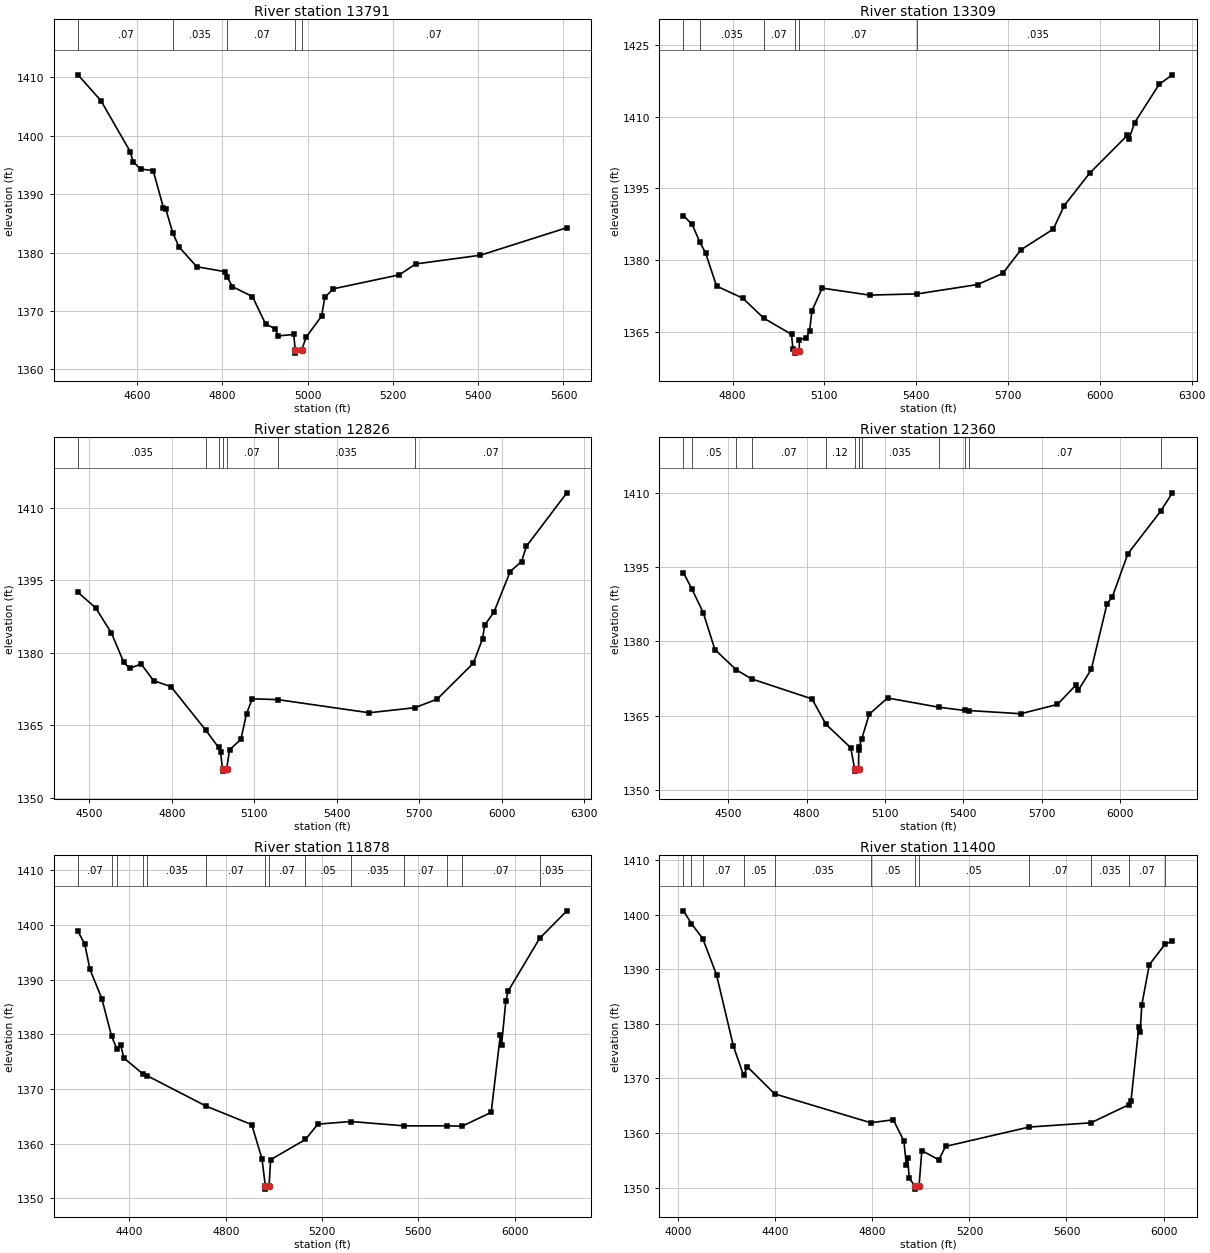
Type RM Length L Ch R = 1 ,13791   ,482,482,482
BEGIN DESCRIPTION:
SHEPS CREEK 24.0
END DESCRIPTION:
XS GIS Cut Line= 3
      2102124.99       13906975.        2101625.       13906775.
      2101024.98       13906875.
#Sta/Elev= 30
  4461.1 1410.42  4514.9    1406  4583.6 1397.29  4590.3 1395.57  4607.8 1394.29
  4637.5 1394.04  4661.7 1387.62  4667.1 1387.46  4683.3 1383.39    4698 1380.98
  4739.8 1377.58  4805.7 1376.74  4811.8 1375.76  4823.2 1374.18  4870.4 1372.48
  4901.3 1367.77  4924.2 1366.96  4930.9 1365.74  4967.3    1366  4970.7  1363.3
  4971.2  1362.8  4985.5  1363.3  4996.9 1365.59  5032.6 1369.15  5040.2 1372.37
  5060.4 1373.81    5215  1376.2  5253.1 1378.06  5405.1 1379.55  5607.9 1384.26
#Mann= 5 ,-1 , 0
  4461.1     .07       0  4683.3    .035       0  4811.8     .07       0
  4970.7     .05       0  4985.5     .07       0
Bank Sta=4970.7,4985.5
XS Rating Curve= 0 ,0
Exp/Cntr=0.3,0.1

Type RM Length L Ch R = 1 ,13309   ,483,483,483
BEGIN DESCRIPTION:
SHEPS CREEK 23.0
END DESCRIPTION:
XS GIS Cut Line= 3
      2102024.97     13906524.98        2101725.       13906325.
      2100525.04     13906025.01
#Sta/Elev= 30
  4639.5 1389.25    4668 1387.41  4692.5 1383.77  4711.6 1381.48  4747.6 1374.52
  4833.3 1371.99  4901.7 1367.81  4992.5 1364.42    4997 1361.43  5002.9 1360.99
  5003.4 1360.49  5017.7 1360.99  5018.1  1363.3  5041.2 1363.68  5051.6 1365.18
  5059.3 1369.34  5092.8 1374.09  5247.4 1372.63  5404.1 1372.89  5600.4 1374.84
  5682.9 1377.17  5742.2 1382.12  5847.8 1386.43  5883.9 1391.37  5966.4 1398.12
  6090.1 1406.07  6095.2 1405.22  6113.3 1408.68  6194.1 1416.75  6236.9 1418.72
#Mann= 7 ,-1 , 0
  4639.5     .07       0  4692.5    .035       0  4901.7     .07       0
  5002.9     .05       0  5017.7     .07       0  5404.1    .035       0
  6194.1     .07       0
Bank Sta=5002.9,5017.7
XS Rating Curve= 0 ,0
Exp/Cntr=0.3,0.1

Type RM Length L Ch R = 1 ,12826   ,466,466,466
BEGIN DESCRIPTION:
SHEPS CREEK 22.0
END DESCRIPTION:
XS GIS Cut Line= 3
      2102274.97     13906174.98        2101825.       13905875.
      2100625.03     13905575.01
#Sta/Elev= 30
  4459.2 1392.48  4523.8 1389.26  4580.8 1384.08  4625.9 1378.01    4647 1376.79
    4689 1377.68  4734.1 1374.25  4797.2 1373.02  4923.8 1364.03  4970.2 1360.47
  4977.5 1359.51  4984.9 1356.07  4985.4 1355.57    5000 1356.07  5010.3 1359.95
  5051.5 1362.14  5072.1 1367.43  5092.8  1370.5  5185.1 1370.34    5518 1367.62
  5684.6 1368.67  5765.3 1370.44  5896.8 1377.85  5930.3 1382.88    5938 1385.71
  5971.5 1388.35  6030.8 1396.78    6072 1398.85    6090 1402.01  6236.9 1413.03
#Mann= 7 ,-1 , 0
  4459.2    .035       0  4923.8     .12       0  4970.2     .07       0
  4984.9     .05       0    5000     .07       0  5185.1    .035       0
  5684.6     .07       0
Bank Sta=4984.9,5000
XS Rating Curve= 0 ,0
Exp/Cntr=0.3,0.1

Type RM Length L Ch R = 1 ,12360   ,482,482,482
BEGIN DESCRIPTION:
SHEPS CREEK 21.0
END DESCRIPTION:
XS GIS Cut Line= 3
      2102475.02     13905725.01        2101875.       13905425.
      2100675.04       13905425.
#Sta/Elev= 30
  4328.8 1393.92  4360.4 1390.69  4404.3 1385.87    4449 1378.36  4530.9 1374.25
  4589.3 1372.42  4820.8 1368.36    4874 1363.22  4968.9 1358.47  4983.7 1354.23
  4984.2 1353.73  4998.8 1354.23  4999.5 1358.09  5001.3 1358.64  5010.5 1360.17
  5039.6 1365.26  5109.6 1368.55  5306.2 1366.68  5404.8 1366.02  5419.7 1366.01
  5619.6 1365.36  5759.6 1367.24  5829.6 1371.11  5839.6  1370.1  5889.6 1374.38
  5949.6 1387.62  5969.6 1388.99  6029.6 1397.79  6155.1 1406.41  6199.6 1410.12
#Mann= 14 ,-1 , 0
  4328.8     .07       0  4360.4     .05       0  4530.9    .035       0
  4589.3     .07       0    4874     .12       0  4983.7    .035       0
  4998.8     .12       0  4999.5    .035       0  5001.3     .12       0
  5010.5    .035       0  5306.2     .07       0  5404.8    .035       0
  5419.7     .07       0  6155.1    .035       0
Bank Sta=4983.7,4998.8
XS Rating Curve= 0 ,0
Exp/Cntr=0.3,0.1

Type RM Length L Ch R = 1 ,11878   ,478,478,478
BEGIN DESCRIPTION:
SHEPS CREEK 20.0
END DESCRIPTION:
XS GIS Cut Line= 3
        2102575.       13905525.        2101975.       13904975.
      2100774.99       13905175.
#Sta/Elev= 30
  4186.1 1398.84  4214.2 1396.49  4235.7  1391.9  4285.1 1386.53  4325.4 1379.69
  4347.7 1377.32  4362.8 1378.11  4376.9 1375.65  4456.8 1372.72    4472 1372.46
  4718.9 1366.85  4907.8 1363.48  4950.4 1357.22  4964.4 1352.18  4964.9 1351.68
  4979.6 1352.18  4986.2 1357.07  5130.7 1360.76  5182.5 1363.57  5319.5 1364.05
  5541.3 1363.25  5719.2 1363.26  5781.6 1363.19  5902.3 1365.72  5940.3 1379.85
  5945.4 1378.02  5963.1 1386.12  5973.3 1387.95  6103.3 1397.54  6216.6 1402.59
#Mann= 14 ,-1 , 0
  4186.1     .07       0  4325.4     .05       0  4347.7     .07       0
  4456.8     .05       0    4472    .035       0  4718.9     .07       0
  4964.4     .05       0  4979.6     .07       0  5130.7     .05       0
  5319.5    .035       0  5541.3     .07       0  5719.2    .035       0
  5781.6     .07       0  6103.3    .035       0
Bank Sta=4964.4,4979.6
XS Rating Curve= 0 ,0
Exp/Cntr=0.3,0.1

Type RM Length L Ch R = 1 ,11400   ,473,473,473
BEGIN DESCRIPTION:
SHEPS CREEK 19.0
END DESCRIPTION:
XS GIS Cut Line= 3
      2102775.04     13904925.02        2101875.       13904525.
      2100974.99       13905025.
#Sta/Elev= 30
  4021.7 1400.68  4054.7 1398.33  4101.1  1395.6  4157.8 1388.99  4227.6 1375.89
  4269.4 1370.56  4285.1 1372.14  4397.5 1367.18  4793.1  1361.9  4886.3 1362.44
    4930 1358.56  4940.3 1354.08  4945.8 1355.37  4951.9 1351.73  4977.1 1350.25
  4977.6 1349.75  4992.3 1350.25  5003.9  1356.8  5074.1 1355.11  5101.6 1357.57
  5445.9 1361.11  5700.1 1361.88  5856.2 1365.18  5865.7 1365.84  5897.8 1379.33
  5903.5 1378.55  5910.4 1383.47  5941.2  1390.8  6007.8 1394.67  6036.2 1395.07
#Mann= 12 ,-1 , 0
  4021.7     .07       0  4054.7     .12       0  4101.1     .07       0
  4269.4     .05       0  4397.5    .035       0  4793.1     .05       0
  4977.1     .05       0  4992.3     .05       0  5445.9     .07       0
  5700.1    .035       0  5856.2     .07       0  6007.8    .035       0
Bank Sta=4977.1,4992.3
XS Rating Curve= 0 ,0
Exp/Cntr=0.3,0.1

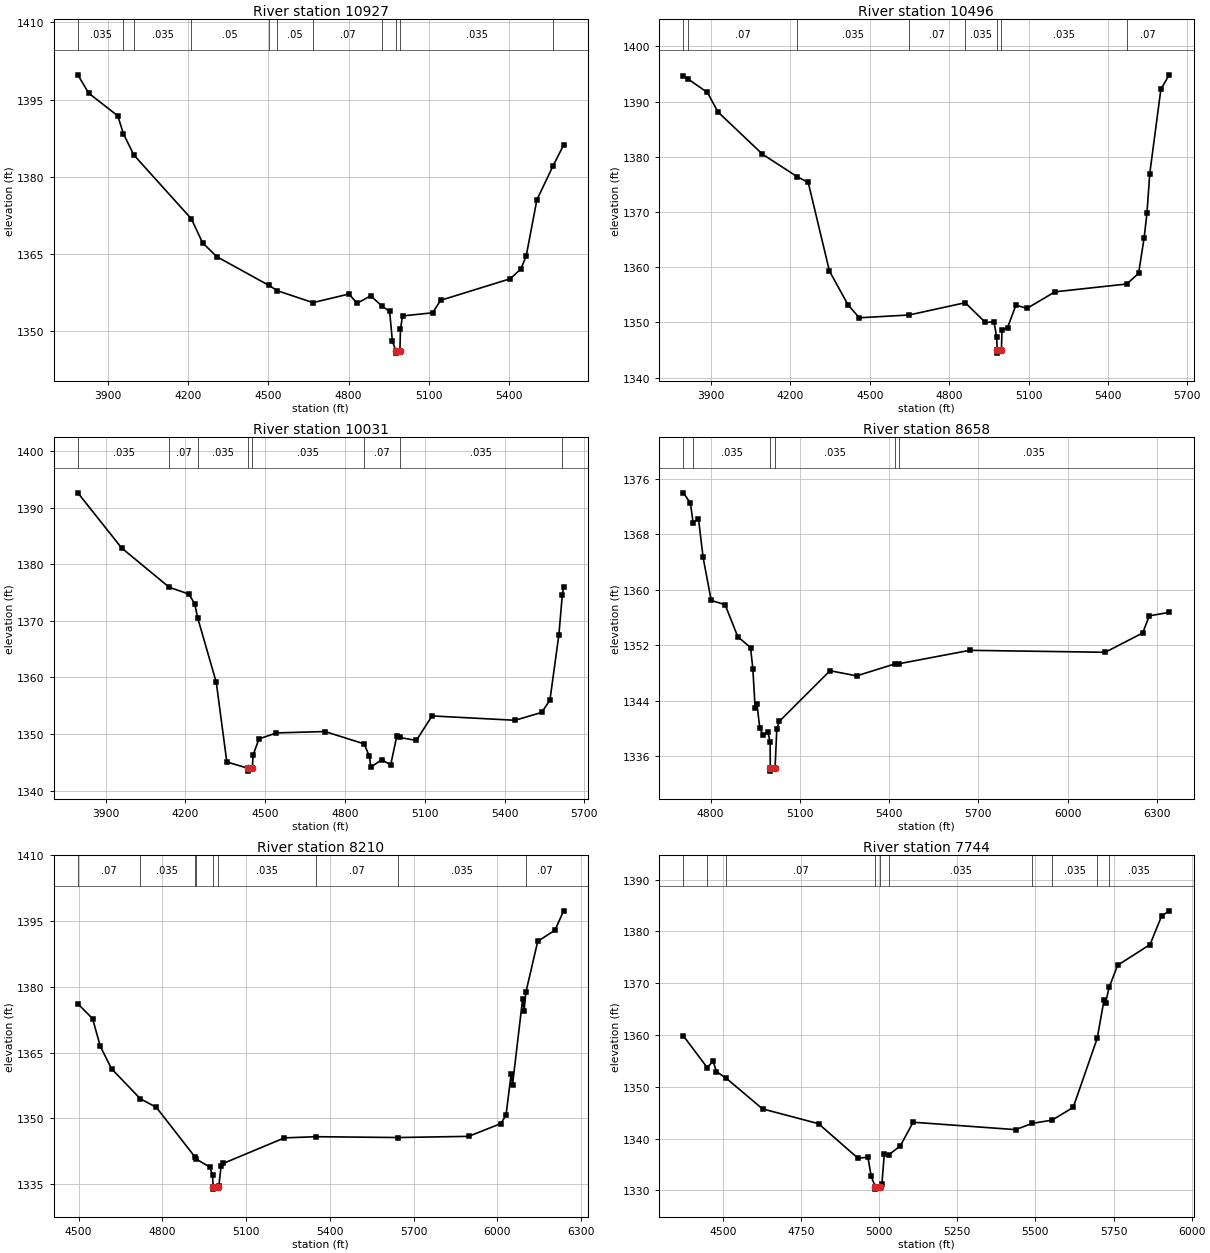
Type RM Length L Ch R = 1 ,10927   ,431,431,431
BEGIN DESCRIPTION:
SHEPS CREEK 18.0
END DESCRIPTION:
XS GIS Cut Line= 3
      2102874.99       13903925.        2101675.       13904125.
      2101075.05       13904125.
#Sta/Elev= 30
  3787.7 1399.81  3828.2 1396.25  3937.2 1391.82  3958.3 1388.32    3997 1384.23
  4212.5 1371.78    4254 1367.14  4307.3 1364.44  4502.8 1358.84  4533.9 1357.82
  4666.7  1355.5  4801.5 1357.18  4831.9 1355.38  4882.6 1356.82  4926.3 1354.78
  4953.6 1353.78  4963.7 1348.09  4976.1 1346.18  4976.6 1345.68  4991.9 1346.18
  4994.1 1350.31  5001.7 1352.92  5114.2 1353.52  5144.2 1355.95  5404.2 1360.14
  5444.2 1362.03  5464.2 1364.58  5504.2 1375.51  5564.5 1382.09  5604.2 1386.16
#Mann= 11 ,-1 , 0
  3787.7    .035       0  3958.3     .07       0    3997    .035       0
  4212.5     .05       0  4502.8     .07       0  4533.9     .05       0
  4666.7     .07       0  4926.3    .035       0  4976.1    .035       0
  4991.9    .035       0  5564.5     .07       0
Bank Sta=4976.1,4991.9
XS Rating Curve= 0 ,0
Exp/Cntr=0.3,0.1

Type RM Length L Ch R = 1 ,10496   ,465,465,465
BEGIN DESCRIPTION:
SHEPS CREEK 17.0
END DESCRIPTION:
XS GIS Cut Line= 3
      2102775.03       13903825.        2101575.       13903725.
      2100975.04     13903924.99
#Sta/Elev= 30
  3795.4 1394.58  3810.8 1394.15  3885.7 1391.67  3925.9 1388.13    4094 1380.48
  4225.5  1376.4  4267.1 1375.37  4347.3 1359.32  4417.6  1353.2  4460.2 1350.85
  4648.9 1351.36  4860.8 1353.58  4936.9    1350  4969.5 1350.11  4979.5 1347.37
  4981.7 1344.95  4982.2 1344.45  4997.5 1344.95  4999.6 1348.68  5020.7 1349.06
  5052.3 1353.14  5094.5 1352.56  5199.9 1355.55  5471.4 1356.97  5516.1  1358.9
  5537.2 1365.39  5547.7 1369.79  5558.3 1376.98  5600.4 1392.26    5632 1394.85
#Mann= 8 ,-1 , 0
  3795.4    .035       0  3810.8     .07       0  4225.5    .035       0
  4648.9     .07       0  4860.8    .035       0  4981.7    .035       0
  4997.5    .035       0  5471.4     .07       0
Bank Sta=4981.7,4997.5
XS Rating Curve= 0 ,0
Exp/Cntr=0.3,0.1

Type RM Length L Ch R = 1 ,10031   ,1373,1373,1373
BEGIN DESCRIPTION:
SHEPS CREEK 16.0
END DESCRIPTION:
XS GIS Cut Line= 3
      2102724.97     13903774.98        2101625.       13903275.
      2101025.03     13903424.99
#Sta/Elev= 30
  3795.5  1392.6  3960.2 1382.86  4139.1 1375.92  4212.9 1374.72  4234.8 1373.02
  4245.9 1370.56  4316.1 1359.12  4355.7 1345.07  4435.7 1343.95  4436.2 1343.45
  4451.5 1343.95  4454.5 1346.28  4476.5 1349.14  4542.4  1350.2  4724.8 1350.44
  4872.2 1348.26  4891.7 1346.09  4897.2 1344.16  4937.9 1345.45  4971.9 1344.57
    4995 1349.69  5005.3  1349.4  5068.2 1348.87  5127.5  1353.2  5439.3 1352.43
  5539.8 1353.82  5570.7 1356.02  5604.2  1367.5  5617.1 1374.53  5622.2  1375.9
#Mann= 8 ,-1 , 0
  3795.5    .035       0  4139.1     .07       0  4245.9    .035       0
  4435.7     .05       0  4451.5    .035       0  4872.2     .07       0
  5005.3    .035       0  5617.1     .07       0
Bank Sta=4435.7,4451.5
XS Rating Curve= 0 ,0
Exp/Cntr=0.3,0.1

Type RM Length L Ch R = 1 ,8658    ,448,448,448
BEGIN DESCRIPTION:
SHEPS CREEK 15.0
END DESCRIPTION:
XS GIS Cut Line= 3
      2102525.03     13902825.02        2102275.       13902675.
      2101075.02     13903274.99
#Sta/Elev= 30
  4708.8 1373.96  4732.2 1372.46  4741.5 1369.63  4759.4 1370.24  4774.9 1364.64
  4802.1 1358.45  4848.8 1357.84  4891.5 1353.22  4934.3 1351.66  4942.1 1348.64
  4949.8 1342.93  4955.7 1343.58  4965.4  1340.1  4977.1    1339  4992.6 1339.52
  5000.4    1338  5000.6 1334.35  5001.1 1333.85  5016.9 1334.35  5022.7 1339.96
  5031.1 1341.02  5201.6 1348.32  5291.1 1347.58  5420.2 1349.31  5434.8 1349.34
  5671.2 1351.26  6126.8 1350.98  6252.6 1353.76  6274.9 1356.23    6342 1356.73
#Mann= 6 ,-1 , 0
  4708.8     .07       0  4741.5    .035       0  5000.6    .035       0
  5016.9    .035       0  5420.2     .07       0  5434.8    .035       0
Bank Sta=5000.6,5016.9
XS Rating Curve= 0 ,0
Exp/Cntr=0.3,0.1

Type RM Length L Ch R = 1 ,8210    ,466,466,466
BEGIN DESCRIPTION:
SHEPS CREEK 14.0
END DESCRIPTION:
XS GIS Cut Line= 3
      2102625.05       13902325.        2102125.       13902275.
      2100924.97     13902575.01
#Sta/Elev= 30
  4497.5 1376.12  4550.3 1372.74  4577.9 1366.43  4618.1 1361.31  4720.6 1354.49
  4778.9 1352.48  4915.7 1341.28    4919 1340.77  4969.9 1338.89  4979.9 1336.98
  4981.7 1334.34  4982.2 1333.84  4998.2 1334.34  5002.6 1334.63  5010.3 1339.08
  5018.1  1339.7  5237.1 1345.53  5349.9  1345.8  5643.9 1345.61  5896.8 1345.88
  6012.8 1348.81  6030.8 1350.79  6048.9 1360.04    6054 1357.69  6090.1  1377.2
  6095.2 1374.56  6101.6  1378.7  6144.2 1390.37    6206 1392.92    6237 1397.33
#Mann= 9 ,-1 , 0
  4497.5     .07       0  4720.6    .035       0  4915.7     .07       0
    4919    .035       0  4981.7    .035       0  4998.2    .035       0
  5349.9     .07       0  5643.9    .035       0  6101.6     .07       0
Bank Sta=4981.7,4998.2
XS Rating Curve= 0 ,0
Exp/Cntr=0.3,0.1

Type RM Length L Ch R = 1 ,7744    ,484,484,484
BEGIN DESCRIPTION:
SHEPS CREEK 13.0
END DESCRIPTION:
XS GIS Cut Line= 3
      2102525.04     13902075.01        2101925.       13901875.
      2101024.96     13902075.01
#Sta/Elev= 30
  4373.8 1359.83  4450.2 1353.69  4468.7 1354.99  4479.3 1352.94  4510.6 1351.66
  4626.8 1345.74    4806 1342.88  4932.5  1336.2  4964.1 1336.41  4974.7 1332.68
  4987.5 1330.74    4988 1330.24    5004 1330.74  5008.9 1331.29  5016.5 1337.05
  5032.2 1336.92  5067.8  1338.6  5108.7 1343.16  5436.5 1341.73    5490 1342.94
  5553.6 1343.57  5620.9 1346.02  5697.7 1359.35  5719.5 1366.74  5724.7 1366.28
  5736.1 1369.24  5763.1 1373.48  5866.8 1377.47  5903.9    1383  5928.3 1383.99
#Mann= 10 ,-1 , 0
  4373.8     .07       0  4450.2    .035       0  4510.6     .07       0
  4987.5     .05       0    5004     .07       0  5032.2    .035       0
    5490     .07       0  5553.6    .035       0  5697.7     .07       0
  5736.1    .035       0
Bank Sta=4987.5,5004
XS Rating Curve= 0 ,0
Exp/Cntr=0.3,0.1

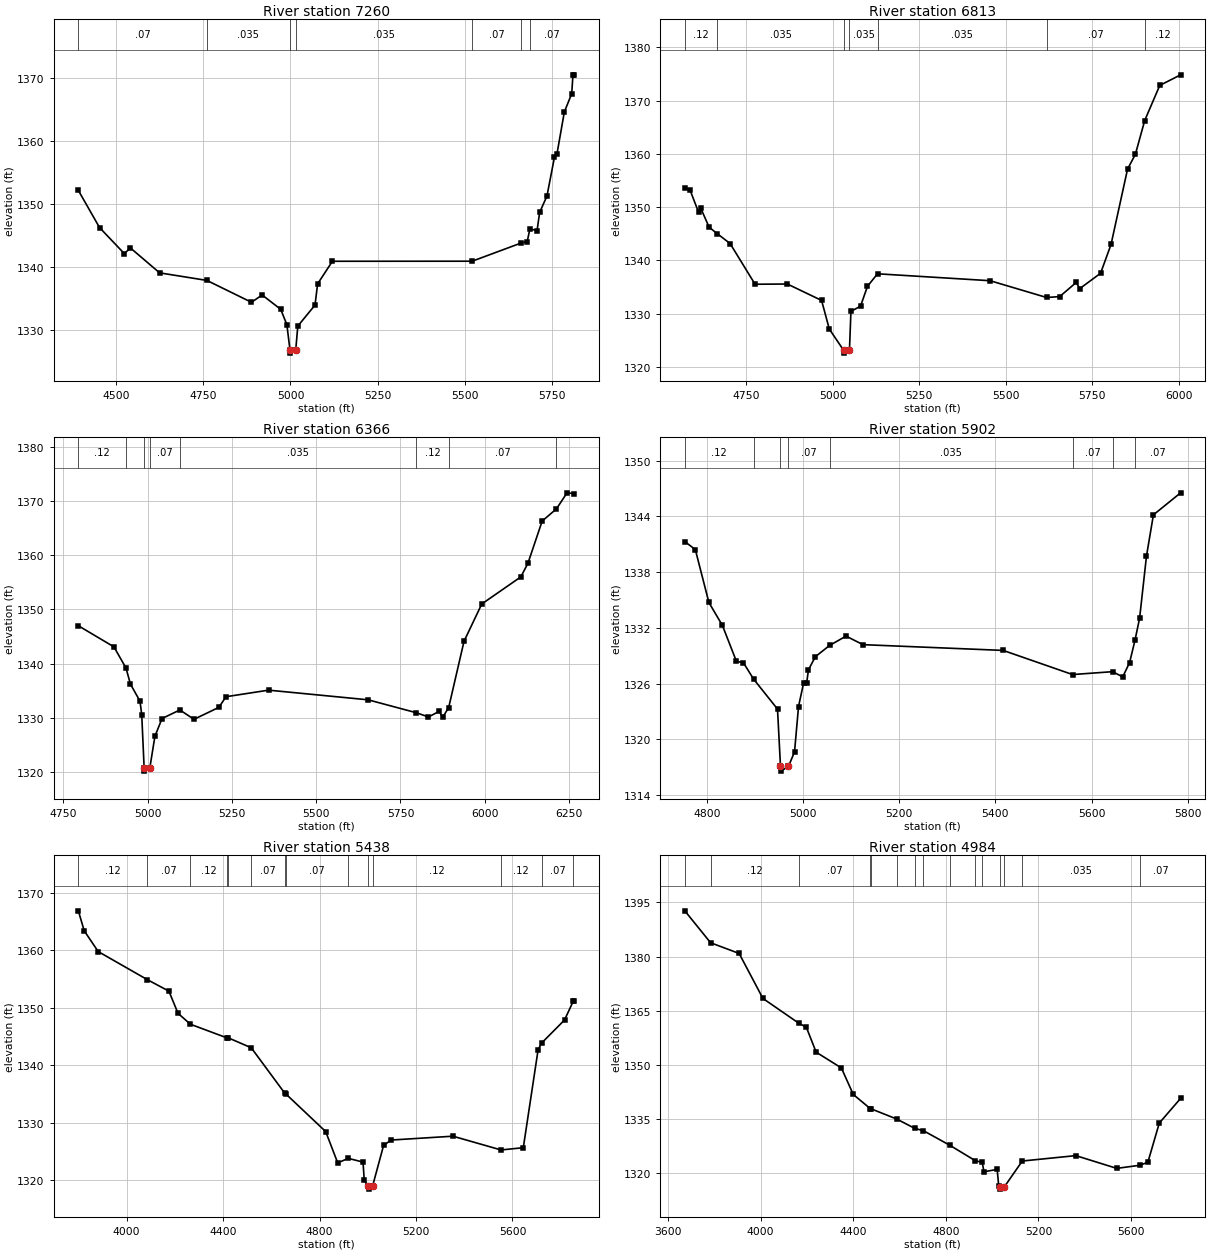
Type RM Length L Ch R = 1 ,7260    ,447,447,447
BEGIN DESCRIPTION:
SHEPS CREEK 12.0
END DESCRIPTION:
XS GIS Cut Line= 3
      2102424.98       13901525.        2101825.       13901425.
        2101225.       13901975.
#Sta/Elev= 30
  4391.6 1352.13  4452.4 1346.23  4523.4  1342.1  4541.1 1342.99  4624.8 1339.04
  4760.3 1337.84  4888.3 1334.37  4918.8 1335.53    4972 1333.26  4989.7 1330.83
  4998.7  1326.8  4999.2  1326.3  5015.2  1326.8  5021.1 1330.59  5070.5 1333.93
  5077.9 1337.29  5120.4 1340.88  5521.3 1340.89  5660.4 1343.75  5679.1    1344
  5686.8    1346  5707.4 1345.76  5714.8 1348.63  5735.8 1351.24  5757.4 1357.43
  5764.2 1357.83  5785.7 1364.59  5806.7 1367.46  5810.4 1370.47  5813.8 1370.47
#Mann= 7 ,-1 , 0
  4391.6     .07       0  4760.3    .035       0  4998.7    .035       0
  5015.2    .035       0  5521.3     .07       0  5660.4    .035       0
  5686.8     .07       0
Bank Sta=4998.7,5015.2
XS Rating Curve= 0 ,0
Exp/Cntr=0.3,0.1

Type RM Length L Ch R = 1 ,6813    ,447,447,447
BEGIN DESCRIPTION:
SHEPS CREEK 11.0
END DESCRIPTION:
XS GIS Cut Line= 3
      2102474.98     13901274.99        2102075.       13901125.
      2101074.97       13901025.
#Sta/Elev= 30
  4573.1 1353.54  4588.2 1353.23  4613.1 1349.01  4618.5 1349.91  4643.4 1346.24
  4666.8 1345.03  4703.9 1343.18    4776 1335.54  4869.4 1335.58  4968.2  1332.5
  4990.5 1327.13  5032.2 1323.11  5032.7 1322.61  5048.7 1323.11    5053 1330.45
  5080.7 1331.42  5100.8 1335.16  5129.8  1337.5    5455  1336.2  5618.2 1333.05
    5656 1333.22  5703.8 1335.88  5713.8 1334.71  5774.1  1337.6  5804.3 1343.01
    5852 1357.15  5874.6 1359.92  5901.5 1366.25    5945 1372.85  6005.3 1374.84
#Mann= 7 ,-1 , 0
  4573.1     .12       0  4666.8    .035       0  5032.2    .035       0
  5048.7    .035       0  5129.8    .035       0  5618.2     .07       0
  5901.5     .12       0
Bank Sta=5032.2,5048.7
XS Rating Curve= 0 ,0
Exp/Cntr=0.3,0.1

Type RM Length L Ch R = 1 ,6366    ,464,464,464
BEGIN DESCRIPTION:
SHEPS CREEK 10.0
END DESCRIPTION:
XS GIS Cut Line= 3
      2102574.99       13900875.        2102375.       13900825.
      2101174.96     13900424.99
#Sta/Elev= 30
  4794.3 1346.98  4899.9 1343.09  4935.6  1339.2  4948.9 1336.23  4977.3 1333.07
  4982.4 1330.59  4989.6 1320.69  4990.1 1320.19  5006.2 1320.69  5021.5  1326.6
  5042.6 1329.88  5095.5 1331.46  5137.5 1329.74  5211.3 1331.94  5232.4  1333.9
  5358.8 1335.11    5654 1333.33    5797 1330.95  5833.2 1330.17  5864.8  1331.2
  5875.3 1330.11  5893.1  1331.9  5938.6 1344.11  5991.3 1350.99  6107.2 1355.98
  6128.3  1358.5  6170.5 1366.27  6212.9 1368.52  6244.3 1371.47  6265.4 1371.32
#Mann= 8 ,-1 , 0
  4794.3     .12       0  4935.6     .07       0  4989.6     .05       0
  5006.2     .07       0  5095.5    .035       0    5797     .12       0
  5893.1     .07       0  6212.9     .12       0
Bank Sta=4989.6,5006.2
XS Rating Curve= 0 ,0
Exp/Cntr=0.3,0.1

Type RM Length L Ch R = 1 ,5902    ,464,464,464
BEGIN DESCRIPTION:
SHEPS CREEK 9.0
END DESCRIPTION:
XS GIS Cut Line= 3
      2102625.04     13900525.03        2102425.       13900375.
      2101824.98     13899874.98
#Sta/Elev= 30
  4754.2 1341.29  4776.1 1340.43  4804.3 1334.73  4832.4 1332.26  4861.5  1328.4
  4876.1 1328.24  4897.3 1326.48    4947 1323.25  4953.2 1317.07  4953.7 1316.57
  4969.8 1317.07  4982.4 1318.65  4990.7 1323.52  5001.1 1326.03  5007.5 1326.03
  5011.4 1327.49  5025.7 1328.89  5055.2  1330.1  5089.5 1331.11  5124.7 1330.19
  5416.2 1329.57  5560.6 1326.97  5643.7 1327.28  5664.9 1326.72  5679.2 1328.26
  5690.5 1330.69    5700 1333.04  5714.3 1339.73  5728.7 1344.17  5785.3 1346.54
#Mann= 8 ,-1 , 0
  4754.2     .12       0  4897.3     .07       0  4953.2     .05       0
  4969.8     .07       0  5055.2    .035       0  5560.6     .07       0
  5643.7     .12       0  5690.5     .07       0
Bank Sta=4953.2,4969.8
XS Rating Curve= 0 ,0
Exp/Cntr=0.3,0.1

Type RM Length L Ch R = 1 ,5438    ,454,454,454
BEGIN DESCRIPTION:
SHEPS CREEK 8.0
END DESCRIPTION:
XS GIS Cut Line= 3
      2102995.49     13901118.18        2102625.       13899975.
      2101825.01     13899675.01
#Sta/Elev= 30
  3799.6 1366.87    3824  1363.4    3882 1359.79  4085.6 1354.91  4175.2 1352.91
  4212.9 1349.06  4264.3 1347.16  4414.4 1344.81  4422.1 1344.78  4516.6 1343.07
  4656.2 1335.14  4660.5 1335.03  4825.4  1328.5  4875.2 1323.06  4918.8 1323.85
  4980.1  1323.2  4985.3 1320.04  5002.6    1319  5003.1  1318.5  5019.6    1319
  5065.4 1326.09  5096.5 1327.03  5352.9  1327.7  5552.5 1325.31  5644.8  1325.7
  5706.2 1342.73    5721  1343.9  5815.7 1347.89  5852.8 1351.24  5855.7 1351.24
#Mann= 14 ,-1 , 0
  3799.6     .12       0  4085.6     .07       0  4264.3     .12       0
  4414.4     .07       0  4422.1     .12       0  4516.6     .07       0
  4656.2     .12       0  4660.5     .07       0  4918.8     .12       0
  5002.6     .05       0  5019.6     .12       0  5552.5     .12       0
    5721     .07       0  5852.8     .12       0
Bank Sta=5002.6,5019.6
XS Rating Curve= 0 ,0
Exp/Cntr=0.3,0.1

Type RM Length L Ch R = 1 ,4984    ,441,441,441
BEGIN DESCRIPTION:
SHEPS CREEK 7.0
END DESCRIPTION:
XS GIS Cut Line= 3
      2103891.92     13900294.17        2102775.       13899575.
      2102174.97     13899024.98
#Sta/Elev= 30
  3672.1 1392.68  3783.6 1383.82  3906.9 1380.85  4009.8 1368.35  4164.9 1361.48
  4197.4 1360.35  4239.6 1353.45  4348.6 1349.08    4400 1341.72  4473.1  1337.8
    4475 1337.78  4588.2 1334.88  4665.8  1332.3  4703.2 1331.66  4818.1 1327.58
  4927.3 1323.33  4957.2 1322.87  4964.8 1320.26  5021.8 1320.91  5028.6 1316.29
  5034.3 1315.94  5034.8 1315.44  5051.3 1315.94  5130.4 1323.24  5361.6 1324.74
  5538.5  1321.2    5639 1322.07    5673 1322.91  5722.3 1333.77  5814.5 1340.63
#Mann= 15 ,-1 , 0
  3672.1    .035       0  3783.6     .12       0  4164.9     .07       0
  4473.1     .12       0    4475     .07       0  4588.2     .12       0
  4665.8     .07       0  4703.2    .035       0  4818.1     .07       0
  4927.3    .035       0  4957.2     .07       0  5034.3     .05       0
  5051.3     .07       0  5130.4    .035       0    5639     .07       0
Bank Sta=5034.3,5051.3
XS Rating Curve= 0 ,0
Exp/Cntr=0.3,0.1

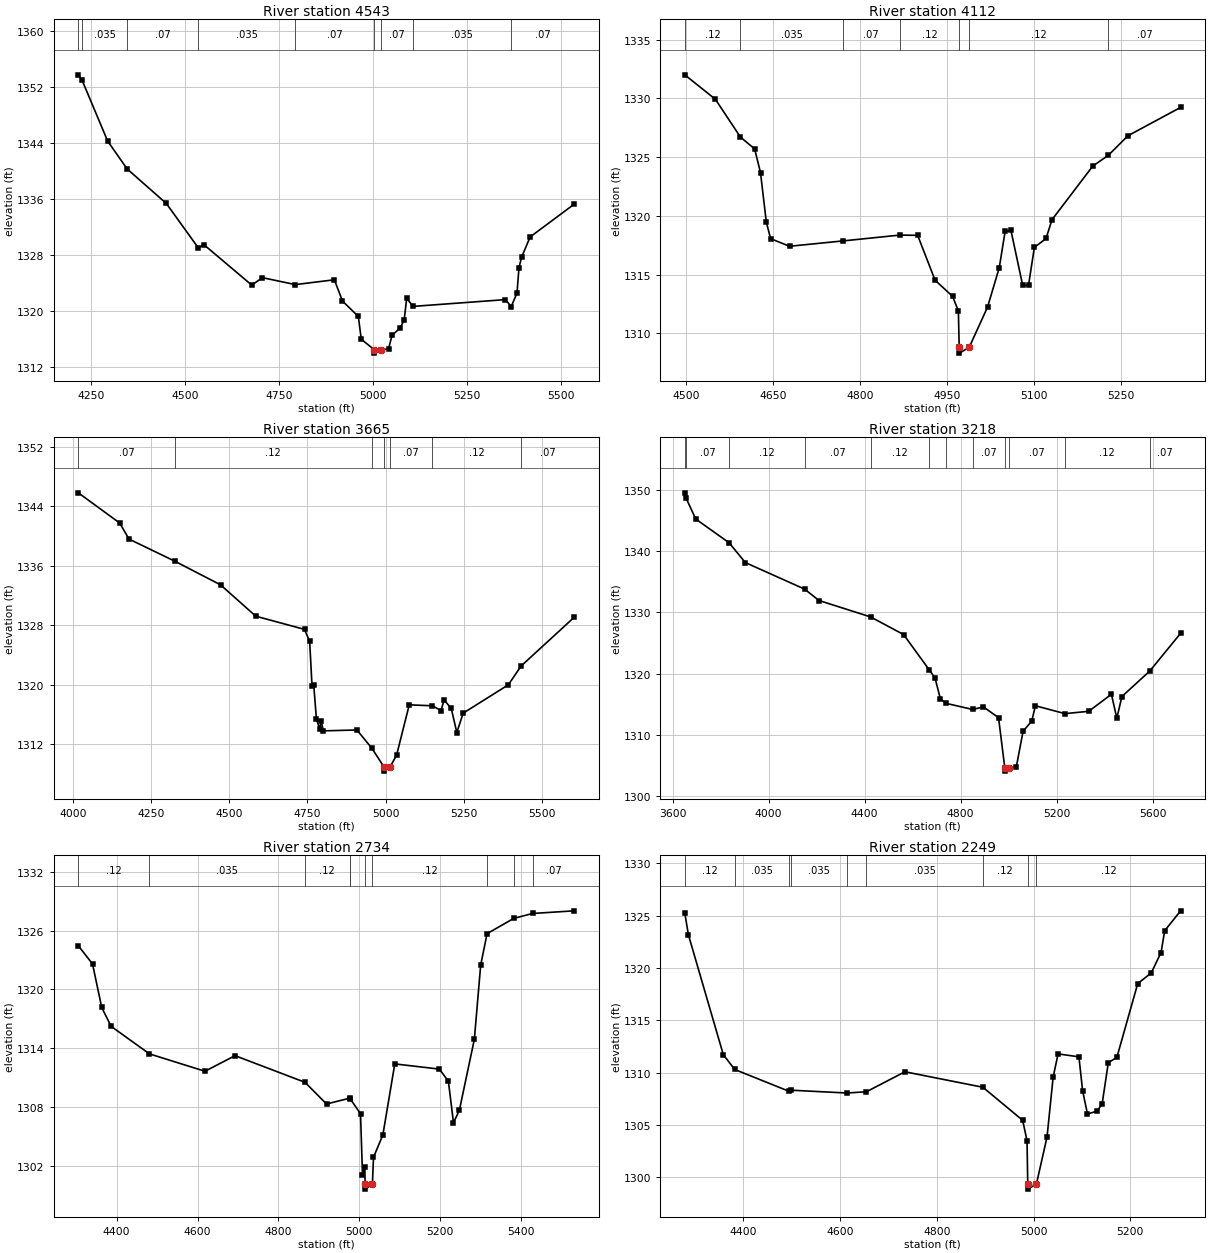
Type RM Length L Ch R = 1 ,4543    ,431,431,431
BEGIN DESCRIPTION:
SHEPS CREEK 6.0
END DESCRIPTION:
XS GIS Cut Line= 3
      2103425.01     13899675.01        2102825.       13899175.
      2102324.96     13898974.98
#Sta/Elev= 30
    4215 1353.79  4224.5 1353.08  4293.1  1344.3    4345 1340.31  4449.3 1335.37
  4534.4 1329.01  4548.9 1329.49  4676.5 1323.69  4705.1 1324.75  4792.7 1323.76
  4896.5 1324.45  4917.9 1321.41  4960.2  1319.2    4968 1315.94  5002.3 1314.45
  5002.8 1313.95  5019.4 1314.45  5040.5 1314.54  5049.9  1316.5  5071.4 1317.54
  5082.2  1318.7  5088.9 1321.79  5105.9 1320.64  5351.5 1321.61  5367.1 1320.62
  5382.4 1322.53  5387.8 1326.19  5394.5 1327.66  5417.4 1330.58  5534.6 1335.27
#Mann= 9 ,-1 , 0
    4215     .07       0  4224.5    .035       0    4345     .07       0
  4534.4    .035       0  4792.7     .07       0  5002.3     .05       0
  5019.4     .07       0  5105.9    .035       0  5367.1     .07       0
Bank Sta=5002.3,5019.4
XS Rating Curve= 0 ,0
Exp/Cntr=0.3,0.1

Type RM Length L Ch R = 1 ,4112    ,447,447,447
BEGIN DESCRIPTION:
SHEPS CREEK 5.0
END DESCRIPTION:
XS GIS Cut Line= 3
        2103325.       13898825.        2102825.       13898775.
      2102475.05     13898824.99
#Sta/Elev= 30
  4497.1    1332  4549.9 1329.92  4593.2  1326.7  4617.7  1325.7  4627.8 1323.68
  4637.8 1319.48  4645.3 1318.06    4678 1317.42  4769.5 1317.87  4868.3 1318.37
  4899.1 1318.35  4929.2 1314.53  4959.4 1313.16  4969.4 1311.92  4970.8 1308.83
  4971.3 1308.33  4988.2 1308.83  5019.8 1312.25    5040  1315.6  5050.1 1318.68
  5060.2 1318.76  5080.4  1314.1  5090.5  1314.1  5100.6 1317.32  5120.8 1318.08
  5130.9 1319.67  5201.6 1324.25    5228 1325.14  5262.2 1326.82  5353.1 1329.23
#Mann= 7 ,-1 , 0
  4497.1     .12       0  4593.2    .035       0  4769.5     .07       0
  4868.3     .12       0  4970.8     .05       0  4988.2     .12       0
    5228     .07       0
Bank Sta=4970.8,4988.2
XS Rating Curve= 0 ,0
Exp/Cntr=0.3,0.1

Type RM Length L Ch R = 1 ,3665    ,447,447,447
BEGIN DESCRIPTION:
SHEPS CREEK 4.0
END DESCRIPTION:
XS GIS Cut Line= 3
       2103880.9     13898740.17        2102975.       13898375.
      2102375.01       13898475.
#Sta/Elev= 30
  4017.7 1345.82    4150 1341.76  4179.5 1339.61  4325.7 1336.64  4472.2 1333.46
    4585 1329.24  4740.7 1327.47  4757.2 1325.85  4764.8  1319.8  4770.2 1319.99
  4778.8 1315.44    4789  1314.1  4794.4  1315.2  4800.4 1313.83  4908.2 1313.95
  4955.6 1311.52  4995.8 1308.92  4996.3 1308.42  5013.3 1308.92    5035 1310.55
  5075.5 1317.33  5149.5  1317.2  5176.9 1316.56  5187.1 1317.98  5209.9 1316.84
  5227.6 1313.61  5247.9 1316.21  5392.3 1320.02  5433.2 1322.55  5602.7 1329.09
#Mann= 7 ,-1 , 0
  4017.7     .07       0  4325.7     .12       0  4955.6     .07       0
  4995.8     .05       0  5013.3     .07       0  5149.5     .12       0
  5433.2     .07       0
Bank Sta=4995.8,5013.3
XS Rating Curve= 0 ,0
Exp/Cntr=0.3,0.1

Type RM Length L Ch R = 1 ,3218    ,484,484,484
BEGIN DESCRIPTION:
SHEPS CREEK 3.0
END DESCRIPTION:
XS GIS Cut Line= 3
      2104360.03     13898141.21        2103025.       13897975.
      2102425.04     13898374.97
#Sta/Elev= 30
  3650.4 1349.51    3655 1348.72  3695.8 1345.24  3835.1 1341.36  3902.7 1338.13
  4149.7  1333.8  4209.7 1331.94  4424.8 1329.26  4562.4 1326.38  4669.2 1320.62
  4693.4 1319.28  4715.5  1315.9  4739.4 1315.16  4850.1 1314.16    4895 1314.58
  4957.9 1312.82  4984.2  1304.6  4984.7  1304.1  5002.2  1304.6  5031.8 1304.74
  5060.3 1310.62  5096.4 1312.25  5111.4 1314.77  5234.5 1313.48  5333.8 1313.86
  5428.4 1316.64  5450.9 1312.72    5472 1316.27  5588.2 1320.43  5716.8 1326.59
#Mann= 12 ,-1 , 0
  3650.4     .12       0    3655     .07       0  3835.1     .12       0
  4149.7     .07       0  4424.8     .12       0  4669.2     .07       0
  4739.4     .12       0  4850.1     .07       0  4984.2     .05       0
  5002.2     .07       0  5234.5     .12       0  5588.2     .07       0
Bank Sta=4984.2,5002.2
XS Rating Curve= 0 ,0
Exp/Cntr=0.3,0.1

Type RM Length L Ch R = 1 ,2734    ,485,485,485
BEGIN DESCRIPTION:
SHEPS CREEK 2.0
END DESCRIPTION:
XS GIS Cut Line= 3
      2103474.97     13897924.98        2102875.       13897575.
      2102418.67     13897303.45
#Sta/Elev= 30
  4305.4 1324.45  4340.5 1322.59  4363.2 1318.16  4386.4 1316.23  4481.3 1313.42
  4618.4 1311.65  4692.8 1313.24  4865.8 1310.52  4918.9 1308.31  4975.7  1308.9
  4977.9 1308.81  5002.9 1307.32  5007.8 1301.08  5013.6 1301.88  5014.3 1300.13
  5014.8 1299.63  5032.3 1300.13    5035 1302.87  5058.2 1305.16  5087.6  1312.4
  5197.8 1311.87  5220.1 1310.64  5232.7  1306.4  5247.3 1307.68  5284.3 1314.91
  5299.9 1322.46  5315.7 1325.68  5381.7 1327.24  5428.3 1327.74    5531 1328.01
#Mann= 10 ,-1 , 0
  4305.4     .12       0  4481.3    .035       0  4865.8     .12       0
  4975.7    .035       0  4977.9     .12       0  5014.3     .05       0
  5032.3     .12       0  5315.7     .07       0  5381.7     .12       0
  5428.3     .07       0
Bank Sta=5014.3,5032.3
XS Rating Curve= 0 ,0
Exp/Cntr=0.3,0.1

Type RM Length L Ch R = 1 ,2249    ,1478,1478,1478
BEGIN DESCRIPTION:
SHEPS CREEK 1.0
END DESCRIPTION:
XS GIS Cut Line= 3
      2103574.99     13897524.99        2102975.       13897125.
      2102675.04     13897075.01
#Sta/Elev= 30
  4278.9 1325.25  4286.4 1323.16  4358.5 1311.71  4382.1 1310.29  4493.6 1308.22
  4498.2 1308.31  4614.3 1308.04  4654.4 1308.16  4734.1 1310.07  4895.3 1308.59
  4977.5 1305.43  4986.5 1303.48    4988 1299.35  4988.5 1298.85    5006 1299.35
  5027.9 1303.84  5040.5 1309.56  5050.7 1311.78  5093.8  1311.5  5101.4 1308.27
  5111.5 1306.03  5131.8 1306.32  5141.9 1307.03  5154.6 1310.94  5172.3 1311.45
  5215.4  1318.5  5243.3 1319.52  5263.6 1321.47  5271.2 1323.56  5304.1 1325.46
#Mann= 9 ,-1 , 0
  4278.9     .12       0  4382.1    .035       0  4493.6     .07       0
  4498.2    .035       0  4614.3     .07       0  4654.4    .035       0
  4895.3     .12       0    4988     .05       0    5006     .12       0
Bank Sta=4988,5006
XS Rating Curve= 0 ,0
Exp/Cntr=0.3,0.1

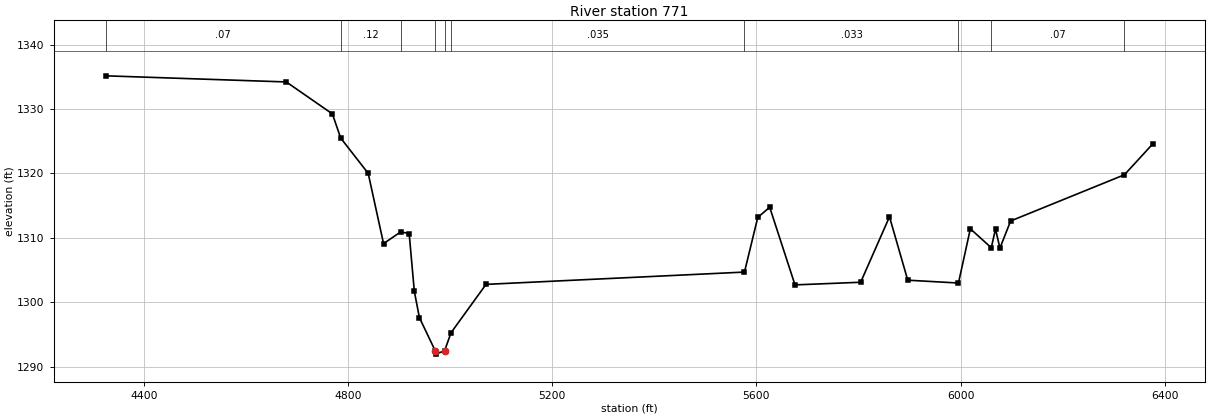
Type RM Length L Ch R = 1 ,771     ,0,0,0
BEGIN DESCRIPTION:
Sheps Creek 0.0
END DESCRIPTION:
XS GIS Cut Line= 3
      2104397.31     13896323.97      2103509.62     13896248.96
      2102563.24     13896922.43
#Sta/Elev= 30
    4325 1335.16  4678.6 1334.21  4768.9 1329.25  4785.2  1325.5  4839.1 1320.02
  4869.2 1309.11  4902.8 1310.93  4919.4 1310.67  4929.5  1301.7  4939.5 1297.61
  4970.6 1292.45  4971.1 1291.95  4988.7 1292.45  5001.5 1295.28    5070 1302.78
  5576.6 1304.69  5602.6 1313.17    5626 1314.76  5675.6  1302.7  5804.3 1303.11
  5860.8 1313.27  5896.6 1303.43    5996 1302.99  6019.3 1311.41  6060.3 1308.47
  6068.6 1311.36  6077.3 1308.41  6098.2 1312.62  6321.3  1319.8  6377.4 1324.64
#Mann= 10 ,-1 , 0
    4325     .07       0  4785.2     .12       0  4902.8     .07       0
  4970.6     .05       0  4988.7     .07       0  5001.5    .035       0
  5576.6    .033       0    5996     .12       0  6060.3     .07       0
  6321.3     .12       0
Bank Sta=4970.6,4988.7
XS Rating Curve= 0 ,0
Exp/Cntr=0.3,0.1

Chan Stop Cuts=-1
Use User Specified Reach Order=0
Composite Channel Slope=5