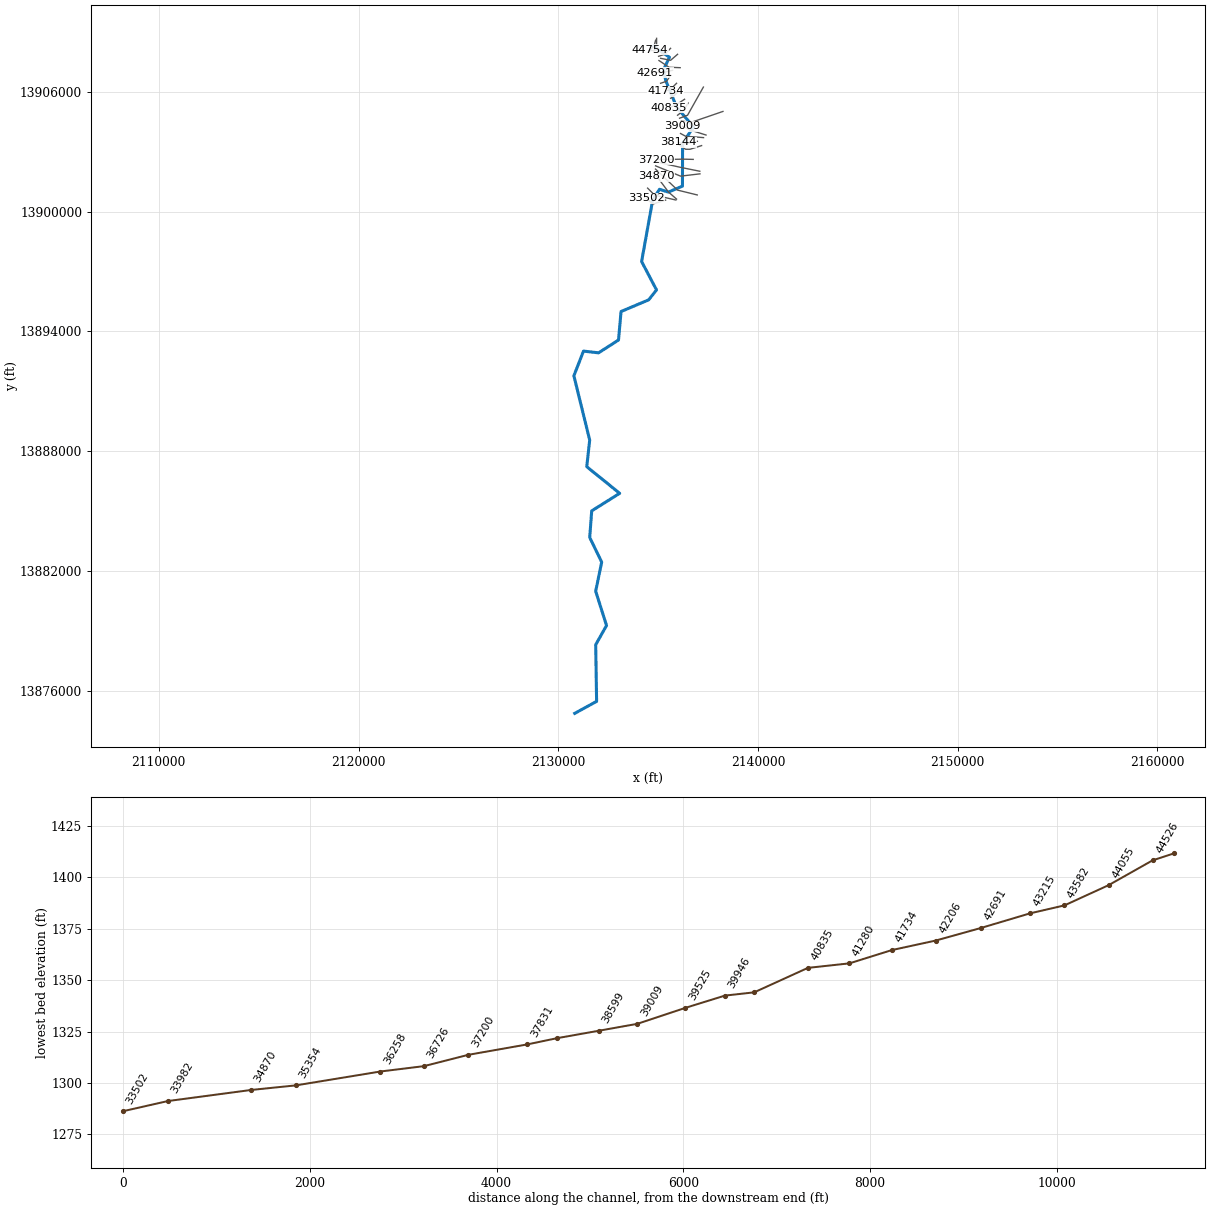
--- SIMMONS CREEK.prj (project) ---

Proj Title=SIMMONS CREEK Base Level Engineering
Current Plan=p01
Default Exp/Contr=0.3,0.1
English Units
Geom File=g01
Flow File=f01
Plan File=p01
Y Axis Title=Elevation
X Axis Title(PF)=Main Channel Distance
X Axis Title(XS)=Station
BEGIN DESCRIPTION:
SIMMONS CREEK
END DESCRIPTION:
DSS Export Rating Curves= 0
DSS Export Rating Curve Sorted= 0
DSS Export Volume Flow Curves= 0
DXF OffsetX= 0
DXF OffsetY= 0
DXF ScaleX= 1
DXF ScaleY= 10

--- SIMMONS CREEK.p01 (plan) ---

Plan Title=Multiple Run
Short Identifier=Multiple
Geom File=g01
Flow File=f01
Subcritical Flow
K Sum by GR= 0
Std Step Tol= 0.01
Critical Tol= 0.01
Num of Std Step Trials= 20
Max Error Tol= 0.3
Flow Tol Ratio= 0.001
Split Flow NTrial= 30
Split Flow Tol= 0.02
Split Flow Ratio= 0.02
Log Output Level= 0
Friction Slope Method= 1
Unsteady Friction Slope Method= 2
Unsteady Bridges Friction Slope Method= 1
Parabolic Critical Depth
Global Vel Dist=  1 , 1 , 1
Global Log Level= 0
CheckData=True
Encroach Param= -1, 0, 0, 0
BEGIN DESCRIPTION:
Multiple Run
END DESCRIPTION:

--- SIMMONS CREEK.f01 (steady flow) ---

Flow Title=Multiple
Program Version=4.10
Number of Profiles= 7
Profile Names=10-year,25-year,50-year,1pct_min,100-year,1pct_plu,500-year
River Rch & RM=SIMMONS CREEK,Reach-1         ,44754
     569     932    1268     840    1675    3343    2884
River Rch & RM=SIMMONS CREEK,Reach-1         ,44055
    1454    2522    3564    2442    4872    9721    9004
River Rch & RM=SIMMONS CREEK,Reach-1         ,40261
    2073    3654    5217    3605    7193   14351   13529
River Rch & RM=SIMMONS CREEK,Reach-1         ,37200
    3039    5458    7890    5512   10998   21944   21160
River Rch & RM=SIMMONS CREEK,Reach-1         ,33982
    3988    7222   10499    7367   14699   29328   28534
River Rch & RM=SIMMONS CREEK,Reach-1         ,28448
    4758    8656   12619    8873   17704   35324   34515
River Rch & RM=SIMMONS CREEK,Reach-1         ,22987
    8468   15741   23287   16593   33106   66056   66262
River Rch & RM=SIMMONS CREEK,Reach-1         ,15276
    8345   15549   23036   16436   32793   65432   65840
River Rch & RM=SIMMONS CREEK,Reach-1         ,12041
    8786   16376   24264   17311   34540   68916   69334
River Rch & RM=SIMMONS CREEK,Reach-1         ,6006
    9416   17560   26028   18571   37054   73933   74394
River Rch & RM=SIMMONS CREEK,Reach-1         ,1187
    9441   17599   26079   18603   37117   74058   74475
Boundary for River Rch & Prof#=SIMMONS CREEK,Reach-1         , 1
Up Type= 0
Dn Type= 3
Dn Slope=0.007
Boundary for River Rch & Prof#=SIMMONS CREEK,Reach-1         , 2
Up Type= 0
Dn Type= 3
Dn Slope=0.007
Boundary for River Rch & Prof#=SIMMONS CREEK,Reach-1         , 3
Up Type= 0
Dn Type= 3
Dn Slope=0.007
Boundary for River Rch & Prof#=SIMMONS CREEK,Reach-1         , 4
Up Type= 0
Dn Type= 3
Dn Slope=0.007
Boundary for River Rch & Prof#=SIMMONS CREEK,Reach-1         , 5
Up Type= 0
Dn Type= 3
Dn Slope=0.007
Boundary for River Rch & Prof#=SIMMONS CREEK,Reach-1         , 6
Up Type= 0
Dn Type= 3
Dn Slope=0.007
Boundary for River Rch & Prof#=SIMMONS CREEK,Reach-1         , 7
Up Type= 0
Dn Type= 3
Dn Slope=0.007
DSS Import GetInterval= 0
DSS Import GetPeak= 0
DSS Import FillOption= 0

--- SIMMONS CREEK.g01 (geometry) ---

Geom Title=Existing Conditions
Program Version=4.10

River Reach=SIMMONS CREEK   ,Reach-1
Reach XY= 30
        2134775.       13908275.      2135569.48     13907727.43
      2135276.02     13907115.54      2135378.54     13906576.46
      2135930.83      13905222.7      2136775.06     13904240.33
      2136226.26     13903415.29      2136219.54     13901272.55
       2135510.9     13900975.24      2135068.24     13901116.59
       2134726.2      13900564.5      2134174.77     13897499.93
       2134921.4     13896076.49      2134527.29     13895580.85
      2133144.78     13894995.09      2133017.14     13893568.83
      2132019.48     13892927.35      2131265.18      13893014.5
      2130783.04     13891778.32      2131574.75     13888559.78
      2131428.52     13887226.28      2133075.67     13885893.46
      2131676.05     13885014.57      2131575.91     13883684.84
      2132175.33     13882450.04      2131875.38     13880990.16
      2132418.12     13879274.78      2131875.53     13878311.05
      2131921.25     13875476.55        2130825.       13874875.

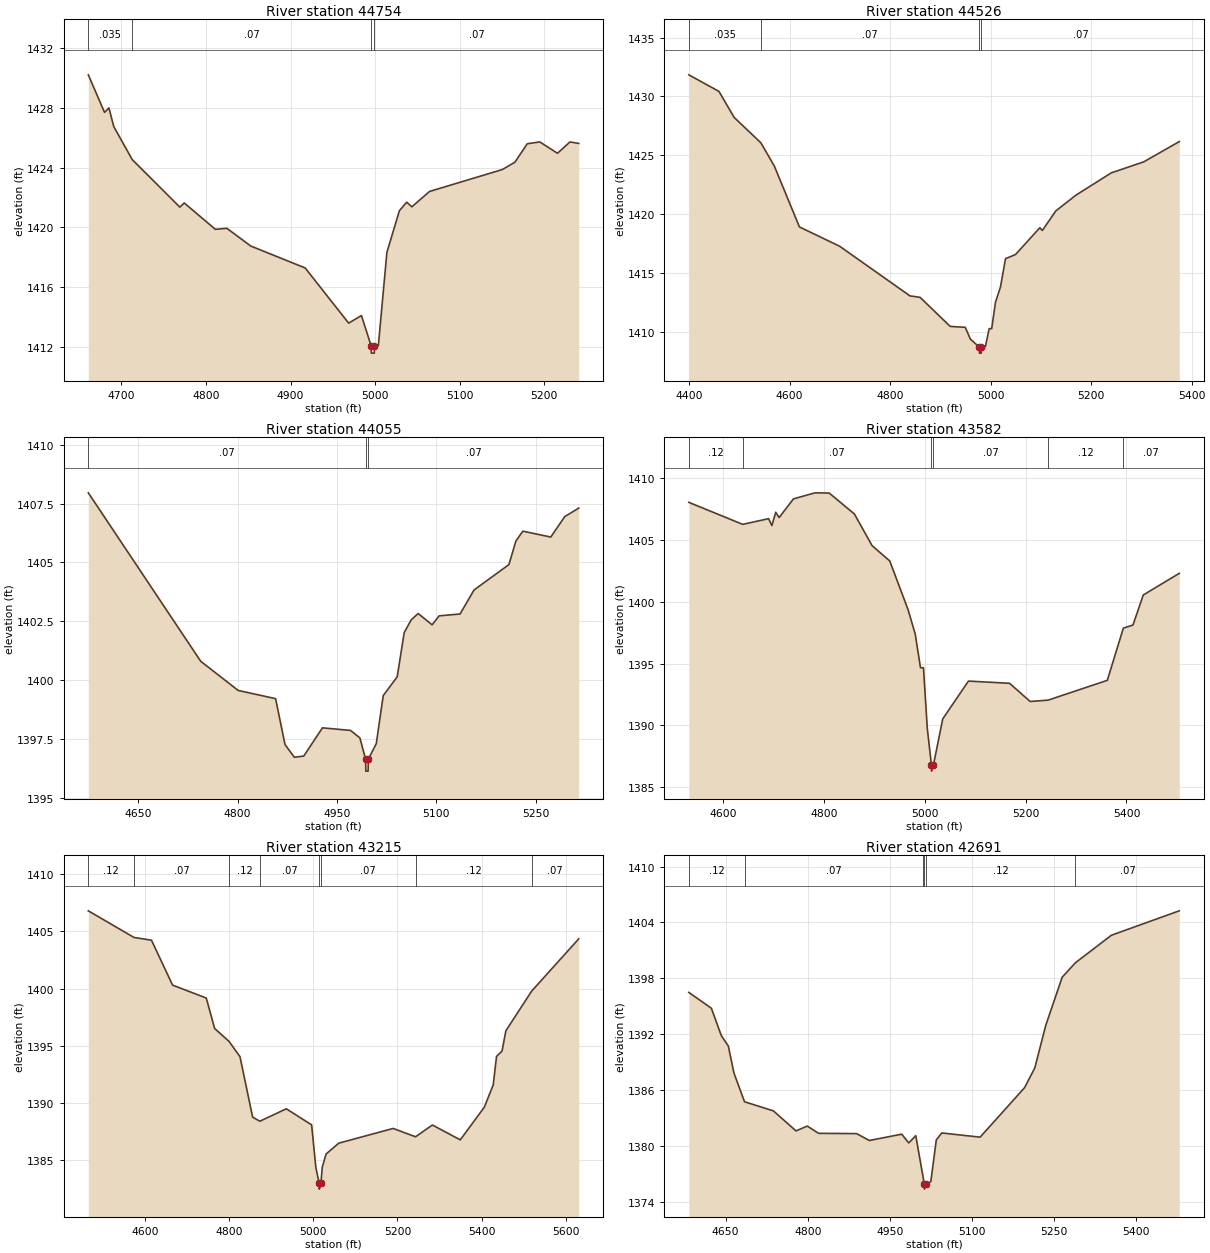
Type RM Length L Ch R = 1 ,44754   ,228,228,228
BEGIN DESCRIPTION:
SIMMONS CREEK 84.0
END DESCRIPTION:
XS GIS Cut Line= 3
      2134875.55      13908584.3      2134796.22     13908254.61
      2134600.13     13908115.02
#Sta/Elev= 30
  4660.9 1430.23  4680.1 1427.71  4685.3 1428.01    4691 1426.76  4712.8 1424.55
  4769.1 1421.36  4774.3 1421.64  4811.1 1419.87  4824.7 1419.94    4853 1418.75
  4917.3 1417.28  4968.7 1413.58  4983.8 1414.09  4995.2 1412.07  4995.5 1411.57
    4999 1411.57  4999.2 1412.07  5003.8 1412.07  5013.9 1418.33  5028.7 1421.12
  5037.3 1421.69  5043.4 1421.38  5064.3 1422.41  5150.4 1423.88  5165.2 1424.37
  5179.9 1425.61  5194.7 1425.73  5215.6 1424.97  5230.3 1425.73  5240.7 1425.63
#Mann= 4 ,-1 , 0
  4660.9    .035       0  4712.8     .07       0  4995.2     .05       0
  4999.2     .07       0
Bank Sta=4995.2,4999.2
XS Rating Curve= 0 ,0
Exp/Cntr=0.3,0.1

Type RM Length L Ch R = 1 ,44526   ,471,471,471
BEGIN DESCRIPTION:
SIMMONS CREEK 83.0
END DESCRIPTION:
XS GIS Cut Line= 3
        2134925.     13908674.96        2134925.       13908075.
      2134549.72     13908056.51
#Sta/Elev= 30
  4399.7 1431.83  4459.7 1430.42  4489.7 1428.22  4543.1 1426.05  4569.7 1424.09
  4619.7 1418.91  4699.7 1417.27  4839.7 1413.05  4859.7 1412.93  4919.7 1410.46
  4949.7 1410.38  4959.7 1409.39  4977.7 1408.69  4977.9 1408.19  4981.4 1408.19
  4981.7 1408.69  4989.7 1408.74  4997.2 1410.27  5002.2 1410.27  5009.7  1412.5
  5019.7 1413.81  5029.7 1416.21  5049.7 1416.57    5098 1418.84    5103 1418.61
  5129.8 1420.27  5169.9 1421.61    5240  1423.5  5304.8 1424.44  5375.4 1426.16
#Mann= 4 ,-1 , 0
  4399.7    .035       0  4543.1     .07       0  4977.7     .05       0
  4981.7     .07       0
Bank Sta=4977.7,4981.7
XS Rating Curve= 0 ,0
Exp/Cntr=0.3,0.1

Type RM Length L Ch R = 1 ,44055   ,473,473,473
BEGIN DESCRIPTION:
SIMMONS CREEK 82.0
END DESCRIPTION:
XS GIS Cut Line= 3
      2135624.99     13908174.99        2135325.       13907875.
      2135024.98     13907774.99
#Sta/Elev= 30
  4574.7 1407.96  4744.4  1400.8    4801 1399.56  4857.5 1399.21  4871.7 1397.26
  4885.8 1396.72    4900 1396.77  4928.2 1397.97  4970.7 1397.86  4984.8 1397.54
  4993.4 1396.63  4993.7 1396.13  4997.2 1396.13  4997.4 1396.63  5009.5  1397.3
    5020 1399.34  5041.1 1400.14  5051.7 1402.02  5062.2 1402.56  5072.7 1402.83
  5093.8 1402.35  5104.4 1402.73    5136 1402.81  5157.1 1403.83  5209.8 1404.91
  5220.3 1405.91  5230.8 1406.33    5273 1406.08  5294.1 1406.95  5315.2 1407.31
#Mann= 3 ,-1 , 0
  4574.7     .07       0  4993.4     .05       0  4997.4     .07       0
Bank Sta=4993.4,4997.4
XS Rating Curve= 0 ,0
Exp/Cntr=0.3,0.1

Type RM Length L Ch R = 1 ,43582   ,367,367,367
BEGIN DESCRIPTION:
SIMMONS CREEK 81.0
END DESCRIPTION:
XS GIS Cut Line= 3
      2135976.48     13907875.95        2135625.       13907575.
      2135125.02       13907675.
#Sta/Elev= 30
  4532.1 1408.03    4639 1406.25  4690.2 1406.71  4696.8 1406.16  4704.5 1407.23
  4711.1  1406.8  4739.6 1408.31  4782.4  1408.8  4810.5 1408.78  4860.4 1407.09
  4895.5 1404.53  4930.6 1403.29  4966.8 1399.36  4981.1 1397.38  4991.5 1394.66
  4997.4 1394.66    5005 1389.75  5013.2  1386.8  5013.5  1386.3  5017.2  1386.8
  5035.6 1390.52  5086.6 1393.58  5168.2  1393.4    5209 1391.93  5244.6 1392.04
    5362 1393.64  5393.8 1397.86  5412.9 1398.11  5433.3 1400.54  5504.7 1402.29
#Mann= 6 ,-1 , 0
  4532.1     .12       0    4639     .07       0  5013.2     .05       0
  5017.2     .07       0  5244.6     .12       0  5393.8     .07       0
Bank Sta=5013.2,5017.2
XS Rating Curve= 0 ,0
Exp/Cntr=0.3,0.1

Type RM Length L Ch R = 1 ,43215   ,524,524,524
BEGIN DESCRIPTION:
SIMMONS CREEK 80.0
END DESCRIPTION:
XS GIS Cut Line= 3
      2136104.91      13907205.8      2135549.38     13907226.63
      2135042.39     13907563.47
#Sta/Elev= 30
    4466  1406.8  4574.5 1404.47    4616 1404.23  4666.1  1400.3  4746.1 1399.17
  4766.1  1396.5  4800.1 1395.38  4826.2 1394.04  4856.2 1388.75  4873.4 1388.39
  4936.2 1389.48  4996.3 1388.07  5006.3 1384.35  5014.3 1382.95  5014.5 1382.45
  5018.3 1382.95  5021.6 1384.38  5030.6 1385.52  5060.7 1386.47  5189.9 1387.76
  5243.1 1387.03  5283.1 1388.06  5349.3 1386.76  5406.4 1389.62  5427.5 1391.57
  5435.4 1394.06  5448.5 1394.53  5457.5  1396.3  5518.9 1399.78  5630.6 1404.35
#Mann= 8 ,-1 , 0
    4466     .12       0  4574.5     .07       0  4800.1     .12       0
  4873.4     .07       0  5014.3     .05       0  5018.3     .07       0
  5243.1     .12       0  5518.9     .07       0
Bank Sta=5014.3,5018.3
XS Rating Curve= 0 ,0
Exp/Cntr=0.3,0.1

Type RM Length L Ch R = 1 ,42691   ,485,485,485
BEGIN DESCRIPTION:
SIMMONS CREEK 79.0
END DESCRIPTION:
XS GIS Cut Line= 3
        2135725.       13907075.        2135325.       13906975.
      2134841.07     13906962.75
#Sta/Elev= 30
  4582.7 1396.49  4623.9 1394.79    4642 1391.86  4654.9 1390.73  4665.2 1387.82
  4684.5 1384.75  4737.3 1383.77  4778.6 1381.62  4799.2 1382.14  4819.8 1381.36
  4889.4 1381.33  4912.6 1380.59  4971.8 1381.27  4984.7 1380.33  4997.5 1381.11
  5011.3 1376.52    5013 1375.87  5013.3 1375.37    5017 1375.87    5025 1376.19
    5035 1380.65    5045  1381.4  5115.1 1380.95  5196.3 1386.26  5215.1 1388.39
  5235.1 1392.96  5265.1 1398.12  5289.2 1399.67  5355.1 1402.63  5479.1 1405.25
#Mann= 6 ,-1 , 0
  4582.7     .12       0  4684.5     .07       0  5011.3     .12       0
    5013     .05       0    5017     .12       0  5289.2     .07       0
Bank Sta=5013,5017
XS Rating Curve= 0 ,0
Exp/Cntr=0.3,0.1

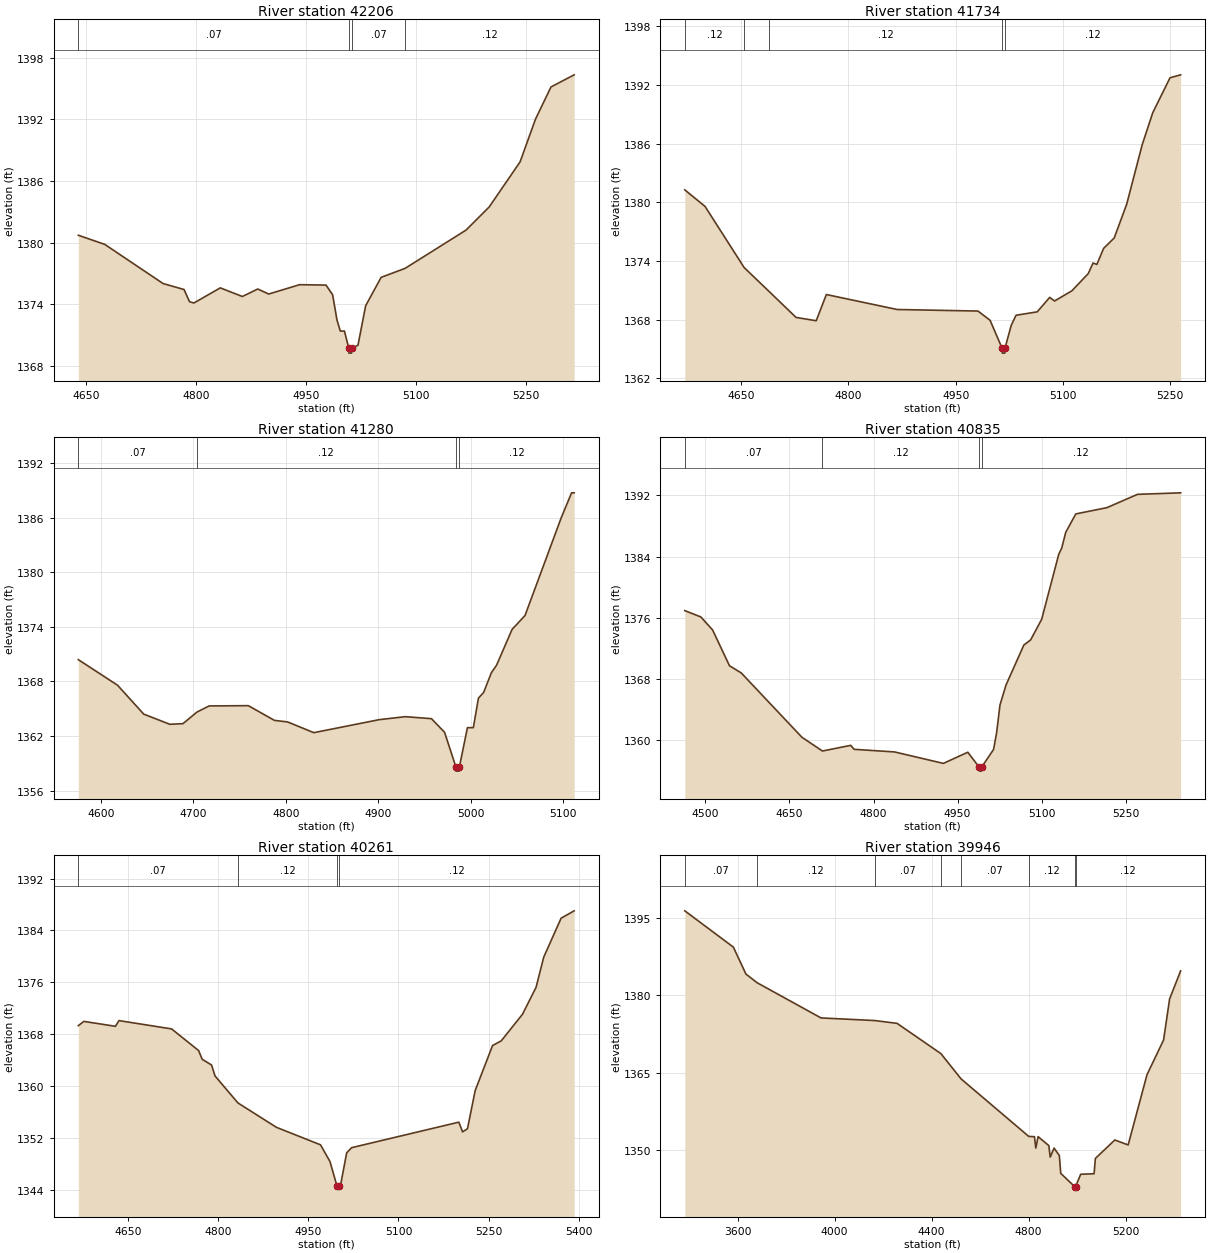
Type RM Length L Ch R = 1 ,42206   ,472,472,472
BEGIN DESCRIPTION:
SIMMONS CREEK 78.0
END DESCRIPTION:
XS GIS Cut Line= 3
      2135625.02     13906825.03        2135425.       13906525.
      2135125.02     13906425.01
#Sta/Elev= 30
  4639.1 1380.71  4675.2 1379.82  4754.8 1376.01  4783.4 1375.43  4790.9 1374.24
  4796.9 1374.12  4832.9 1375.59    4863 1374.75    4884 1375.48    4899 1374.99
  4941.1  1375.9  4977.2 1375.86  4986.2 1374.92  4992.2 1372.45  4996.7 1371.39
  5002.3 1371.39  5008.2 1369.74  5008.5 1369.24    5012 1369.24  5012.2 1369.74
  5020.8    1370  5031.3 1373.85  5052.4 1376.61  5085.2 1377.49  5168.3 1381.21
    5200 1383.47  5242.1 1387.85  5263.2 1392.02  5284.3 1395.14  5315.9 1396.32
#Mann= 4 ,-1 , 0
  4639.1     .07       0  5008.2     .05       0  5012.2     .07       0
  5085.2     .12       0
Bank Sta=5008.2,5012.2
XS Rating Curve= 0 ,0
Exp/Cntr=0.3,0.1

Type RM Length L Ch R = 1 ,41734   ,454,454,454
BEGIN DESCRIPTION:
SIMMONS CREEK 77.0
END DESCRIPTION:
XS GIS Cut Line= 3
        2135925.       13906425.        2135625.       13906125.
      2135375.02     13906025.01
#Sta/Elev= 30
  4571.2 1381.28  4599.5 1379.59  4654.2 1373.34  4689.3 1370.88  4726.8 1368.24
    4755  1367.9  4769.2 1370.58  4868.2 1369.05  4981.3 1368.89  4998.2 1367.95
    5015 1365.09  5015.3 1364.59  5018.8 1364.59    5019 1365.09  5027.8 1367.44
  5034.5 1368.46  5064.1 1368.81  5081.6 1370.29  5088.4 1369.92  5112.6 1370.96
  5135.5 1372.72  5142.2  1373.8  5147.6 1373.66    5157  1375.3  5171.8 1376.36
  5189.3 1379.82  5210.9 1385.88  5225.7 1389.16  5249.9 1392.74  5264.7 1393.04
#Mann= 5 ,-1 , 0
  4571.2     .12       0  4654.2     .07       0  4689.3     .12       0
    5015     .05       0    5019     .12       0
Bank Sta=5015,5019
XS Rating Curve= 0 ,0
Exp/Cntr=0.3,0.1

Type RM Length L Ch R = 1 ,41280   ,445,445,445
BEGIN DESCRIPTION:
SIMMONS CREEK 76.0
END DESCRIPTION:
XS GIS Cut Line= 3
      2136024.99     13906024.99        2135725.       13905725.
      2135624.96     13905674.98
#Sta/Elev= 30
  4575.7  1370.4  4618.1 1367.59  4646.4 1364.41  4674.7 1363.29  4688.8 1363.36
  4703.9 1364.63  4717.1 1365.31  4759.5 1365.34  4787.8 1363.72    4802 1363.55
  4830.3 1362.37    4901  1363.8  4929.2 1364.13  4957.5 1363.91  4971.7 1362.41
  4983.8 1358.64  4984.1 1358.14  4987.6 1358.14  4987.8 1358.64  4996.4 1362.92
  5002.8 1362.92  5008.3 1366.17  5013.9 1366.79  5022.3 1368.96  5027.9 1369.79
  5044.7 1373.73  5058.7 1375.26  5097.8    1386    5109 1388.75  5111.8 1388.75
#Mann= 4 ,-1 , 0
  4575.7     .07       0  4703.9     .12       0  4983.8     .05       0
  4987.8     .12       0
Bank Sta=4983.8,4987.8
XS Rating Curve= 0 ,0
Exp/Cntr=0.3,0.1

Type RM Length L Ch R = 1 ,40835   ,574,574,574
BEGIN DESCRIPTION:
SIMMONS CREEK 75.0
END DESCRIPTION:
XS GIS Cut Line= 3
      2136325.03     13905625.02        2135875.       13905325.
      2135552.82     13905205.79
#Sta/Elev= 30
  4463.4 1376.93    4492  1376.1    4513  1374.4  4543.1 1369.72  4564.1 1368.78
  4672.3 1360.37  4708.9 1358.57  4759.4 1359.31  4765.4 1358.79  4837.5 1358.45
  4924.6 1356.95  4968.2 1358.41  4988.7 1356.44    4989 1355.94  4992.5 1355.94
  4992.7 1356.44  5014.1 1358.77  5019.5 1360.91  5025.6 1364.59  5036.3 1367.19
  5068.2 1372.43  5080.3  1373.1    5100  1375.8  5130.4 1384.29  5135.7  1385.1
  5142.9 1387.17  5160.8 1389.57  5216.3 1390.39  5270.8 1392.13  5347.8 1392.33
#Mann= 4 ,-1 , 0
  4463.4     .07       0  4708.9     .12       0  4988.7     .05       0
  4992.7     .12       0
Bank Sta=4988.7,4992.7
XS Rating Curve= 0 ,0
Exp/Cntr=0.3,0.1

Type RM Length L Ch R = 1 ,40261   ,315,315,315
BEGIN DESCRIPTION:
SIMMONS CREEK 74.0
END DESCRIPTION:
XS GIS Cut Line= 3
      2136504.24     13905438.44      2136282.02     13905063.44
      2135975.03     13904825.02
#Sta/Elev= 30
  4567.6  1369.3  4576.7 1369.96  4629.3  1369.2  4635.2 1370.08  4722.7  1368.8
  4767.7 1365.45  4773.6 1364.11  4789.2 1363.22    4795 1361.53    4833 1357.37
  4897.1  1353.6  4970.4  1350.9  4986.1 1348.32  4997.7 1344.56  4997.9 1344.06
  5001.7 1344.56  5003.5 1344.56  5013.9 1349.67  5022.1 1350.46  5200.4  1354.4
  5206.7  1352.9  5214.8 1353.39  5227.6 1359.28  5256.5 1366.23    5271 1366.96
  5306.3 1371.06  5328.9 1375.23  5341.6 1379.88  5370.5 1385.89  5392.2 1387.03
#Mann= 4 ,-1 , 0
  4567.6     .07       0    4833     .12       0  4997.7     .05       0
  5001.7     .12       0
Bank Sta=4997.7,5001.7
XS Rating Curve= 0 ,0
Exp/Cntr=0.3,0.1

Type RM Length L Ch R = 1 ,39946   ,421,421,421
BEGIN DESCRIPTION:
SIMMONS CREEK 73.0
END DESCRIPTION:
XS GIS Cut Line= 3
      2137267.99      13906234.9        2136475.       13904825.
        2136075.       13904675.
#Sta/Elev= 30
  3382.4 1396.38  3582.7 1389.35  3634.7 1384.12    3681 1382.44  3944.1 1375.63
  4166.1 1375.12  4257.7 1374.58  4438.7 1368.71  4521.7 1363.82    4801 1352.67
  4824.4 1352.62  4830.1 1350.41  4839.4 1352.63  4883.7 1350.89  4889.4 1348.66
  4905.3 1350.41    4927 1348.97  4932.8 1345.52  4989.9 1342.96  4990.2 1342.46
  4994.1 1342.96  5015.1 1345.34  5070.3 1345.44  5075.7 1348.41  5155.8 1351.98
  5210.9 1351.02  5288.4 1364.61  5356.9 1371.35  5381.8 1379.31  5427.2 1384.74
#Mann= 8 ,-1 , 0
  3382.4     .07       0    3681     .12       0  4166.1     .07       0
  4438.7     .12       0  4521.7     .07       0    4801     .12       0
  4989.9     .05       0  4994.1     .12       0
Bank Sta=4989.9,4994.1
XS Rating Curve= 0 ,0
Exp/Cntr=0.3,0.1

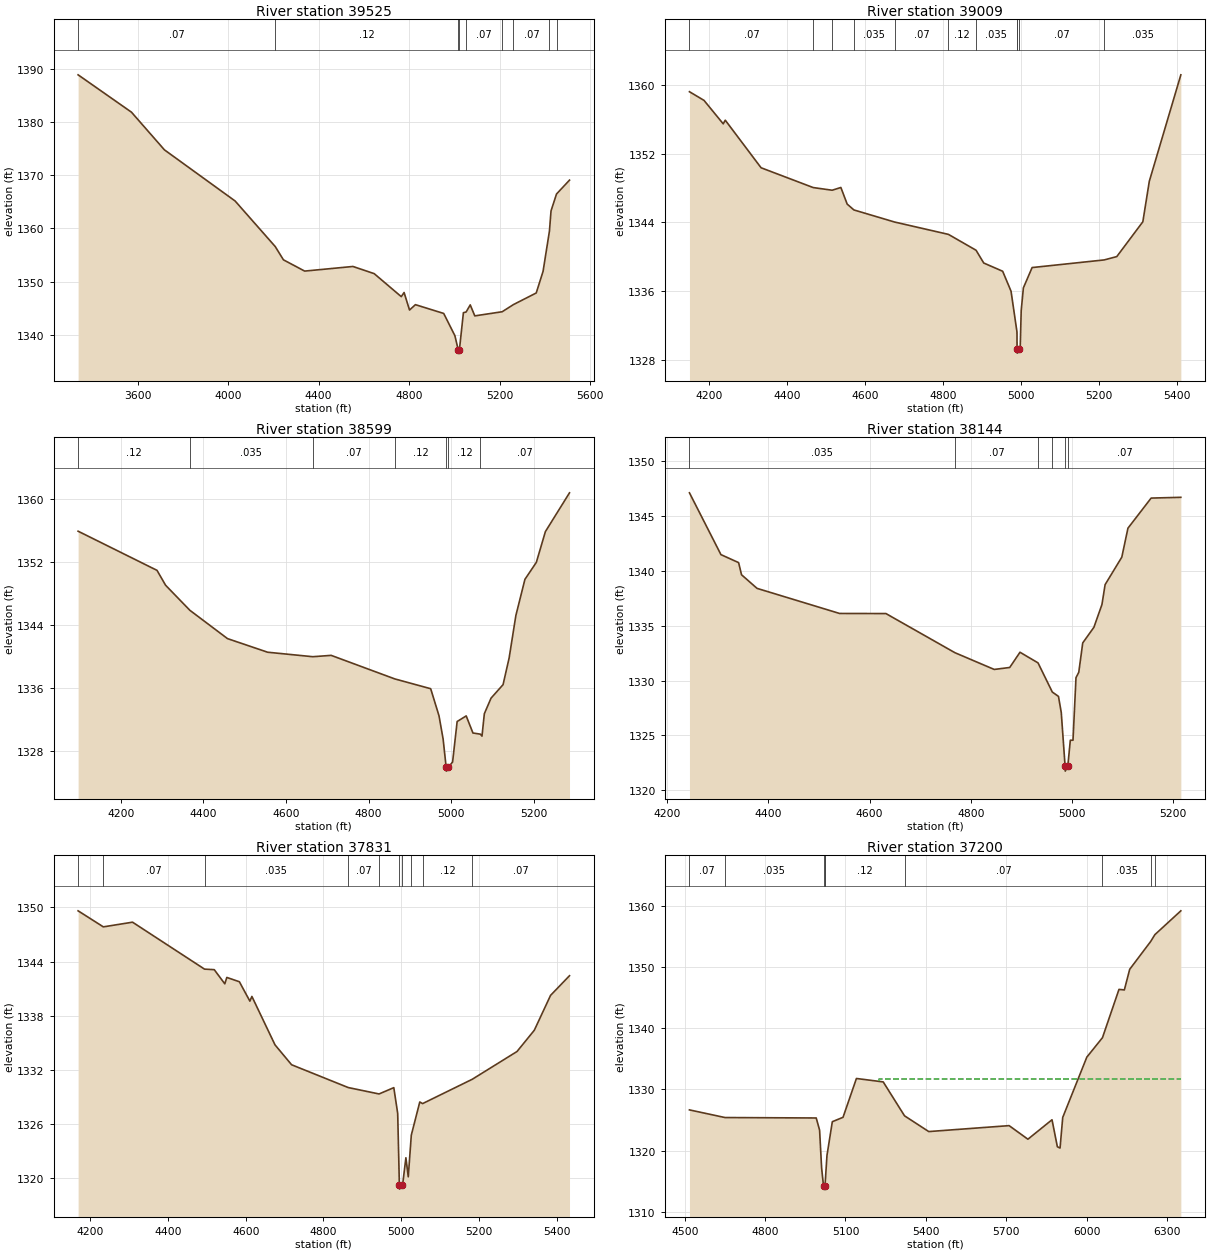
Type RM Length L Ch R = 1 ,39525   ,516,516,516
BEGIN DESCRIPTION:
SIMMONS CREEK 72.0
END DESCRIPTION:
XS GIS Cut Line= 3
      2138247.56     13905015.01        2136675.       13904475.
      2136168.73     13904528.58
#Sta/Elev= 30
  3337.3 1388.91  3573.1 1381.88  3718.8 1374.79  4031.3 1365.16  4208.5 1356.59
  4244.8 1354.09  4338.6 1351.97  4552.1 1352.84  4645.9 1351.49  4765.6 1347.16
    4778 1347.94  4802.1 1344.64  4828.1 1345.65  4953.1    1344  5002.5 1339.82
    5018 1337.03  5018.3 1336.53  5022.2 1337.03  5040.2 1344.14  5052.2 1344.27
  5070.4 1345.61  5090.5 1343.54  5211.6 1344.32  5261.5 1345.67    5362 1347.85
  5392.2 1351.91  5420.4 1359.49  5427.5 1363.31  5451.7 1366.48  5509.1 1369.09
#Mann= 9 ,-1 , 0
  3337.3     .07       0  4208.5     .12       0    5018     .05       0
  5022.2     .12       0  5052.2     .07       0  5211.6    .035       0
  5261.5     .07       0  5420.4     .12       0  5451.7     .07       0
Bank Sta=5018,5022.2
XS Rating Curve= 0 ,0
Exp/Cntr=0.3,0.1

Type RM Length L Ch R = 1 ,39009   ,410,410,410
BEGIN DESCRIPTION:
SIMMONS CREEK 71.0
END DESCRIPTION:
XS GIS Cut Line= 3
      2137400.55     13903833.32       2136594.5     13904087.74
      2136224.99     13904275.01
#Sta/Elev= 30
  4149.5 1359.24  4186.8 1358.23  4236.1 1355.49  4241.3 1355.92  4333.1 1350.37
  4466.7 1348.06  4515.3 1347.75  4537.6 1348.07  4553.8 1346.13    4571 1345.45
  4675.4 1344.04  4813.3  1342.6  4884.1 1340.75  4903.8 1339.26  4952.3  1338.3
  4973.8 1335.97  4988.5 1331.37    4989 1331.19  4989.2 1329.25  4989.6 1328.75
  4994.6 1329.25  4997.2 1329.25  4999.8  1333.7  5005.4 1336.36  5027.8 1338.73
  5212.5 1339.62  5244.8 1340.01  5311.6 1344.07  5328.2  1348.8    5409 1361.21
#Mann= 11 ,-1 , 0
  4149.5     .07       0  4466.7    .035       0  4515.3     .12       0
    4571    .035       0  4675.4     .07       0  4813.3     .12       0
  4884.1    .035       0  4988.5     .07       0  4989.2     .05       0
  4994.6     .07       0  5212.5    .035       0
Bank Sta=4989.2,4994.6
XS Rating Curve= 0 ,0
Exp/Cntr=0.3,0.1

Type RM Length L Ch R = 1 ,38599   ,455,455,455
BEGIN DESCRIPTION:
SIMMONS CREEK 70.0
END DESCRIPTION:
XS GIS Cut Line= 3
      2137275.27     13903703.62        2136375.       13903775.
      2136123.39     13903910.13
#Sta/Elev= 30
  4097.1 1355.92    4288 1350.94  4308.7 1349.05  4367.5 1345.86  4458.5 1342.26
  4555.6 1340.53  4664.8 1339.96  4709.3 1340.13    4863 1337.14    4950 1335.89
  4970.1 1332.45  4980.1 1329.48  4987.4 1325.91  4987.9 1325.41  4992.9 1325.91
    5003 1326.57    5014 1331.72  5035.9 1332.43  5052.2 1330.26  5070.3 1330.11
  5074.1 1329.86  5079.8 1332.71    5096 1334.69  5125.1 1336.41  5139.8 1339.81
  5156.1 1345.21    5178  1349.8  5205.6 1351.96  5227.5 1355.87  5285.8  1360.8
#Mann= 7 ,-1 , 0
  4097.1     .12       0  4367.5    .035       0  4664.8     .07       0
    4863     .12       0  4987.4     .05       0  4992.9     .12       0
  5070.3     .07       0
Bank Sta=4987.4,4992.9
XS Rating Curve= 0 ,0
Exp/Cntr=0.3,0.1

Type RM Length L Ch R = 1 ,38144   ,313,313,313
BEGIN DESCRIPTION:
SIMMONS CREEK 69.0
END DESCRIPTION:
XS GIS Cut Line= 3
      2136966.07     13903518.31        2136225.       13903375.
      2136029.27     13903465.88
#Sta/Elev= 30
  4244.3 1347.13  4306.5 1341.49  4341.4 1340.76  4347.2 1339.65  4377.8 1338.41
  4540.8 1336.12  4632.4 1336.11  4768.6 1332.54  4846.3 1331.01  4876.9 1331.19
  4897.2 1332.58  4932.8 1331.61    4961 1328.95  4973.2 1328.55  4978.7 1327.08
  4986.2 1322.23  4986.6 1321.73  4991.7 1322.23  4996.6 1324.55  5001.9 1324.55
  5007.8 1330.26  5013.3 1330.75  5021.1 1333.43  5043.2 1334.86  5059.1 1336.94
  5065.3 1338.75  5098.3 1341.26  5110.4  1343.9  5156.2 1346.65  5214.9 1346.72
#Mann= 6 ,-1 , 0
  4244.3    .035       0  4768.6     .07       0  4932.8     .12       0
    4961     .07       0  4986.2     .05       0  4991.7     .07       0
Bank Sta=4986.2,4991.7
XS Rating Curve= 0 ,0
Exp/Cntr=0.3,0.1

Type RM Length L Ch R = 1 ,37831   ,631,631,631
BEGIN DESCRIPTION:
SIMMONS CREEK 68.0
END DESCRIPTION:
XS GIS Cut Line= 4
      2137178.43     13903304.42      2136596.71     13903119.92
      2136375.89     13903120.39      2136021.61     13903368.99
#Sta/Elev= 30
  4168.9 1349.63  4233.8 1347.85  4308.9 1348.37  4494.1 1343.16  4519.1  1343.1
  4546.2 1341.53  4551.4 1342.24  4583.7 1341.76  4610.7 1339.61  4615.9 1340.13
  4675.3 1334.76    4718 1332.55  4863.7 1330.02    4943 1329.31  4980.9 1330.01
  4990.9 1327.15  4995.2 1319.25  4995.6 1318.75  5000.7 1319.25  5003.6 1319.25
    5012 1322.23  5018.1 1320.12  5025.9 1324.74  5047.7 1328.42    5055 1328.24
  5182.7 1330.94  5297.8 1334.02  5342.3 1336.38  5384.1 1340.25  5432.8 1342.43
#Mann= 10 ,-1 , 0
  4168.9    .035       0  4233.8     .07       0  4494.1    .035       0
  4863.7     .07       0    4943     .12       0  4995.2     .05       0
  5000.7     .12       0  5025.9     .07       0    5055     .12       0
  5182.7     .07       0
Bank Sta=4995.2,5000.7
XS Rating Curve= 0 ,0
Exp/Cntr=0.3,0.1

Type RM Length L Ch R = 1 ,37200   ,474,474,474
BEGIN DESCRIPTION:
SIMMONS CREEK 67.0
END DESCRIPTION:
XS GIS Cut Line= 3
      2136758.12     13902613.71        2136275.       13902625.
      2134924.13     13902603.09
#Sta/Elev= 30
  4517.6 1326.64  4650.3 1325.39  4990.8 1325.32  5003.4 1323.34  5010.9 1317.18
  5018.1  1314.2  5018.5  1313.7  5023.6  1314.2    5025 1315.16  5030.9 1319.18
  5050.9 1324.71  5090.9 1325.43  5140.9 1331.77  5240.9 1331.21  5320.5 1325.67
  5410.9  1323.1  5710.9 1324.07    5781 1321.85    5871 1325.03    5891 1320.62
    5901 1320.41    5911 1325.41    6001 1335.26  6059.3 1338.43    6121 1346.32
    6141 1346.23    6161  1349.6  6239.4 1354.15    6255 1355.26  6351.9 1359.15
#Mann= 9 ,-1 , 0
  4517.6     .07       0  4650.3    .035       0  5018.1    .035       0
  5023.6    .035       0    5025     .12       0  5320.5     .07       0
  6059.3    .035       0  6239.4     .12       0    6255    .035       0
#XS Ineff= 2 , 0
       0                 5226.58       0 1331.61
Permanent Ineff=
       F       F
Bank Sta=5018.1,5023.6
XS Rating Curve= 0 ,0
Exp/Cntr=0.3,0.1

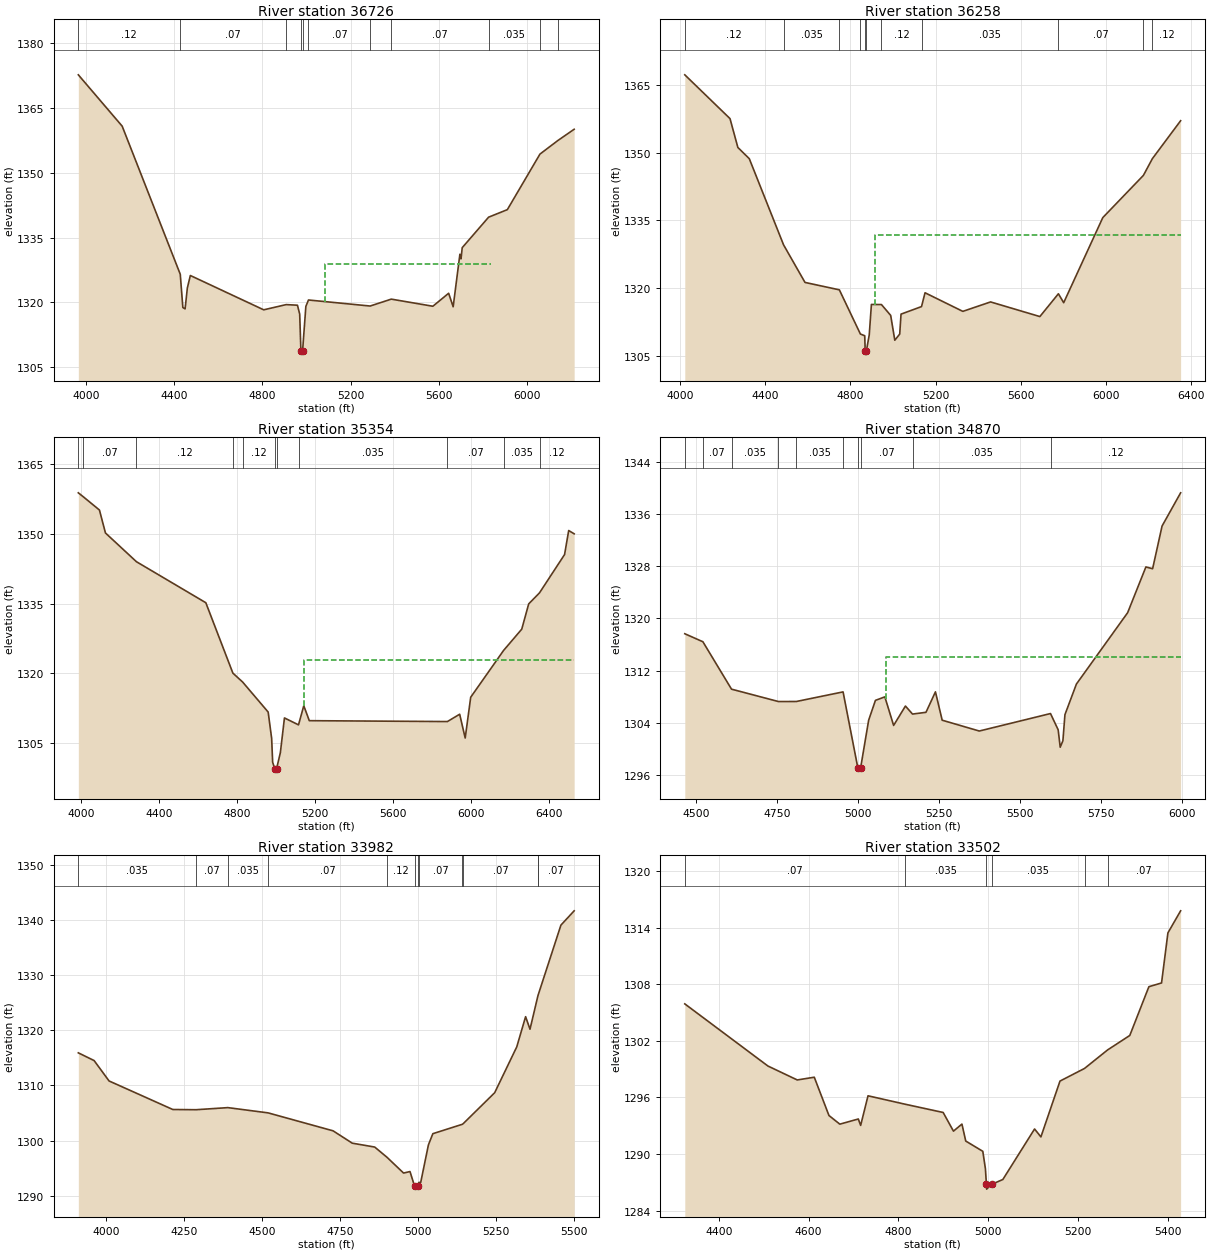
Type RM Length L Ch R = 1 ,36726   ,468,468,468
BEGIN DESCRIPTION:
SIMMONS CREEK 66.0
END DESCRIPTION:
XS GIS Cut Line= 3
      2137090.27     13902019.36        2136075.       13902225.
       2134889.1      13902493.5
#Sta/Elev= 30
  3963.7 1372.73  4162.9 1360.82  4426.6 1326.49  4438.4 1318.77  4448.6 1318.46
  4458.8 1323.29  4472.4  1326.2  4805.7 1318.24  4907.6 1319.45  4958.8 1319.31
    4969 1317.26  4974.2 1309.24  4976.6  1308.7    4977  1308.2  4982.1  1308.7
    4997 1319.03  5008.9 1320.52    5289 1319.12    5385 1320.72  5573.8 1319.07
  5645.5 1322.08    5666 1318.95  5696.6 1331.13  5701.7 1330.06  5707.1 1332.65
  5826.9 1339.72  5912.1 1341.47  6060.2 1354.35  6141.6  1357.5  6215.5 1360.11
#Mann= 11 ,-1 , 0
  3963.7     .12       0  4426.6     .07       0  4907.6     .12       0
  4976.6     .05       0  4982.1     .12       0  5008.9     .07       0
    5289    .035       0    5385     .07       0  5826.9    .035       0
  6060.2     .12       0  6141.6    .035       0
#XS Ineff= 2 ,-1
 4408.96 4473.59 1325.68 5084.43 5837.04 1328.77
Permanent Ineff=
       F       F
Bank Sta=4976.6,4982.1
XS Rating Curve= 0 ,0
Exp/Cntr=0.3,0.1

Type RM Length L Ch R = 1 ,36258   ,904,904,904
BEGIN DESCRIPTION:
SIMMONS CREEK 65.0
END DESCRIPTION:
XS GIS Cut Line= 3
      2137096.09     13901889.35        2136125.       13901775.
      2134874.34     13902290.42
#Sta/Elev= 30
  4021.5 1367.23    4234 1357.53  4270.9 1351.14  4324.7 1348.65  4485.7 1329.57
  4586.5 1321.24    4748  1319.6  4846.9 1309.81  4867.2 1309.43  4869.4 1306.08
  4869.9 1305.58    4875 1306.08  4888.5 1309.64  4898.6 1316.36  4945.8 1316.34
  4989.2 1313.94  5008.6 1308.44  5031.7  1309.8  5037.9 1314.22  5134.2 1315.89
  5150.7 1318.95  5328.3 1314.83  5458.8 1316.92  5690.4 1313.68  5777.6 1318.73
  5802.4 1316.75  5986.2  1335.6    6177 1344.95  6219.4 1348.67    6352 1357.06
#Mann= 11 ,-1 , 0
  4021.5     .12       0  4485.7    .035       0    4748     .12       0
  4846.9     .07       0  4869.4     .05       0    4875     .07       0
  4945.8     .12       0  5134.2    .035       0  5777.6     .07       0
    6177    .035       0  6219.4     .12       0
#XS Ineff= 2 , 0
       0                  4917.3       0 1331.73
Permanent Ineff=
       F       F
Bank Sta=4869.4,4875
XS Rating Curve= 0 ,0
Exp/Cntr=0.3,0.1

Type RM Length L Ch R = 1 ,35354   ,484,484,484
BEGIN DESCRIPTION:
SIMMONS CREEK 64.0
END DESCRIPTION:
XS GIS Cut Line= 3
      2136960.12     13900832.91        2135975.       13901075.
      2134869.46     13902129.01
#Sta/Elev= 30
  3985.8 1358.87  4010.1 1358.06    4094 1355.16  4124.9 1350.21  4283.5 1344.02
  4639.4 1335.17  4778.1 1319.99  4828.2 1318.06    4959 1311.59  4976.9  1305.9
    4982 1300.74  4993.4 1299.35  4993.9 1298.85    5002 1299.35  5021.5 1302.82
  5042.5 1310.32  5114.6 1308.83  5141.6 1312.95  5169.9 1309.73    5878 1309.54
  5940.8 1311.12  5969.1 1305.99  5997.4 1314.79  6165.6 1324.86  6259.1 1329.47
  6294.7 1334.92  6350.1  1337.3  6478.6 1345.56  6499.7 1350.74  6527.7 1350.03
#Mann= 11 ,-1 , 0
  3985.8     .12       0  4010.1     .07       0  4283.5     .12       0
  4778.1     .07       0  4828.2     .12       0  4993.4     .05       0
    5002     .12       0  5114.6    .035       0    5878     .07       0
  6165.6    .035       0  6350.1     .12       0
#XS Ineff= 2 , 0
       0                 5141.77       0 1322.74
Permanent Ineff=
       F       F
Bank Sta=4993.4,5002
XS Rating Curve= 0 ,0
Exp/Cntr=0.3,0.1

Type RM Length L Ch R = 1 ,34870   ,888,888,888
BEGIN DESCRIPTION:
SIMMONS CREEK 63.0
END DESCRIPTION:
XS GIS Cut Line= 3
      2135924.97     13900625.03        2135525.       13900975.
      2134924.98     13901775.03
#Sta/Elev= 30
  4464.6 1317.66  4520.5 1316.43  4608.9 1309.16  4753.9 1307.26  4809.2 1307.27
  4953.5 1308.74  4999.1 1297.09  4999.6 1296.59  5007.7 1297.09  5032.5  1304.4
  5053.4 1307.44  5082.5 1307.98  5109.6  1303.6  5146.1 1306.57    5168 1305.34
  5209.6 1305.61  5238.8 1308.75  5259.6  1304.4  5374.2 1302.74  5594.2 1305.42
  5617.9 1302.92  5624.2 1300.26  5632.5 1301.25  5638.8 1305.25  5674.2 1309.94
  5832.5 1320.89  5888.8  1327.9  5909.6 1327.63  5938.8 1334.18  5996.1 1339.27
#Mann= 10 ,-1 , 0
  4464.6    .035       0  4520.5     .07       0  4608.9    .035       0
  4753.9     .07       0  4809.2    .035       0  4953.5     .07       0
  4999.1     .05       0  5007.7     .07       0    5168    .035       0
  5594.2     .12       0
#XS Ineff= 2 , 0
       0                 5084.92       0 1314.11
Permanent Ineff=
       F       F
Bank Sta=4999.1,5007.7
XS Rating Curve= 0 ,0
Exp/Cntr=0.3,0.1

Type RM Length L Ch R = 1 ,33982   ,480,480,480
BEGIN DESCRIPTION:
SIMMONS CREEK 62.0
END DESCRIPTION:
XS GIS Cut Line= 3
      2135889.73     13900578.71        2134825.       13900825.
      2134475.02     13901174.98
#Sta/Elev= 30
  3911.4  1315.9    3962  1314.5  4009.8 1310.81  4213.9 1305.64  4288.5  1305.6
  4390.3 1305.98    4519 1305.03  4727.1 1301.78  4788.7 1299.54  4860.5 1298.84
  4899.8 1296.99  4952.9 1294.13  4973.5  1294.4  4988.4 1291.72  4988.9 1291.22
  4999.5 1291.72  5001.7 1292.43  5007.8 1292.43  5032.5 1299.23  5046.7 1301.26
    5141 1302.96  5143.8 1303.07  5244.7 1308.68  5315.4 1316.98  5343.7 1322.45
  5357.8 1320.18  5382.1 1325.98  5383.3 1326.27  5456.8 1339.03  5499.2 1341.62
#Mann= 12 ,-1 , 0
  3911.4    .035       0  4288.5     .07       0  4390.3    .035       0
    4519     .07       0  4899.8     .12       0  4988.4     .05       0
  4999.5     .12       0  5001.7     .07       0    5141    .035       0
  5143.8     .07       0  5382.1    .035       0  5383.3     .07       0
Bank Sta=4988.4,4999.5
XS Rating Curve= 0 ,0
Exp/Cntr=0.3,0.1

Type RM Length L Ch R = 1 ,33502   ,479,479,479
BEGIN DESCRIPTION:
SIMMONS CREEK 61.0
END DESCRIPTION:
XS GIS Cut Line= 3
      2135375.03     13900575.01        2134725.       13900375.
      2134424.98     13900675.02
#Sta/Elev= 30
  4324.2 1305.93  4509.3 1299.34  4574.7 1297.86  4612.6 1298.15  4645.3 1294.09
  4669.5 1293.17  4710.7 1293.72  4715.9 1293.04  4732.3 1296.18  4815.6 1295.28
  4899.7 1294.41  4922.6 1292.43  4941.5 1293.18    4950 1291.38    4988 1290.29
  4993.8 1288.44    4996 1286.78  4996.5 1286.28  5007.4 1286.78  5032.6  1287.3
  5103.3 1292.66  5117.4 1291.82  5159.9 1297.74  5214.5 1299.08  5266.1 1301.05
  5315.4 1302.58  5357.9 1307.75  5386.1 1308.15  5400.3 1313.46  5428.6  1315.8
#Mann= 6 ,-1 , 0
  4324.2     .07       0  4815.6    .035       0    4996    .035       0
  5007.4    .035       0  5214.5     .12       0  5266.1     .07       0
Bank Sta=4996,5007.4
XS Rating Curve= 0 ,0
Exp/Cntr=0.3,0.1