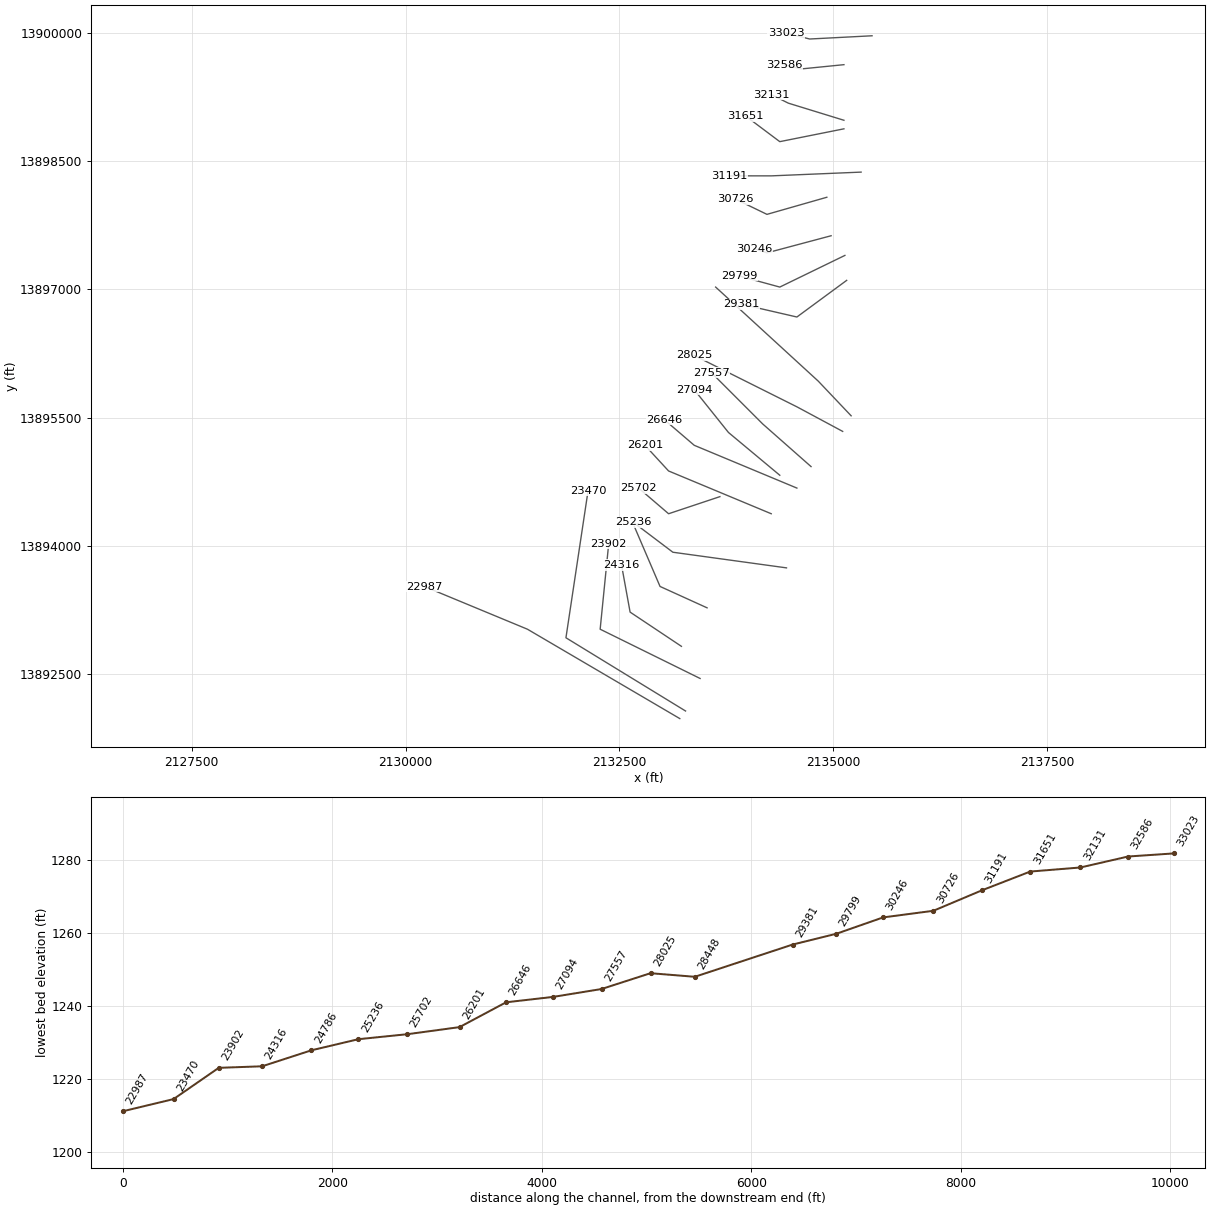
HEC-RAS study SIMMONS CREEK.prj: SIMMONS CREEK Base Level Engineering

--- SIMMONS CREEK.g01 (geometry) --- (continued)

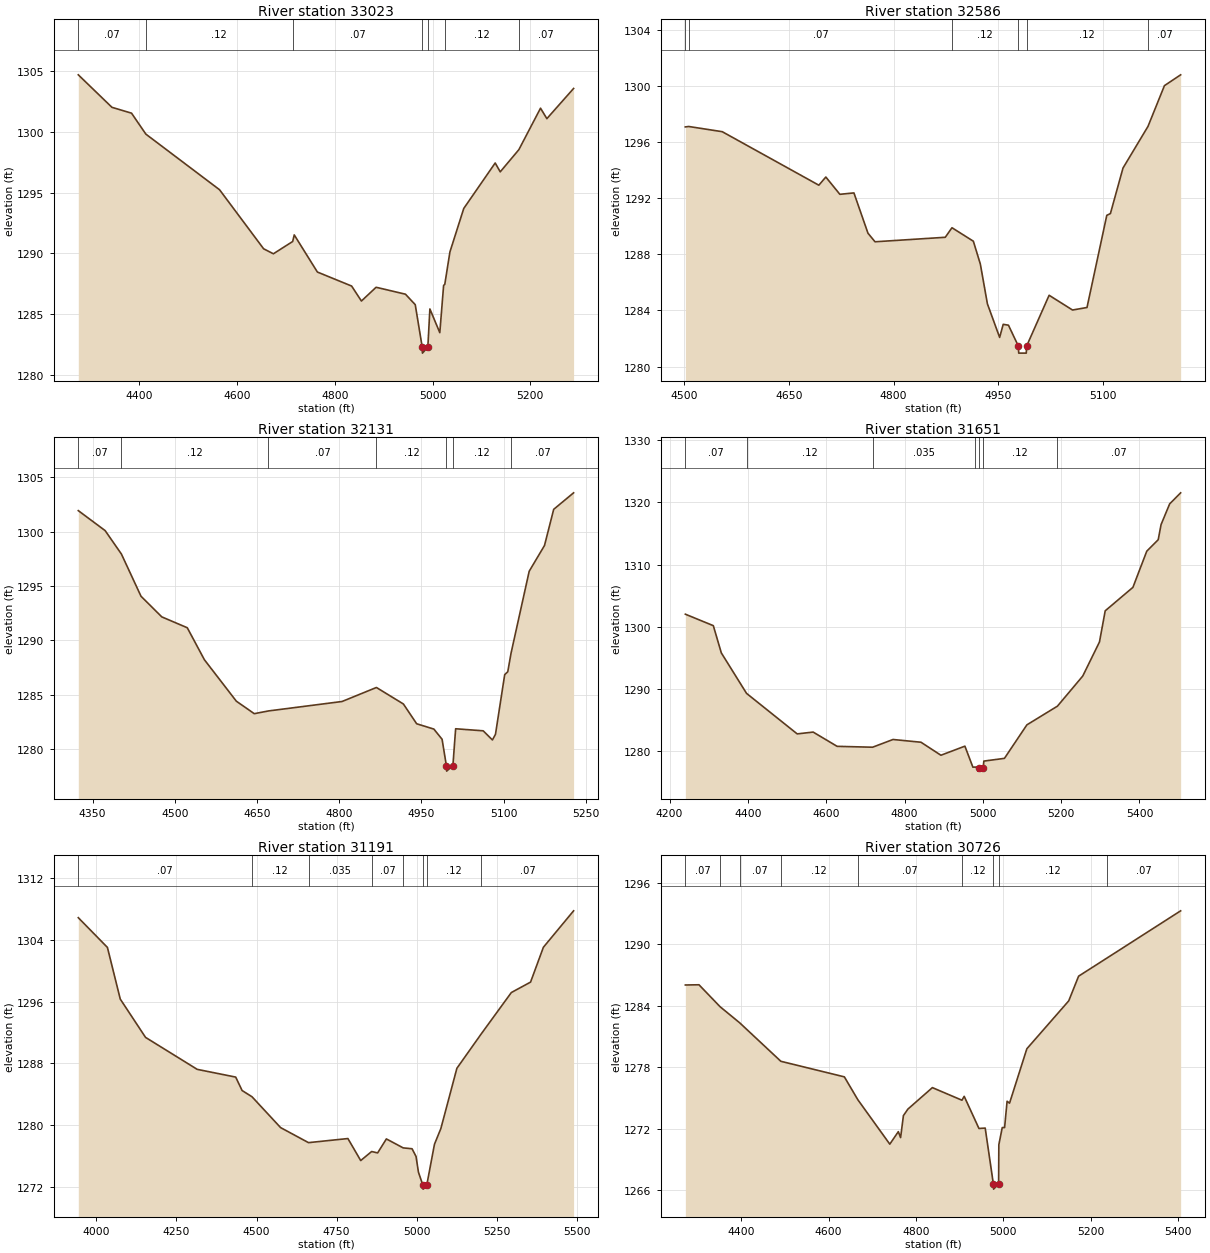
Type RM Length L Ch R = 1 ,33023   ,437,437,437
BEGIN DESCRIPTION:
SIMMONS CREEK 60.0
END DESCRIPTION:
XS GIS Cut Line= 3
      2135453.86     13899962.74        2134725.       13899925.
       2134449.3     13899993.84
#Sta/Elev= 30
  4274.8 1304.67  4343.7    1302  4383.8 1301.52  4413.1  1299.8    4564 1295.23
  4654.2 1290.38  4674.2 1289.97  4713.7 1290.98  4716.9 1291.52  4764.3 1288.47
  4834.4 1287.32  4854.4 1286.09  4884.5 1287.22  4944.6 1286.65  4964.6 1285.79
  4978.9 1282.31  4979.4 1281.81  4990.4 1282.31  4994.6 1285.44  5014.9 1283.49
  5022.7 1287.37  5025.1 1287.46  5035.6 1290.12  5063.9 1293.69  5128.3 1297.43
  5138.6  1296.7  5176.7 1298.52  5221.1 1301.93  5234.1 1301.07  5288.8 1303.55
#Mann= 7 ,-1 , 0
  4274.8     .07       0  4413.1     .12       0  4713.7     .07       0
  4978.9     .05       0  4990.4     .07       0  5025.1     .12       0
  5176.7     .07       0
Bank Sta=4978.9,4990.4
XS Rating Curve= 0 ,0
Exp/Cntr=0.3,0.1

Type RM Length L Ch R = 1 ,32586   ,455,455,455
BEGIN DESCRIPTION:
SIMMONS CREEK 59.0
END DESCRIPTION:
XS GIS Cut Line= 3
      2135125.01       13899625.        2134625.       13899575.
      2134424.96     13899625.01
#Sta/Elev= 30
  4502.1 1297.07    4507  1297.1  4554.9 1296.73  4693.1 1292.92  4703.1  1293.5
  4723.2 1292.27  4743.3 1292.37  4763.4  1289.5  4773.5 1288.89    4874 1289.21
  4883.6 1289.89  4914.2 1288.93  4924.2  1287.3  4934.3 1284.47  4951.8 1282.08
  4956.9 1283.01  4964.4 1282.95  4978.6 1281.46  4979.1 1280.96  4989.9 1280.96
  4990.4 1281.46  5022.6 1285.08  5056.1 1284.03  5076.8 1284.21  5105.1 1290.77
  5110.3  1290.9  5128.3 1294.14  5164.1 1297.11  5187.6 1300.01  5210.8 1300.78
#Mann= 6 ,-1 , 0
  4502.1     .12       0    4507     .07       0  4883.6     .12       0
  4978.6     .05       0  4990.4     .12       0  5164.1     .07       0
Bank Sta=4978.6,4990.4
XS Rating Curve= 0 ,0
Exp/Cntr=0.3,0.1

Type RM Length L Ch R = 1 ,32131   ,480,480,480
BEGIN DESCRIPTION:
SIMMONS CREEK 58.0
END DESCRIPTION:
XS GIS Cut Line= 3
      2135124.97     13898975.01        2134475.       13899175.
      2134275.04     13899274.98
#Sta/Elev= 30
  4324.1 1301.94  4373.1  1300.1  4402.8 1297.94  4438.5 1294.06  4476.4 1292.16
  4522.9 1291.16  4554.2 1288.21  4612.4  1284.4  4645.1 1283.25    4671  1283.5
  4805.3 1284.37    4868 1285.66  4917.2 1284.14  4941.4 1282.32  4972.8 1281.83
  4987.8 1280.89  4995.6 1278.46  4996.1 1277.96  5007.5 1278.46  5012.5 1281.86
  5062.8 1281.67  5079.6 1280.83  5085.2 1281.35    5102 1286.84  5107.6 1287.11
  5113.6 1288.82  5146.7 1296.36  5174.6 1298.73  5191.4 1302.06  5227.7 1303.58
#Mann= 7 ,-1 , 0
  4324.1     .07       0  4402.8     .12       0    4671     .07       0
    4868     .12       0  4995.6     .05       0  5007.5     .12       0
  5113.6     .07       0
Bank Sta=4995.6,5007.5
XS Rating Curve= 0 ,0
Exp/Cntr=0.3,0.1

Type RM Length L Ch R = 1 ,31651   ,460,460,460
BEGIN DESCRIPTION:
SIMMONS CREEK 57.0
END DESCRIPTION:
XS GIS Cut Line= 3
      2135125.03     13898875.01        2134375.       13898725.
      2133974.99     13899025.01
#Sta/Elev= 30
  4240.3 1302.04  4311.7  1300.2  4332.1 1295.83  4396.5 1289.33  4525.9 1282.82
  4566.7 1283.11  4627.9 1280.82  4718.5 1280.68  4770.6 1281.92    4842 1281.48
    4893 1279.39  4954.2 1280.85  4974.6 1277.48  4980.9 1277.49    4989 1277.34
  4989.5 1276.84  5000.9 1277.34  5002.6 1278.45  5055.2 1278.89  5112.5 1284.27
  5190.5 1287.27  5255.2 1292.11  5297.9 1297.58  5312.5 1302.58  5383.3 1306.35
  5418.7 1312.16  5447.9    1314  5455.2 1316.43  5477.1 1319.75  5505.2 1321.53
#Mann= 7 ,-1 , 0
  4240.3     .07       0  4396.5     .12       0  4718.5    .035       0
  4980.9     .12       0    4989     .05       0  5000.9     .12       0
  5190.5     .07       0
Bank Sta=4989,5000.9
XS Rating Curve= 0 ,0
Exp/Cntr=0.3,0.1

Type RM Length L Ch R = 1 ,31191   ,465,465,465
BEGIN DESCRIPTION:
SIMMONS CREEK 56.0
END DESCRIPTION:
XS GIS Cut Line= 3
      2135325.87     13898368.92        2134275.       13898325.
      2133780.68     13898325.52
#Sta/Elev= 30
  3943.5 1306.87  4034.4 1303.02  4074.5 1296.33  4153.4 1291.37  4314.7 1287.23
  4434.8 1286.23  4454.8 1284.49  4485.8 1283.68  4574.9 1279.69  4662.1 1277.74
  4785.1 1278.27  4825.1 1275.42  4859.2 1276.59  4877.9 1276.41  4905.2 1278.22
  4957.7 1277.06  4985.3 1276.95  4997.8 1275.95  5005.3 1273.91  5019.3 1272.22
  5019.8 1271.72  5031.2 1272.22  5055.3 1277.53  5075.3 1279.57  5125.3 1287.37
  5201.8 1291.85  5295.3 1297.18  5355.3 1298.53  5395.3 1303.04  5489.6 1307.76
#Mann= 8 ,-1 , 0
  3943.5     .07       0  4485.8     .12       0  4662.1    .035       0
  4859.2     .07       0  4957.7     .12       0  5019.3     .05       0
  5031.2     .12       0  5201.8     .07       0
Bank Sta=5019.3,5031.2
XS Rating Curve= 0 ,0
Exp/Cntr=0.3,0.1

Type RM Length L Ch R = 1 ,30726   ,480,480,480
BEGIN DESCRIPTION:
SIMMONS CREEK 55.0
END DESCRIPTION:
XS GIS Cut Line= 3
      2134925.02       13898075.        2134225.       13897875.
      2133859.73     13898051.72
#Sta/Elev= 30
    4272 1286.03  4303.2 1286.05  4351.7  1283.9  4396.3 1282.34  4490.6 1278.58
    4636 1277.06  4666.8 1274.83    4740 1270.49  4759.5 1271.71  4764.7 1271.13
  4771.2 1273.28  4781.6 1273.92  4837.5 1276.01  4905.2 1274.78  4910.3 1275.16
  4944.1 1272.02  4958.4 1272.06  4977.1  1266.6  4977.6  1266.1  4989.1  1266.6
  4989.6 1270.43  4997.4 1272.11  5002.8 1272.11  5008.5 1274.68  5014.1 1274.49
  5053.7  1279.8  5149.6 1284.48  5172.2 1286.89  5236.4 1288.64  5405.8 1293.27
#Mann= 9 ,-1 , 0
    4272     .07       0  4351.7     .12       0  4396.3     .07       0
  4490.6     .12       0  4666.8     .07       0  4905.2     .12       0
  4977.1     .05       0  4989.1     .12       0  5236.4     .07       0
Bank Sta=4977.1,4989.1
XS Rating Curve= 0 ,0
Exp/Cntr=0.3,0.1

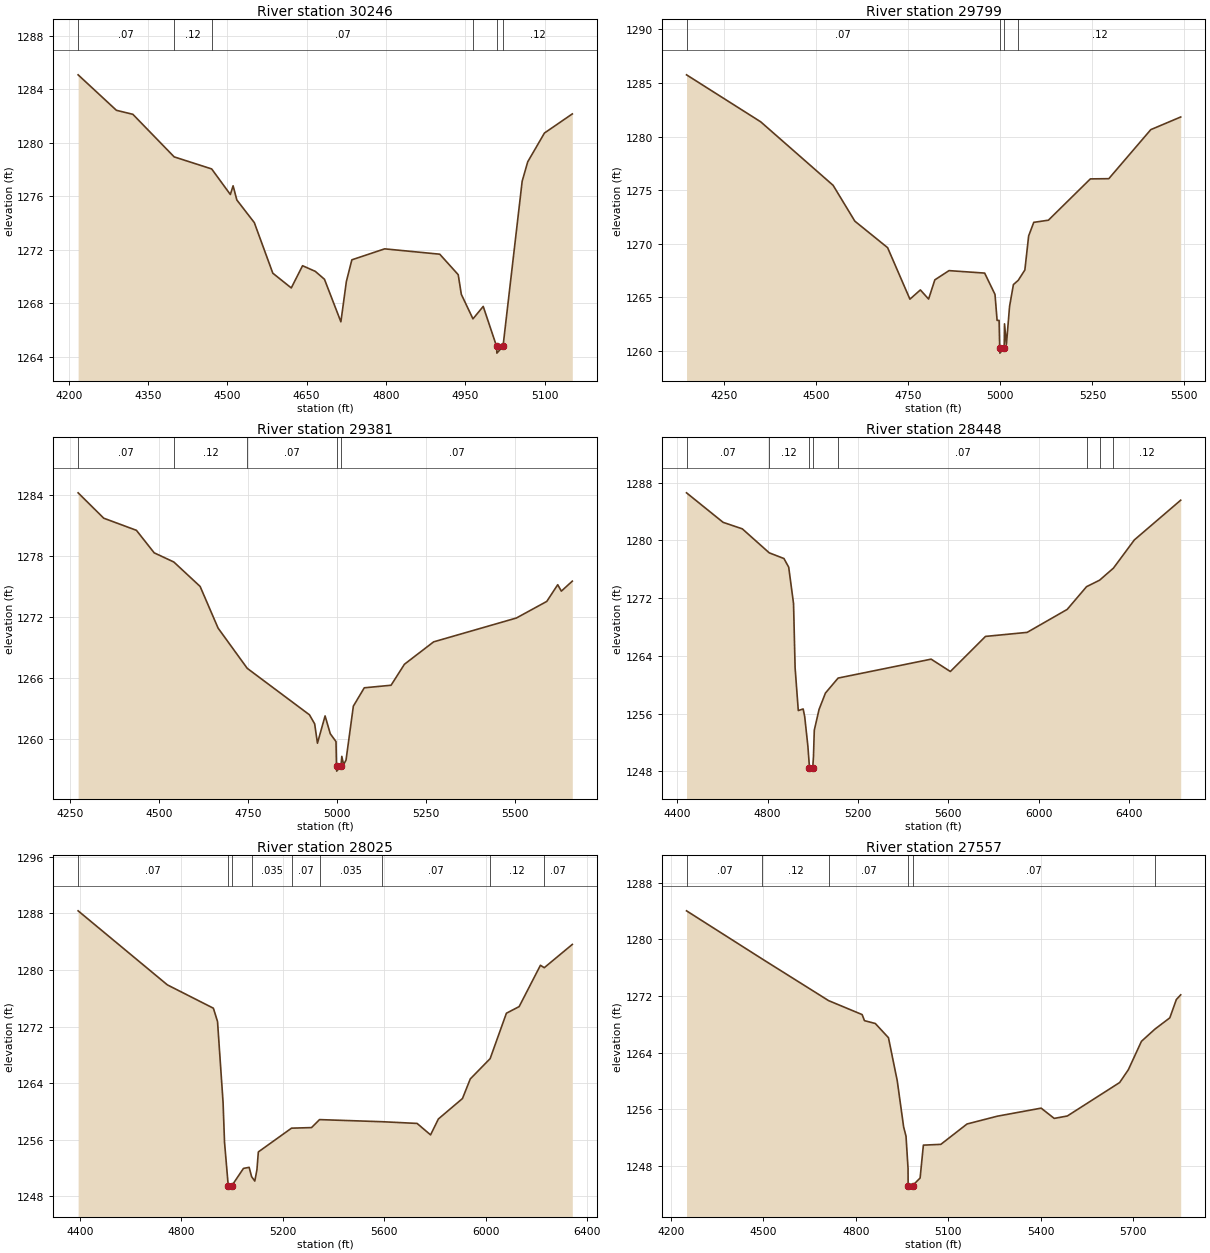
Type RM Length L Ch R = 1 ,30246   ,447,447,447
BEGIN DESCRIPTION:
SIMMONS CREEK 54.0
END DESCRIPTION:
XS GIS Cut Line= 3
        2134975.       13897625.        2134225.       13897425.
      2134075.02     13897474.99
#Sta/Elev= 30
  4217.9 1285.08  4290.3 1282.43  4321.4 1282.13  4399.5 1278.95  4470.4 1278.05
  4505.7 1276.14  4510.9 1276.79    4518 1275.73    4551 1274.04    4586 1270.26
  4620.9 1269.16  4642.2 1270.82  4666.2  1270.4  4683.6 1269.81  4714.7 1266.63
    4725 1269.63  4735.4 1271.26  4797.5 1272.08  4901.6 1271.68  4936.5 1270.15
  4942.4 1268.68  4964.4 1266.85  4983.8 1267.78  5009.1 1264.79  5009.6 1264.29
  5021.2 1264.79  5057.4 1277.13  5067.9 1278.58  5099.5 1280.73  5152.2 1282.16
#Mann= 6 ,-1 , 0
  4217.9     .07       0  4399.5     .12       0  4470.4     .07       0
  4964.4     .12       0  5009.1     .05       0  5021.2     .12       0
Bank Sta=5009.1,5021.2
XS Rating Curve= 0 ,0
Exp/Cntr=0.3,0.1

Type RM Length L Ch R = 1 ,29799   ,418,418,418
BEGIN DESCRIPTION:
SIMMONS CREEK 53.0
END DESCRIPTION:
XS GIS Cut Line= 3
      2135136.23     13897395.06        2134375.       13897025.
      2133896.58     13897155.46
#Sta/Elev= 30
  4147.6 1285.75  4349.1 1281.37  4545.8 1275.45  4604.8 1272.11  4693.8 1269.64
  4754.4 1264.84  4782.8  1265.7  4805.1 1264.85  4822.1 1266.64  4860.6  1267.5
  4957.4 1267.27  4985.5 1265.28  4991.2 1262.86  4996.6 1262.86  4998.3 1260.31
  4998.8 1259.81  5010.5 1260.31  5011.3 1262.54  5016.5 1260.62  5025.1 1264.18
  5035.5  1266.2  5048.7  1266.6  5066.6 1267.56  5076.9 1270.74  5090.8    1272
  5130.5  1272.2  5244.5 1276.05  5294.6 1276.07  5408.6 1280.64  5489.9 1281.82
#Mann= 4 ,-1 , 0
  4147.6     .07       0  4998.3     .05       0  5010.5     .07       0
  5048.7     .12       0
Bank Sta=4998.3,5010.5
XS Rating Curve= 0 ,0
Exp/Cntr=0.3,0.1

Type RM Length L Ch R = 1 ,29381   ,933,933,933
BEGIN DESCRIPTION:
SIMMONS CREEK 52.0
END DESCRIPTION:
XS GIS Cut Line= 3
        2135157.     13897103.36        2134575.       13896675.
      2133925.02     13896824.99
#Sta/Elev= 30
  4271.5 1284.17  4343.5 1281.68  4435.4 1280.49  4485.4 1278.28  4540.6 1277.38
  4614.6 1274.98  4665.1 1270.89  4747.1 1266.94    4922 1262.38  4936.7 1261.49
  4944.5 1259.59    4966 1262.27  4980.6 1260.52  4996.7 1259.75  4998.1 1257.35
  4998.6 1256.85  5010.7 1257.35    5013  1258.3  5018.1 1257.49  5024.9 1257.94
  5045.5 1263.23  5076.2 1265.03  5151.5 1265.28  5189.1 1267.34  5271.2 1269.54
  5503.9 1271.88  5589.4 1273.51  5620.2 1275.15  5630.4 1274.52  5661.2  1275.5
#Mann= 5 ,-1 , 0
  4271.5     .07       0  4540.6     .12       0  4747.1     .07       0
  4998.1     .05       0  5010.7     .07       0
Bank Sta=4998.1,5010.7
XS Rating Curve= 0 ,0
Exp/Cntr=0.3,0.1

Type RM Length L Ch R = 1 ,28448   ,423,423,423
BEGIN DESCRIPTION:
SIMMONS CREEK 51.0
END DESCRIPTION:
XS GIS Cut Line= 3
      2135209.11     13895520.03        2134825.       13895925.
      2133625.03     13897024.98
#Sta/Elev= 30
  4441.8 1286.59  4603.7  1282.5  4688.7  1281.6  4807.6 1278.28  4872.7 1277.49
  4893.8 1276.29  4915.2 1271.24  4922.1 1262.36  4936.2 1256.43  4957.7 1256.65
  4964.6 1255.58  4978.7 1251.48  4985.7 1248.54  4986.2 1248.04  5000.1 1248.54
  5003.3 1250.01    5007 1253.71    5028 1256.58  5056.4 1258.86  5112.3 1260.93
  5523.8 1263.55  5608.9 1261.84  5764.3  1266.7  5948.6 1267.26  6125.6 1270.44
  6211.3 1273.59  6269.1 1274.49  6330.3 1276.16  6422.8 1280.07  6627.8 1285.57
#Mann= 8 ,-1 , 0
  4441.8     .07       0  4807.6     .12       0  4985.7     .05       0
  5000.1     .12       0  5112.3     .07       0  6211.3     .12       0
  6269.1     .07       0  6330.3     .12       0
Bank Sta=4985.7,5000.1
XS Rating Curve= 0 ,0
Exp/Cntr=0.3,0.1

Type RM Length L Ch R = 1 ,28025   ,468,468,468
BEGIN DESCRIPTION:
SIMMONS CREEK 50.0
END DESCRIPTION:
XS GIS Cut Line= 3
      2135110.18     13895337.73        2134575.       13895625.
      2133375.04     13896224.98
#Sta/Elev= 30
  4392.6 1288.37  4744.6  1277.9  4926.1  1274.6  4942.4 1272.72  4964.3 1261.25
    4970 1255.65  4984.6 1249.52  4985.1 1249.02  4999.1 1249.52  5044.7 1251.95
  5067.1  1252.1  5076.8 1250.78  5089.4 1250.16  5097.8 1251.76  5103.4 1254.28
  5234.2 1257.64  5313.1 1257.72  5344.7 1258.85  5592.3 1258.55  5729.5 1258.31
  5782.6 1256.69  5813.4 1258.94  5908.4 1261.83  5939.2  1264.6  6017.5 1267.47
  6081.7 1273.89    6132 1274.83  6215.9 1280.67    6231 1280.33  6341.6 1283.62
#Mann= 9 ,-1 , 0
  4392.6     .07       0  4984.6     .05       0  4999.1     .07       0
  5076.8    .035       0  5234.2     .07       0  5344.7    .035       0
  5592.3     .07       0  6017.5     .12       0    6231     .07       0
Bank Sta=4984.6,4999.1
XS Rating Curve= 0 ,0
Exp/Cntr=0.3,0.1

Type RM Length L Ch R = 1 ,27557   ,463,463,463
BEGIN DESCRIPTION:
SIMMONS CREEK 49.0
END DESCRIPTION:
XS GIS Cut Line= 3
      2134740.36     13894926.28        2134175.       13895425.
      2133575.02     13896024.98
#Sta/Elev= 30
  4250.9 1284.04  4496.4 1277.23  4711.7 1271.34  4820.3 1269.37  4827.9 1268.51
    4863 1268.11  4905.7  1266.1  4934.1 1260.03    4955 1253.46  4962.6 1252.18
  4969.2 1247.61  4969.5 1245.19    4970 1244.69  4983.5 1244.69    4984 1245.19
  5008.3 1246.26  5018.9 1250.91  5075.5 1251.02  5160.4  1253.9  5259.4 1255.01
  5400.8 1256.14  5443.2 1254.69  5485.6 1255.03  5655.3 1259.76  5683.6 1261.58
    5726 1265.59  5769.6 1267.31    5818 1268.91  5839.2  1271.5  5853.3 1272.16
#Mann= 6 ,-1 , 0
  4250.9     .07       0  4496.4     .12       0  4711.7     .07       0
  4969.5     .05       0    4984     .07       0  5769.6     .12       0
Bank Sta=4969.5,4984
XS Rating Curve= 0 ,0
Exp/Cntr=0.3,0.1

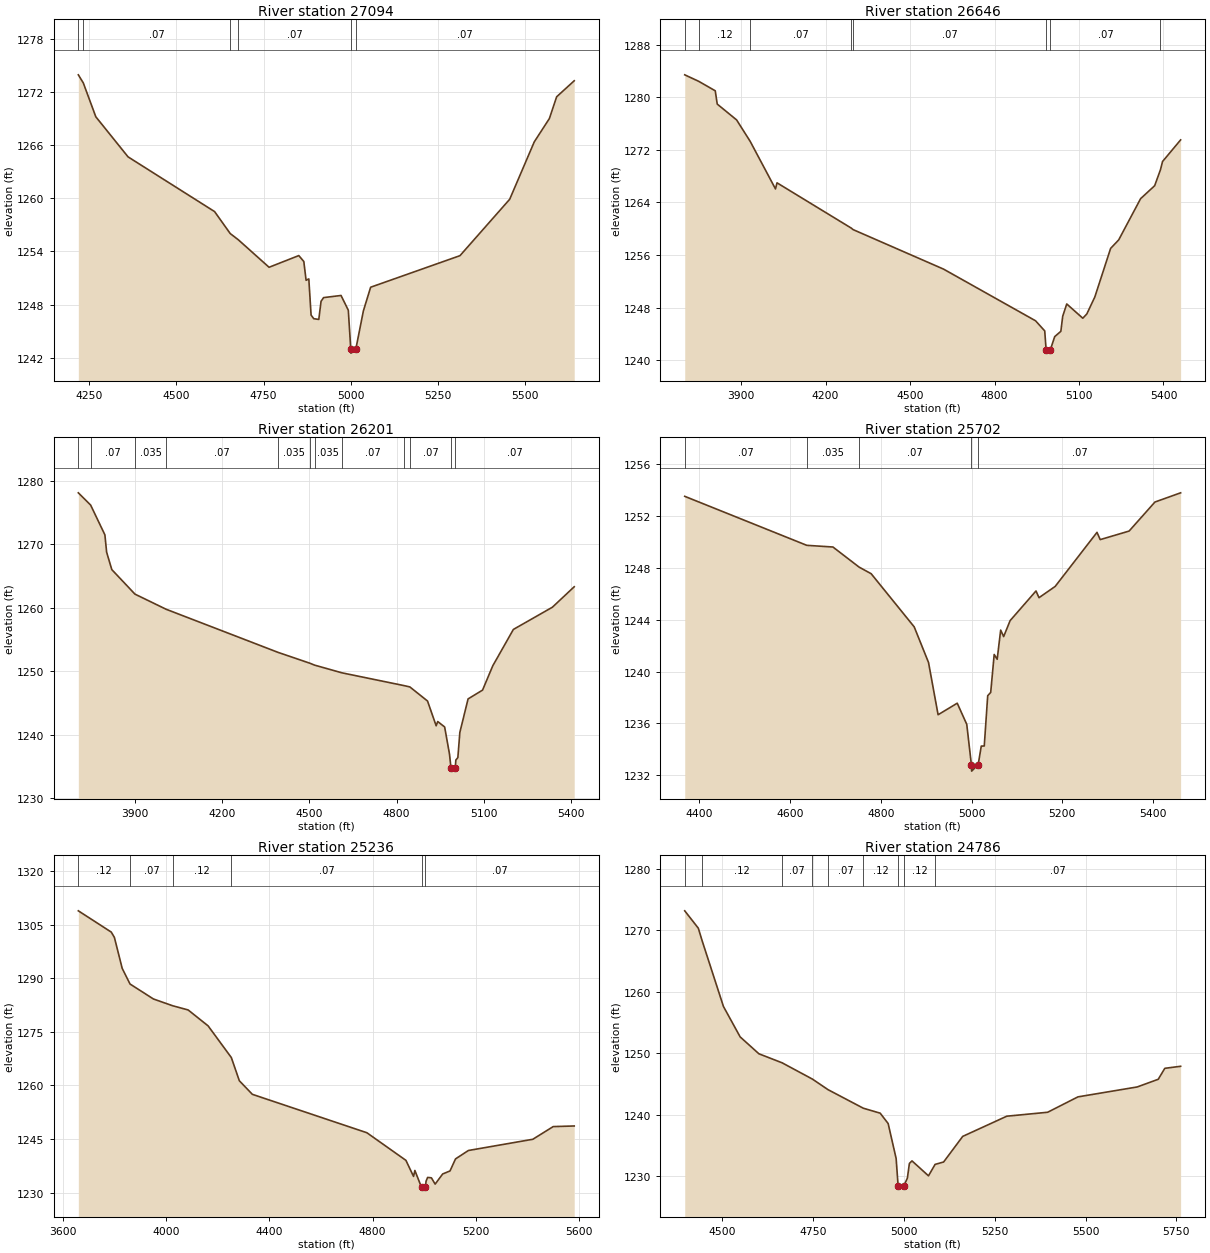
Type RM Length L Ch R = 1 ,27094   ,448,448,448
BEGIN DESCRIPTION:
SIMMONS CREEK 48.0
END DESCRIPTION:
XS GIS Cut Line= 3
      2134374.97     13894825.02        2133775.       13895325.
        2133375.       13895825.
#Sta/Elev= 30
    4219 1273.91  4233.3 1272.99  4269.1 1269.18  4361.5 1264.66  4609.5 1258.49
  4654.4 1256.01  4677.6 1255.31  4765.7 1252.21  4850.9 1253.53  4865.3 1252.86
  4871.8 1250.74  4879.6  1250.9  4886.1 1246.82  4893.9 1246.41  4908.2 1246.33
  4914.7 1248.37  4921.9 1248.79    4972 1249.03  4992.8 1247.37  4999.8 1243.03
  5000.3 1242.53  5014.6 1243.03    5036 1247.29  5056.8 1249.96  5312.9 1253.52
  5455.4 1259.88  5525.8 1266.35  5569.1 1268.98  5589.9 1271.43  5640.3 1273.24
#Mann= 6 ,-1 , 0
    4219     .12       0  4233.3     .07       0  4654.4    .035       0
  4677.6     .07       0  4999.8     .05       0  5014.6     .07       0
Bank Sta=4999.8,5014.6
XS Rating Curve= 0 ,0
Exp/Cntr=0.3,0.1

Type RM Length L Ch R = 1 ,26646   ,445,445,445
BEGIN DESCRIPTION:
SIMMONS CREEK 47.0
END DESCRIPTION:
XS GIS Cut Line= 3
      2134575.03     13894674.99        2133375.       13895175.
      2133025.01     13895474.99
#Sta/Elev= 30
  3699.9  1283.4  3749.2 1282.42  3808.3 1280.97  3815.3 1278.95  3884.1 1276.54
  3932.3 1273.28  4022.2 1266.04  4027.6 1266.97  4291.3 1260.08  4297.9 1259.85
  4619.1 1253.84  4945.8 1245.98  4978.3 1244.44  4983.3 1241.56  4983.8 1241.06
  4998.2 1241.56  5013.7 1243.57  5035.6 1244.38  5042.2 1246.67  5056.5 1248.54
  5113.5 1246.37  5127.8 1247.02  5156.3 1249.61  5212.3 1256.99  5240.9 1258.28
  5318.8 1264.56  5368.7 1266.53  5389.3 1268.96  5396.7 1270.21  5460.9  1273.5
#Mann= 8 ,-1 , 0
  3699.9     .07       0  3749.2     .12       0  3932.3     .07       0
  4291.3    .035       0  4297.9     .07       0  4983.3     .05       0
  4998.2     .07       0  5389.3     .12       0
Bank Sta=4983.3,4998.2
XS Rating Curve= 0 ,0
Exp/Cntr=0.3,0.1

Type RM Length L Ch R = 1 ,26201   ,499,499,499
BEGIN DESCRIPTION:
SIMMONS CREEK 46.0
END DESCRIPTION:
XS GIS Cut Line= 3
      2134274.96     13894375.02        2133075.       13894875.
      2132798.84     13895174.98
#Sta/Elev= 30
  3704.1 1278.08  3746.5 1276.15  3795.6 1271.46  3801.6 1268.72  3819.4 1265.99
  3899.1 1262.13  4006.3 1259.75  4391.8 1252.96  4501.5 1251.25  4517.7 1250.95
  4611.7 1249.74  4824.3 1247.74  4845.7 1247.52  4906.6  1245.3  4936.4  1241.4
  4941.8 1242.07  4965.6 1241.21  4982.4 1236.92  4987.4 1234.76  4987.9 1234.26
  5002.3 1234.76  5004.1    1236  5011.1 1236.39  5017.9 1240.35  5046.3 1245.63
  5096.2 1247.02  5131.4 1250.85  5202.3 1256.57  5336.7 1260.07  5411.8 1263.29
#Mann= 12 ,-1 , 0
  3704.1     .12       0  3746.5     .07       0  3899.1    .035       0
  4006.3     .07       0  4391.8    .035       0  4501.5     .07       0
  4517.7    .035       0  4611.7     .07       0  4824.3    .035       0
  4845.7     .07       0  4987.4     .05       0  5002.3     .07       0
Bank Sta=4987.4,5002.3
XS Rating Curve= 0 ,0
Exp/Cntr=0.3,0.1

Type RM Length L Ch R = 1 ,25702   ,466,466,466
BEGIN DESCRIPTION:
SIMMONS CREEK 45.0
END DESCRIPTION:
XS GIS Cut Line= 3
      2133675.02     13894575.01        2133075.       13894375.
      2132724.97     13894675.03
#Sta/Elev= 30
  4367.5 1253.52  4636.6 1249.74  4694.3 1249.61    4752 1248.06  4778.6 1247.55
  4873.5 1243.45  4905.1  1240.7  4926.2 1236.67  4968.4 1237.56  4989.4 1235.93
  4999.6 1232.82  5000.1 1232.32  5014.6 1232.82  5021.4 1234.25    5028 1234.26
  5035.6 1238.14  5042.2 1238.39  5049.9 1241.32  5056.5 1240.95  5064.2  1243.2
  5070.8  1242.7    5085 1243.93  5142.1 1246.22  5148.7  1245.7  5184.4 1246.57
  5276.6 1250.74  5283.7 1250.18  5347.4 1250.84  5404.4 1253.08    5461 1253.79
#Mann= 5 ,-1 , 0
  4367.5     .07       0  4636.6    .035       0    4752     .07       0
  4999.6     .05       0  5014.6     .07       0
Bank Sta=4999.6,5014.6
XS Rating Curve= 0 ,0
Exp/Cntr=0.3,0.1

Type RM Length L Ch R = 1 ,25236   ,450,450,450
BEGIN DESCRIPTION:
SIMMONS CREEK 44.0
END DESCRIPTION:
XS GIS Cut Line= 3
      2134453.47     13893742.18        2133125.       13893925.
       2132660.9     13894276.05
#Sta/Elev= 30
  3659.1 1308.84  3786.8 1302.89  3798.9 1301.41  3829.2 1292.74  3859.6 1288.36
  3950.3 1284.17  4025.2 1282.27  4084.9  1281.1  4162.3 1276.65  4252.4 1267.78
  4283.4 1261.29  4333.9 1257.49    4778 1246.74  4929.4 1239.01    4959 1234.52
  4964.1 1236.18  4989.9 1231.46  4990.4 1230.96  5005.3 1231.46  5007.4 1233.15
  5013.6 1234.24  5028.2 1234.12  5042.7 1232.36  5071.9  1235.2  5100.4 1236.05
  5121.8 1239.42  5171.7 1241.77  5421.5 1244.91  5500.5 1248.46    5582 1248.63
#Mann= 6 ,-1 , 0
  3659.1     .12       0  3859.6     .07       0  4025.2     .12       0
  4252.4     .07       0  4989.9     .05       0  5005.3     .07       0
Bank Sta=4989.9,5005.3
XS Rating Curve= 0 ,0
Exp/Cntr=0.3,0.1

Type RM Length L Ch R = 1 ,24786   ,470,470,470
BEGIN DESCRIPTION:
SIMMONS CREEK 43.0
END DESCRIPTION:
XS GIS Cut Line= 3
      2133525.02     13893274.99        2132975.       13893525.
      2132675.02     13894224.96
#Sta/Elev= 30
  4396.1 1273.13  4433.5 1270.31  4444.5 1268.18  4502.7 1257.59  4548.8 1252.64
  4600.4  1249.9  4664.1 1248.44  4747.7 1245.79  4790.8 1244.07  4887.8 1241.06
  4934.4 1240.25  4956.3 1238.57  4978.3 1232.89  4983.8 1228.41  4984.3 1227.91
  4999.2 1228.41  5009.3  1229.7  5014.8 1232.08    5022  1232.5  5067.4 1230.07
  5085.6 1231.93  5109.1 1232.32  5161.7 1236.48  5283.1 1239.76  5395.6  1240.4
    5479  1242.9  5642.2 1244.51  5700.2 1245.76  5718.3 1247.54  5761.8 1247.87
#Mann= 9 ,-1 , 0
  4396.1     .07       0  4444.5     .12       0  4664.1     .07       0
  4747.7     .12       0  4790.8     .07       0  4887.8     .12       0
  4983.8     .05       0  4999.2     .12       0  5085.6     .07       0
Bank Sta=4983.8,4999.2
XS Rating Curve= 0 ,0
Exp/Cntr=0.3,0.1

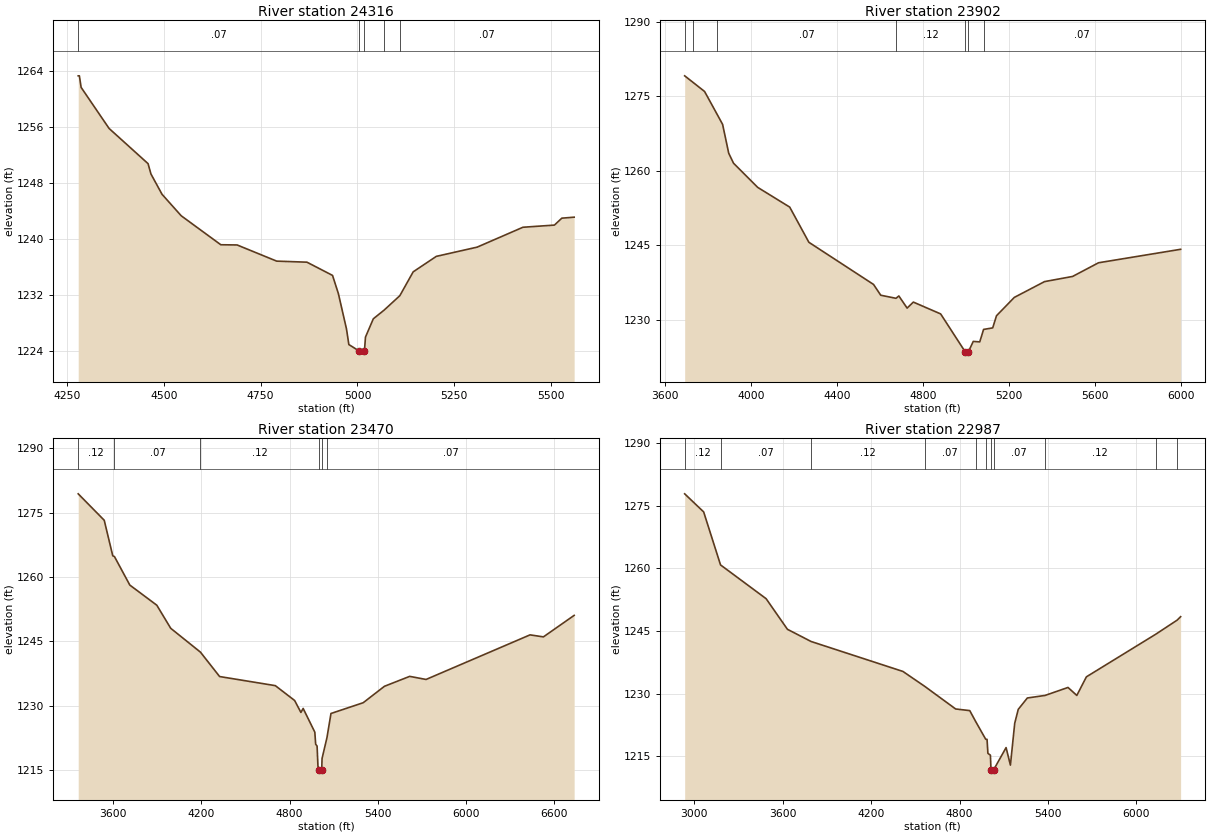
Type RM Length L Ch R = 1 ,24316   ,414,414,414
BEGIN DESCRIPTION:
SIMMONS CREEK 42.0
END DESCRIPTION:
XS GIS Cut Line= 3
      2133225.03     13892824.98        2132625.       13893225.
      2132524.99     13893775.04
#Sta/Elev= 30
  4279.1 1263.31  4282.1 1263.31  4286.6 1261.66  4358.8 1255.79  4459.4 1250.76
  4466.9 1249.28  4495.5 1246.38    4545 1243.31  4647.2 1239.17  4689.3 1239.14
  4791.4 1236.83  4869.5 1236.68  4935.6 1234.79  4950.7 1232.19  4971.7 1227.12
  4977.7 1224.91  5002.7 1224.04  5003.2 1223.54  5018.1 1224.04  5020.6 1225.97
  5040.9 1228.59  5068.8 1229.83  5109.3 1231.89  5143.8  1235.3  5203.5 1237.51
    5309 1238.83  5427.1 1241.67  5508.4 1241.98  5527.5 1242.97  5559.3 1243.11
#Mann= 5 ,-1 , 0
  4279.1     .07       0  5002.7     .05       0  5018.1     .07       0
  5068.8    .035       0  5109.3     .07       0
Bank Sta=5002.7,5018.1
XS Rating Curve= 0 ,0
Exp/Cntr=0.3,0.1

Type RM Length L Ch R = 1 ,23902   ,432,432,432
BEGIN DESCRIPTION:
SIMMONS CREEK 41.0
END DESCRIPTION:
XS GIS Cut Line= 3
      2133443.36     13892449.25        2132275.       13893025.
        2132375.     13894024.99
#Sta/Elev= 30
  3692.6 1279.11  3732.4 1277.76  3785.2 1275.96  3843.9 1271.34  3869.1 1269.34
  3897.5 1263.54  3919.9 1261.53  4032.2 1256.67  4181.3  1252.7  4270.5 1245.62
  4571.3 1237.14  4604.9 1234.97  4675.8 1234.35  4689.1 1234.82  4727.6 1232.38
  4756.5 1233.59  4883.6 1231.21  4997.3 1223.62  4997.8 1223.12    5013 1223.62
  5035.3 1225.68  5065.5 1225.58  5083.3 1228.09  5125.8  1228.4  5143.4 1230.84
  5226.3 1234.53    5367 1237.71  5497.6 1238.75  5618.2  1241.5  6000.1 1244.21
#Mann= 7 ,-1 , 0
  3692.6     .07       0  3732.4     .12       0  3843.9     .07       0
  4675.8     .12       0  4997.3     .05       0    5013     .12       0
  5083.3     .07       0
Bank Sta=4997.3,5013
XS Rating Curve= 0 ,0
Exp/Cntr=0.3,0.1

Type RM Length L Ch R = 1 ,23470   ,483,483,483
BEGIN DESCRIPTION:
SIMMONS CREEK 40.0
END DESCRIPTION:
XS GIS Cut Line= 3
       2133273.3     13892068.87        2131875.       13892925.
      2132133.42     13894641.89
#Sta/Elev= 30
  3361.2  1279.4  3538.3 1273.24  3596.4 1264.96  3607.9 1264.78  3712.5 1258.14
  3896.2 1253.45  3990.9 1248.07  4193.4 1242.51  4323.7 1236.83  4702.9 1234.71
  4834.4 1231.25    4877 1228.47  4892.4  1229.4  4971.8 1223.87  4977.6 1221.07
  4987.2 1220.63  4993.1 1215.96    5003 1215.06  5003.5 1214.56  5018.7 1215.06
    5021 1217.73  5054.7 1222.65  5081.7 1228.22  5301.1 1230.73  5445.7 1234.56
  5617.6 1236.87  5728.9 1236.15  6436.8 1246.54  6527.8 1246.07    6737 1251.08
#Mann= 6 ,-1 , 0
  3361.2     .12       0  3607.9     .07       0  4193.4     .12       0
    5003     .05       0  5018.7     .12       0  5054.7     .07       0
Bank Sta=5003,5018.7
XS Rating Curve= 0 ,0
Exp/Cntr=0.3,0.1

Type RM Length L Ch R = 1 ,22987   ,566,566,566
BEGIN DESCRIPTION:
SIMMONS CREEK 39.0
END DESCRIPTION:
XS GIS Cut Line= 3
      2133206.09     13891980.15        2131425.       13893025.
      2130224.47     13893522.59
#Sta/Elev= 30
    2935 1277.83  3063.8  1273.5  3178.3 1260.82  3487.5 1252.74    3632 1245.42
  3792.4  1242.5  4415.7 1235.33  4563.3 1231.77  4773.3 1226.35    4869 1225.96
  4910.4 1223.27  4977.3  1219.1  4986.3 1219.09  4992.1 1215.73  5009.2 1215.29
    5013 1211.74  5013.5 1211.24  5030.1 1211.74  5115.5 1217.11  5144.8 1212.92
  5174.1 1222.94    5198 1226.26  5259.7 1228.98  5379.8 1229.59  5535.6  1231.5
  5595.3 1229.59  5660.3 1234.04  6129.2  1244.2    6276 1247.61  6299.5 1248.43
#Mann= 11 ,-1 , 0
    2935     .12       0  3178.3     .07       0  3792.4     .12       0
  4563.3     .07       0  4910.4     .12       0  4977.3     .07       0
    5013     .05       0  5030.1     .07       0  5379.8     .12       0
  6129.2     .07       0    6276     .12       0
Bank Sta=5013,5030.1
XS Rating Curve= 0 ,0
Exp/Cntr=0.3,0.1