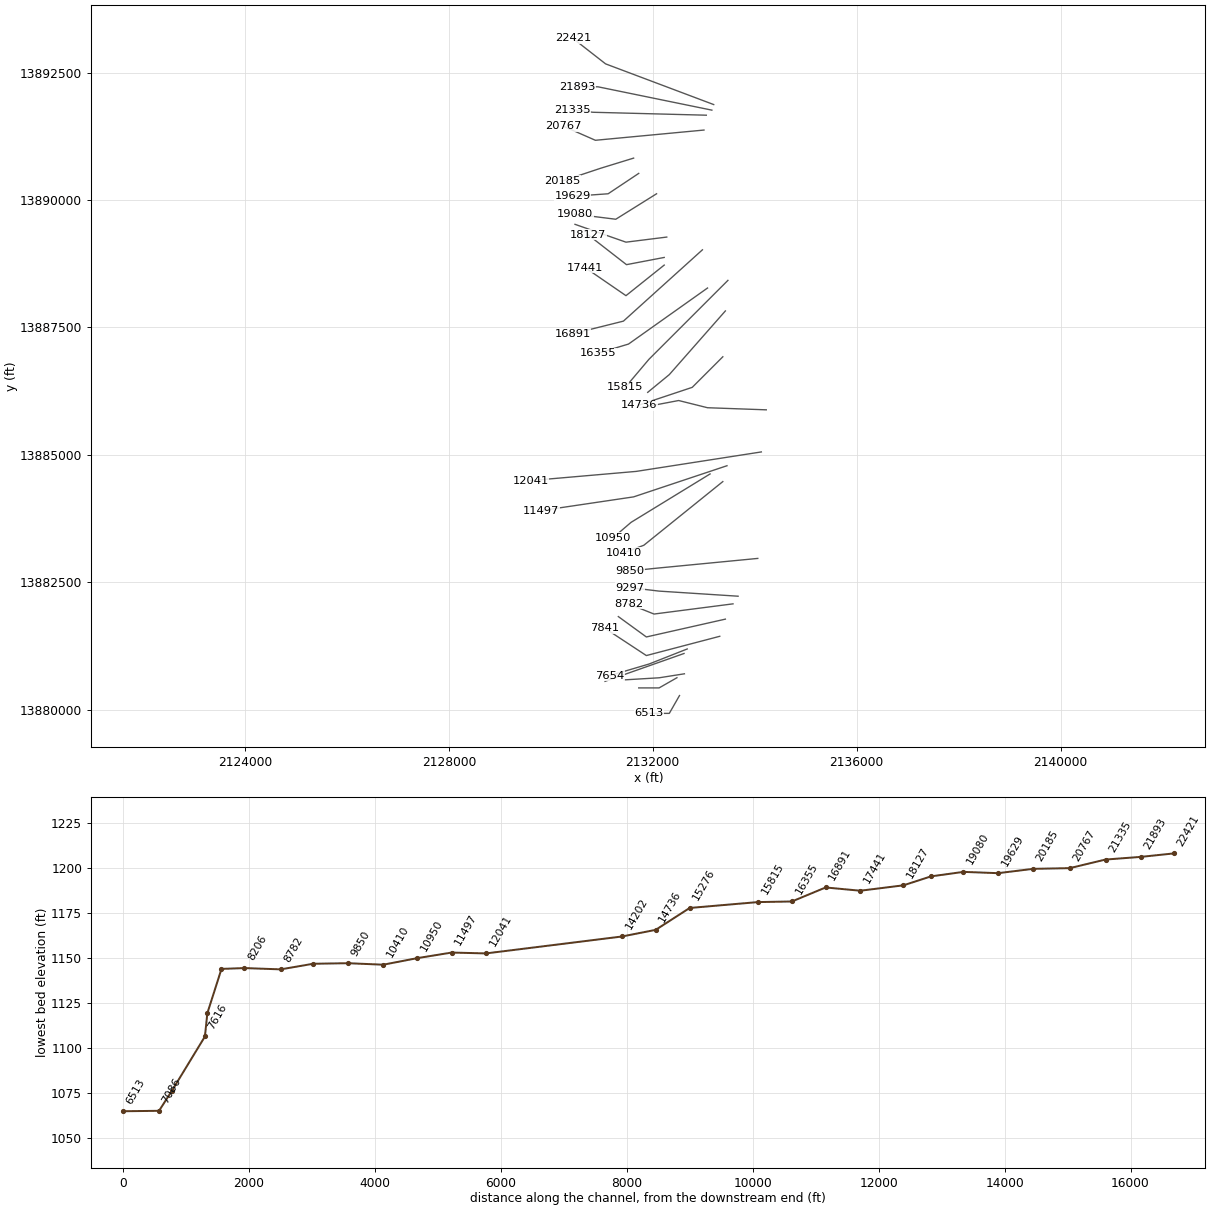
HEC-RAS study SIMMONS CREEK.prj: SIMMONS CREEK Base Level Engineering

--- SIMMONS CREEK.g01 (geometry) --- (continued)

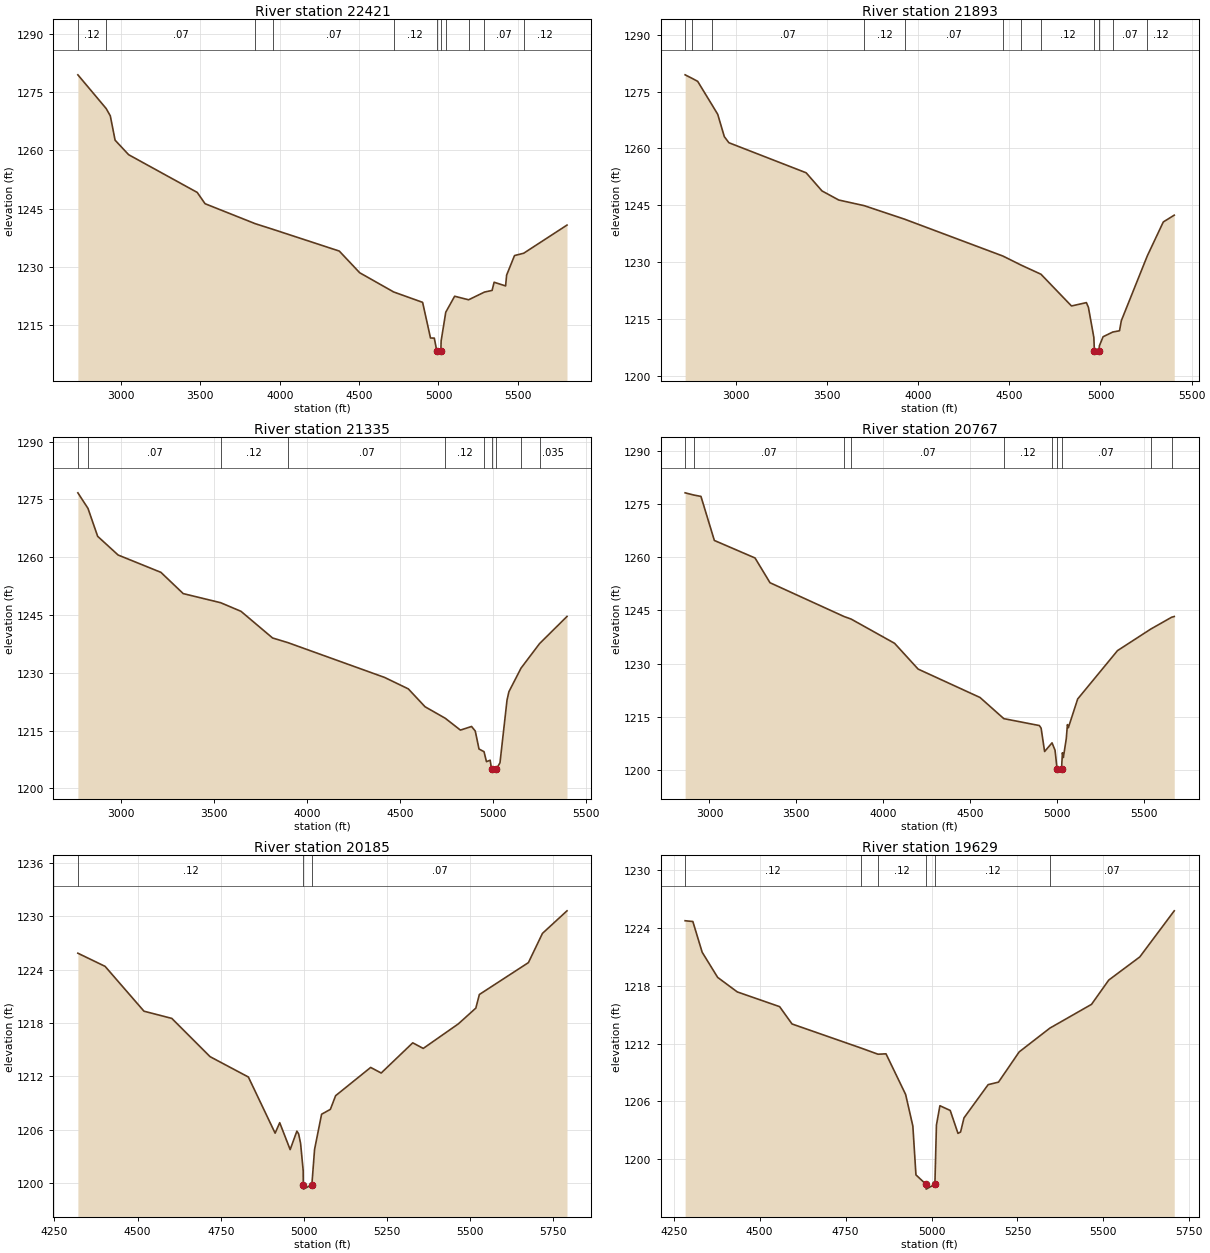
Type RM Length L Ch R = 1 ,22421   ,528,528,528
BEGIN DESCRIPTION:
SIMMONS CREEK 38.0
END DESCRIPTION:
XS GIS Cut Line= 3
      2133196.15     13891876.08        2131075.       13892675.
      2130433.06     13893176.29
#Sta/Elev= 30
  2728.6  1279.4  2906.5 1270.75  2932.9 1268.86  2963.1  1262.6  3048.4 1258.87
  3480.3 1249.18    3530 1246.27    3846 1241.14    3958 1239.68  4375.4  1234.1
  4503.9 1228.53  4717.8 1223.59  4900.2 1220.92  4949.9 1211.76  4973.8 1211.73
  4989.9 1208.37  4990.4 1207.87    5015 1208.37  5016.9 1211.02    5046 1218.38
  5101.9 1222.49  5189.9 1221.58  5289.8 1223.56  5337.8 1223.99  5350.7 1226.09
    5423 1225.14  5429.4 1227.92  5479.1 1232.95  5536.8 1233.54  5809.7 1240.78
#Mann= 11 ,-1 , 0
  2728.6     .12       0  2906.5     .07       0    3846     .12       0
    3958     .07       0  4717.8     .12       0  4989.9     .05       0
    5015     .12       0    5046     .07       0  5189.9     .12       0
  5289.8     .07       0  5536.8     .12       0
Bank Sta=4989.9,5015
XS Rating Curve= 0 ,0
Exp/Cntr=0.3,0.1

Type RM Length L Ch R = 1 ,21893   ,558,558,558
BEGIN DESCRIPTION:
SIMMONS CREEK 37.0
END DESCRIPTION:
XS GIS Cut Line= 3
      2133160.14     13891766.73        2130925.       13892225.
      2130525.04       13892225.
#Sta/Elev= 30
    2723 1279.42  2758.7 1278.55  2791.8  1277.7  2872.2 1271.35  2901.8 1268.99
    2938 1263.09    2963 1261.49  3386.6 1253.55  3473.4 1248.76  3565.3 1246.36
  3704.8 1244.87  3926.3  1241.3  4465.1 1231.57  4565.3 1229.17    4674 1226.76
  4841.3 1218.38    4923 1219.27  4934.1 1218.01  4963.8 1210.08  4966.8 1206.43
  4967.3 1205.93    4992 1206.43  4994.4 1207.89  5014.6 1210.26  5067.6  1211.5
  5104.6 1211.84  5114.6 1214.51  5256.8  1231.6  5344.6 1240.57  5404.6 1242.36
#Mann= 12 ,-1 , 0
    2723     .07       0  2758.7     .12       0  2872.2     .07       0
  3704.8     .12       0  3926.3     .07       0  4465.1     .12       0
  4565.3     .07       0    4674     .12       0  4966.8     .05       0
    4992     .12       0  5067.6     .07       0  5256.8     .12       0
Bank Sta=4966.8,4992
XS Rating Curve= 0 ,0
Exp/Cntr=0.3,0.1

Type RM Length L Ch R = 1 ,21335   ,568,568,568
BEGIN DESCRIPTION:
SIMMONS CREEK 36.0
END DESCRIPTION:
XS GIS Cut Line= 3
      2133051.32     13891667.44        2130825.       13891725.
      2130424.98       13891775.
#Sta/Elev= 30
  2767.8  1276.7  2822.2 1272.66  2874.2 1265.41  2984.2 1260.56  3214.3 1256.06
  3334.3 1250.54  3535.5 1248.18  3645.1 1245.94  3814.5 1239.03  3897.5 1237.81
  4417.1 1228.78  4544.7 1225.81  4634.7 1221.17  4743.5 1218.18  4824.8 1215.11
  4884.8 1216.05  4904.8 1214.86  4924.8  1210.2  4951.9 1209.51  4964.9 1206.92
  4984.9 1207.29  4992.3 1204.96  4992.8 1204.46  5017.5 1204.96  5037.7 1206.63
  5075.5  1222.9  5085.6 1225.07  5150.9  1231.2  5250.6 1237.57    5398 1244.61
#Mann= 10 ,-1 , 0
  2767.8     .12       0  2822.2     .07       0  3535.5     .12       0
  3897.5     .07       0  4743.5     .12       0  4951.9     .07       0
  4992.3     .05       0  5017.5     .07       0  5150.9     .12       0
  5250.6    .035       0
Bank Sta=4992.3,5017.5
XS Rating Curve= 0 ,0
Exp/Cntr=0.3,0.1

Type RM Length L Ch R = 1 ,20767   ,582,582,582
BEGIN DESCRIPTION:
SIMMONS CREEK 35.0
END DESCRIPTION:
XS GIS Cut Line= 3
      2133005.82     13891375.98        2130875.       13891175.
      2130255.95     13891447.13
#Sta/Elev= 30
  2859.8 1278.16  2908.5 1277.55    2951 1277.15  3028.2 1264.73  3262.4 1259.79
  3348.6 1252.81  3775.6 1243.27  3815.6 1242.57  4065.9 1235.73  4201.5 1228.46
  4558.1 1220.45  4694.9 1214.49  4899.6 1212.54  4909.7 1211.81  4929.8 1205.22
  4972.6 1207.67    4990 1205.56  5001.8 1200.19  5002.3 1199.69  5027.1 1200.19
  5032.4 1204.87  5037.8 1203.53  5054.7 1208.87  5061.2  1212.8  5066.6 1211.94
  5120.2 1220.03  5349.6 1233.67    5541 1239.74  5660.8 1243.07  5676.3 1243.29
#Mann= 10 ,-1 , 0
  2859.8     .12       0  2908.5     .07       0  3775.6     .12       0
  3815.6     .07       0  4694.9     .12       0  4972.6     .07       0
  5001.8     .05       0  5027.1     .07       0    5541    .035       0
  5660.8     .07       0
Bank Sta=5001.8,5027.1
XS Rating Curve= 0 ,0
Exp/Cntr=0.3,0.1

Type RM Length L Ch R = 1 ,20185   ,556,556,556
BEGIN DESCRIPTION:
SIMMONS CREEK 34.0
END DESCRIPTION:
XS GIS Cut Line= 3
      2131625.04     13890825.01        2130975.       13890625.
      2130224.99       13890375.
#Sta/Elev= 30
  4320.3 1225.86  4402.1 1224.38  4519.1 1219.33  4602.8 1218.52  4717.9 1214.21
    4833 1211.92  4913.4  1205.6  4927.2 1206.78  4958.6 1203.75  4978.8 1205.83
  4984.1 1205.52    4990 1204.44  4997.8 1201.38  4998.1  1199.8  4998.6  1199.3
  5023.9  1199.8    5032 1203.77  5053.1 1207.73  5079.5 1208.28  5095.3 1209.82
  5200.7    1213  5232.3 1212.37  5327.2 1215.77  5358.8 1215.14  5464.2  1217.9
  5516.9 1219.68  5527.5 1221.21    5675  1224.8  5717.2 1228.09    5791 1230.63
#Mann= 3 ,-1 , 0
  4320.3     .12       0  4998.1     .05       0  5023.9     .07       0
Bank Sta=4998.1,5023.9
XS Rating Curve= 0 ,0
Exp/Cntr=0.3,0.1

Type RM Length L Ch R = 1 ,19629   ,549,549,549
BEGIN DESCRIPTION:
SIMMONS CREEK 33.0
END DESCRIPTION:
XS GIS Cut Line= 3
        2131725.       13890525.        2131125.       13890125.
        2130425.       13890075.
#Sta/Elev= 30
  4283.1 1224.77  4305.6 1224.69  4332.7  1221.5  4377.7 1218.89  4434.8 1217.38
    4558 1215.85  4594.1 1214.05  4794.9 1211.55  4844.2 1210.91  4867.5 1210.95
  4924.6 1206.73  4945.6 1203.45  4954.6 1198.38  4983.8  1197.4  4984.3  1196.9
  5009.7  1197.4  5014.2 1203.55  5024.3 1205.56  5054.3 1205.07  5076.9 1202.69
  5084.4 1202.83  5094.4  1204.3  5164.6 1207.75  5194.7 1208.01  5254.9 1211.15
  5344.2 1213.62  5465.4 1216.09  5515.5 1218.61  5605.7 1221.01    5706  1225.8
#Mann= 6 ,-1 , 0
  4283.1     .12       0  4794.9     .07       0  4844.2     .12       0
  4983.8     .05       0  5009.7     .12       0  5344.2     .07       0
Bank Sta=4983.8,5009.7
XS Rating Curve= 0 ,0
Exp/Cntr=0.3,0.1

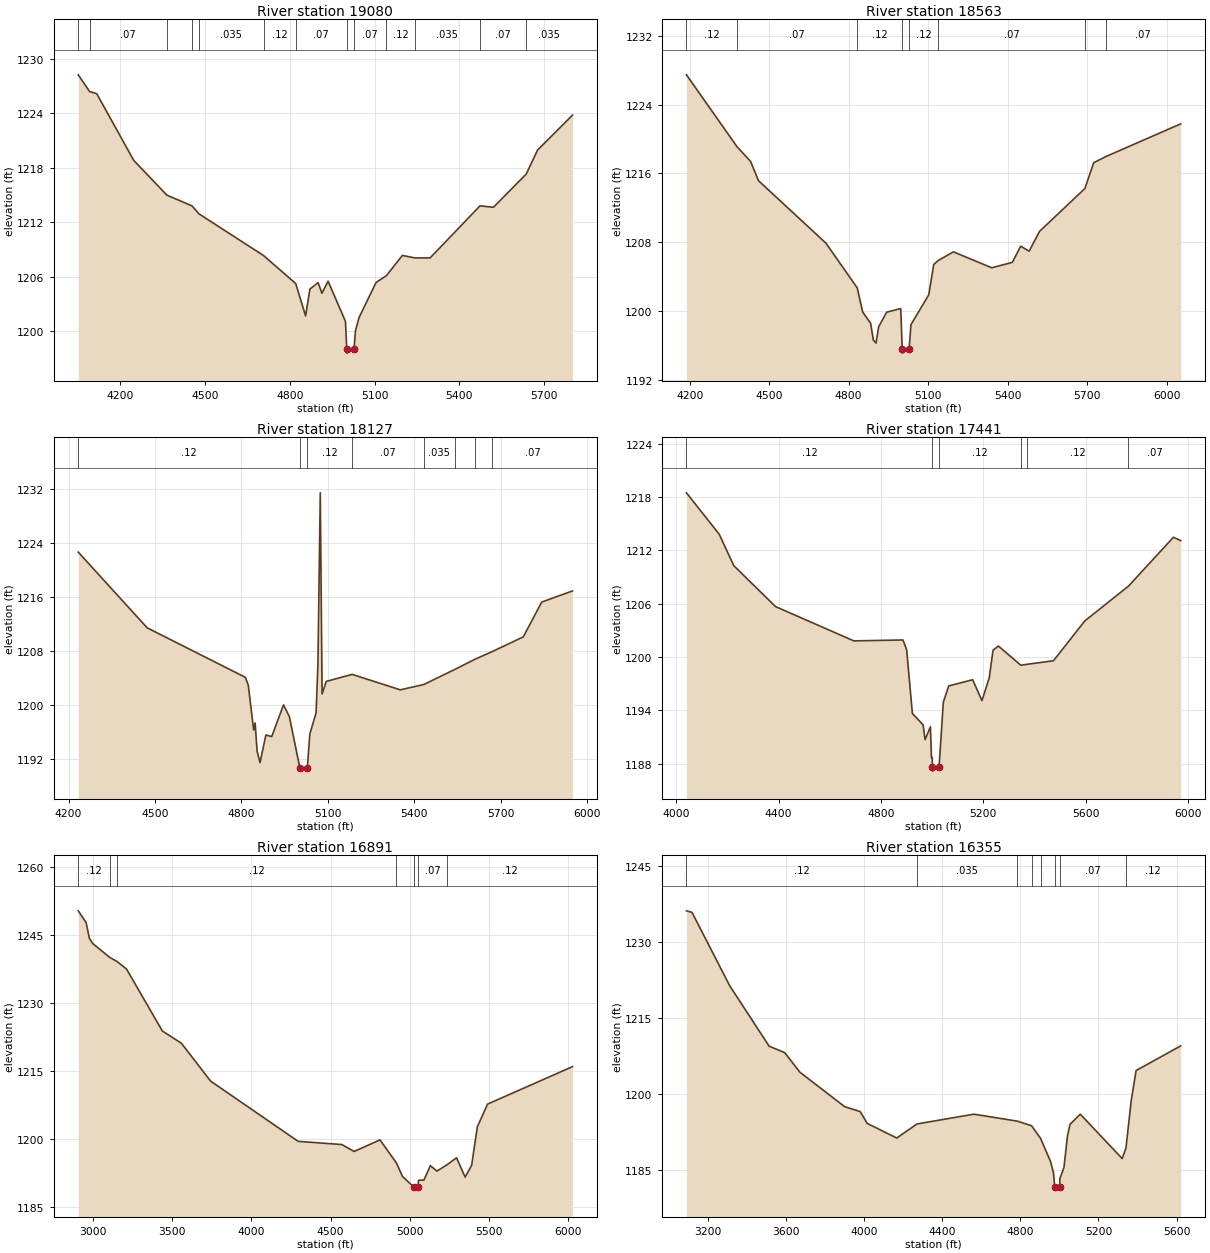
Type RM Length L Ch R = 1 ,19080   ,517,517,517
BEGIN DESCRIPTION:
SIMMONS CREEK 32.0
END DESCRIPTION:
XS GIS Cut Line= 3
      2132074.96     13890124.97        2131275.       13889625.
      2130474.97       13889725.
#Sta/Elev= 30
  4051.2 1228.21  4091.5 1226.37  4116.6 1226.14  4247.5 1218.81  4364.8 1214.99
  4453.7 1213.81  4478.9 1212.92    4707 1208.35    4821 1205.27    4856 1201.71
  4871.3 1204.66  4900.2 1205.37  4913.8  1204.2  4935.6 1205.53  4997.1 1201.11
  5001.7 1198.12  5002.2 1197.62  5027.7 1198.12  5032.3 1200.03  5044.9 1201.51
  5105.4 1205.38  5141.9 1206.13  5198.6 1208.36  5241.6 1208.09  5296.9 1208.09
  5473.5 1213.81  5521.1 1213.65  5637.2 1217.31  5677.3 1219.95  5800.8 1223.78
#Mann= 13 ,-1 , 0
  4051.2     .12       0  4091.5     .07       0  4364.8    .035       0
  4453.7     .12       0  4478.9    .035       0    4707     .12       0
    4821     .07       0  5001.7     .05       0  5027.7     .07       0
  5141.9     .12       0  5241.6    .035       0  5473.5     .07       0
  5637.2    .035       0
Bank Sta=5001.7,5027.7
XS Rating Curve= 0 ,0
Exp/Cntr=0.3,0.1

Type RM Length L Ch R = 1 ,18563   ,436,436,436
BEGIN DESCRIPTION:
SIMMONS CREEK 31.0
END DESCRIPTION:
XS GIS Cut Line= 3
        2132275.       13889275.        2131475.       13889175.
      2130475.01       13889525.
#Sta/Elev= 30
  4187.9 1227.46  4378.9  1219.1  4429.8  1217.4    4460 1215.15  4714.5 1207.89
  4832.6 1202.69    4853  1199.9  4883.3 1198.56  4893.3 1196.63  4903.4 1196.28
  4913.5 1198.18  4943.7 1199.87  4996.8 1200.29  5002.3 1195.61  5002.8 1195.11
  5028.4 1195.61  5035.4 1198.42  5102.7  1201.9  5121.3 1205.41  5138.5 1205.88
  5195.8 1206.88  5340.3 1205.03  5417.9 1205.66  5449.7 1207.54  5481.5 1206.96
  5521.2 1209.28  5691.8 1214.24  5725.2 1217.24  5770.5 1217.95  6053.6 1221.76
#Mann= 8 ,-1 , 0
  4187.9     .12       0  4378.9     .07       0  4832.6     .12       0
  5002.3     .05       0  5028.4     .12       0  5138.5     .07       0
  5691.8    .035       0  5770.5     .07       0
Bank Sta=5002.3,5028.4
XS Rating Curve= 0 ,0
Exp/Cntr=0.3,0.1

Type RM Length L Ch R = 1 ,18127   ,686,686,686
BEGIN DESCRIPTION:
SIMMONS CREEK 30.0
END DESCRIPTION:
XS GIS Cut Line= 3
      2132225.05     13888875.01      2131485.14     13888733.58
      2130725.02     13889324.99
#Sta/Elev= 30
  4233.5  1222.6    4473 1211.38  4813.9 1204.05  4824.1 1202.86  4842.7 1196.25
  4847.8 1197.29  4854.6 1193.11  4864.8 1191.42  4885.1 1195.51  4905.5 1195.28
  4946.2 1199.96  4966.6 1198.25    5003 1190.66  5003.5 1190.16  5029.1 1190.66
  5037.7 1195.65  5059.5  1198.8  5065.9 1206.03    5074 1231.38  5080.3 1201.59
  5094.8 1203.45  5184.8 1204.49  5351.8  1202.2  5433.7 1202.99  5541.1 1205.22
  5611.7 1206.74  5671.5 1207.87  5778.9 1210.04  5843.1  1215.2  5949.9 1216.85
#Mann= 8 ,-1 , 0
  4233.5     .12       0    5003     .05       0  5029.1     .12       0
  5184.8     .07       0  5433.7    .035       0  5541.1     .07       0
  5611.7    .035       0  5671.5     .07       0
Bank Sta=5003,5029.1
XS Rating Curve= 0 ,0
Exp/Cntr=0.3,0.1

Type RM Length L Ch R = 1 ,17441   ,550,550,550
BEGIN DESCRIPTION:
SIMMONS CREEK 29.0
END DESCRIPTION:
XS GIS Cut Line= 3
      2132225.02     13888725.02        2131475.       13888125.
      2130675.02     13888674.99
#Sta/Elev= 30
  4039.9 1218.46    4168  1213.8  4224.8 1210.27  4388.1 1205.66  4693.8 1201.81
  4885.9 1201.91  4900.3 1200.82  4922.8 1193.64  4964.4 1192.37  4972.4  1190.7
  4993.2 1192.15  4997.2 1188.69  5000.4 1188.69  5000.8 1187.66  5001.3 1187.16
    5027 1187.66  5043.7 1194.92  5064.7 1196.74  5158.2 1197.44  5194.6 1195.09
    5223 1197.64  5237.9 1200.76  5258.8 1201.23  5346.6 1199.07    5372 1199.18
  5473.9 1199.57  5596.4 1204.05  5767.2 1207.97  5942.8 1213.46  5971.2 1213.09
#Mann= 6 ,-1 , 0
  4039.9     .12       0  5000.8     .05       0    5027     .12       0
  5346.6     .07       0    5372     .12       0  5767.2     .07       0
Bank Sta=5000.8,5027
XS Rating Curve= 0 ,0
Exp/Cntr=0.3,0.1

Type RM Length L Ch R = 1 ,16891   ,536,536,536
BEGIN DESCRIPTION:
SIMMONS CREEK 28.0
END DESCRIPTION:
XS GIS Cut Line= 3
      2132974.97     13889024.97        2131425.       13887625.
      2130424.99       13887375.
#Sta/Elev= 30
  2907.2 1250.29  2956.8 1247.69  2977.8 1244.21  2999.4 1243.06  3106.3 1240.02
  3150.4 1239.16  3211.7 1237.48  3438.1 1223.81  3558.4 1221.11  3742.6 1212.77
  4295.1  1199.5    4571 1198.79  4648.7 1197.27  4811.6 1199.82  4915.6 1194.72
  4953.6 1191.76  5023.9 1189.47  5024.4 1188.97  5050.1 1189.47  5055.1 1190.92
  5088.6 1190.95  5129.8 1194.15    5171 1192.94  5235.7 1194.36  5294.7 1195.87
  5348.9 1191.62  5390.1 1194.21  5426.2 1202.71  5490.6  1207.7  6026.6 1215.96
#Mann= 7 ,-1 , 0
  2907.2     .12       0  3106.3     .07       0  3150.4     .12       0
  4915.6     .07       0  5023.9     .05       0  5050.1     .07       0
  5235.7     .12       0
Bank Sta=5023.9,5050.1
XS Rating Curve= 0 ,0
Exp/Cntr=0.3,0.1

Type RM Length L Ch R = 1 ,16355   ,540,540,540
BEGIN DESCRIPTION:
SIMMONS CREEK 27.0
END DESCRIPTION:
XS GIS Cut Line= 3
      2133074.98     13888274.99        2131525.       13887175.
      2130922.64       13886994.
#Sta/Elev= 30
  3091.2 1236.15  3119.5 1235.85  3312.6 1221.35  3514.4 1209.42  3593.9 1208.15
  3671.8 1204.28  3900.6 1197.48  3980.6  1196.5  4016.3 1194.17  4167.6 1191.28
  4271.1 1194.06  4562.5 1195.99  4785.3 1194.61  4857.7  1193.7  4903.6 1191.21
    4955 1186.61  4969.7  1184.4  4975.7 1181.69  4976.2 1181.19  5001.9 1181.69
  5002.3 1183.25  5023.2 1185.46  5041.4 1191.72  5054.5    1194  5106.7 1195.99
  5321.3 1187.23  5340.7 1189.33  5367.7 1198.73  5392.6 1204.61  5620.8 1209.48
#Mann= 8 ,-1 , 0
  3091.2     .12       0  4271.1    .035       0  4785.3     .07       0
  4857.7    .035       0  4903.6     .07       0  4975.7     .05       0
  5001.9     .07       0  5340.7     .12       0
Bank Sta=4975.7,5001.9
XS Rating Curve= 0 ,0
Exp/Cntr=0.3,0.1

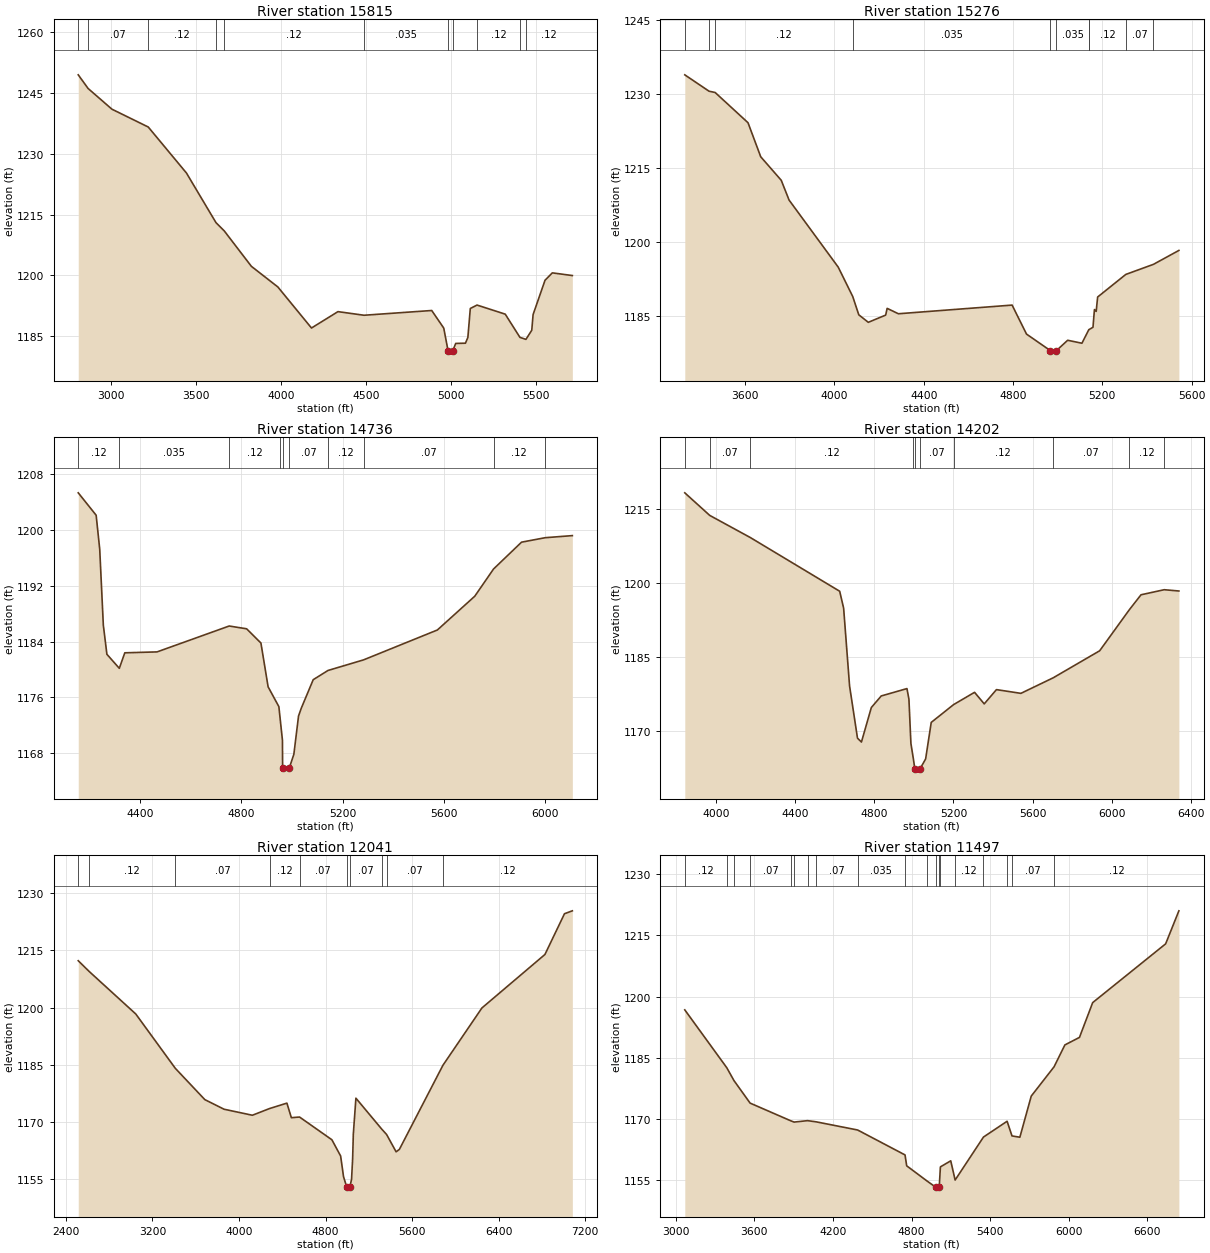
Type RM Length L Ch R = 1 ,15815   ,1083,1083,1083
BEGIN DESCRIPTION:
SIMMONS CREEK 26.0
END DESCRIPTION:
XS GIS Cut Line= 3
      2133475.02     13888425.02        2131925.       13886875.
      2131464.54     13886329.52
#Sta/Elev= 30
  2808.2 1249.47  2866.1 1246.11  3006.2    1241    3220  1236.6  3444.6 1225.26
  3618.2 1213.03  3667.2 1210.97  3826.5 1202.25    3982 1197.17    4180 1187.04
  4335.6 1191.08    4489 1190.19  4887.1 1191.36  4957.8 1187.03  4983.6 1181.35
  4984.1 1180.85  5009.8 1181.35  5028.2 1183.24  5085.4  1183.3  5099.7 1184.72
    5114 1191.86  5153.7  1192.7  5319.5 1190.46    5406 1184.73  5441.2 1184.24
  5475.5 1186.49  5483.3 1190.36  5553.5 1198.82  5596.4 1200.64  5714.1 1199.98
#Mann= 11 ,-1 , 0
  2808.2     .12       0  2866.1     .07       0    3220     .12       0
  3618.2     .07       0  3667.2     .12       0    4489    .035       0
  4983.6    .035       0  5009.8    .035       0  5153.7     .12       0
    5406     .07       0  5441.2     .12       0
Bank Sta=4983.6,5009.8
XS Rating Curve= 0 ,0
Exp/Cntr=0.3,0.1

Type RM Length L Ch R = 1 ,15276   ,540,540,540
BEGIN DESCRIPTION:
SIMMONS CREEK 25.0
END DESCRIPTION:
XS GIS Cut Line= 3
      2133424.97     13887824.96        2132325.       13886575.
      2131901.37      13886226.8
#Sta/Elev= 30
  3329.6 1233.85  3438.2 1230.54  3465.5 1230.28  3612.8 1224.17  3669.7 1217.29
  3761.7 1212.53  3796.8 1208.53  4016.9 1194.98  4081.9 1189.04    4109 1185.34
  4151.6 1183.82  4229.5 1185.28  4236.1 1186.64  4286.4 1185.55  4795.9  1187.3
  4860.4 1181.44  4967.5 1178.09    4968 1177.59  4994.2 1178.09  5044.8 1180.19
  5108.7 1179.59  5139.7 1182.35  5141.2 1182.37  5158.2 1182.82  5164.7  1186.4
  5172.6 1186.03    5179 1188.93  5305.2  1193.5  5429.2 1195.54    5543 1198.35
#Mann= 10 ,-1 , 0
  3329.6     .12       0  3438.2     .07       0  3465.5     .12       0
  4081.9    .035       0  4967.5    .035       0  4994.2    .035       0
  5139.7     .07       0  5141.2     .12       0  5305.2     .07       0
  5429.2     .12       0
Bank Sta=4967.5,4994.2
XS Rating Curve= 0 ,0
Exp/Cntr=0.3,0.1

Type RM Length L Ch R = 1 ,14736   ,534,534,534
BEGIN DESCRIPTION:
SIMMONS CREEK 24.0
END DESCRIPTION:
XS GIS Cut Line= 3
        2133375.       13886925.        2132775.       13886325.
      2131729.55      13885976.6
#Sta/Elev= 30
  4156.3 1205.31    4227  1202.1  4241.1 1197.23  4255.3 1186.37  4269.4 1182.18
  4318.4 1180.17  4340.1 1182.39  4467.4 1182.52  4752.2 1186.23    4821 1185.83
  4877.5 1183.79  4905.8 1177.52  4948.3 1174.68  4952.6 1173.21  4962.4 1169.87
  4963.1 1165.94  4963.6 1165.44  4989.9 1165.94  5007.5 1167.86  5025.9 1173.33
  5036.4 1174.42  5083.9 1178.54  5142.2 1179.86  5282.8 1181.38    5574 1185.66
  5721.7  1190.5  5795.8  1194.4  5906.2 1198.24  5999.6 1198.88  6106.8 1199.18
#Mann= 10 ,-1 , 0
  4156.3     .12       0  4318.4    .035       0  4752.2     .12       0
  4952.6     .07       0  4963.1     .05       0  4989.9     .07       0
  5142.2     .12       0  5282.8     .07       0  5795.8     .12       0
  5999.6    .035       0
Bank Sta=4963.1,4989.9
XS Rating Curve= 0 ,0
Exp/Cntr=0.3,0.1

Type RM Length L Ch R = 1 ,14202   ,2161,2161,2161
BEGIN DESCRIPTION:
SIMMONS CREEK 23.0
END DESCRIPTION:
XS GIS Cut Line= 4
      2134227.79     13885883.68        2133075.       13885925.
      2132508.87     13886066.45      2131760.57     13885924.58
#Sta/Elev= 30
  3841.2 1218.37  3967.3 1213.78  4172.8 1209.27  4624.5 1198.35  4644.5 1194.91
  4674.5  1179.1  4714.6 1168.46  4734.6 1167.68  4784.6  1174.7  4834.6 1177.05
  4964.7 1178.55  4974.7  1176.4  4984.7 1167.41  4996.9 1164.32  5004.5 1162.26
    5005 1161.76  5031.3 1162.26  5059.2 1164.24  5087.5 1171.67  5200.5 1175.29
  5306.6 1177.79  5355.5 1175.44  5417.3 1178.34    5541 1177.58  5703.7 1180.73
  5939.3 1186.24  6089.2 1194.58  6148.4 1197.63  6265.7 1198.66  6339.9  1198.4
#Mann= 10 ,-1 , 0
  3841.2     .12       0  3967.3     .07       0  4172.8     .12       0
  4996.9     .07       0  5004.5     .05       0  5031.3     .07       0
  5200.5     .12       0  5703.7     .07       0  6089.2     .12       0
  6265.7    .035       0
Bank Sta=5004.5,5031.3
XS Rating Curve= 0 ,0
Exp/Cntr=0.3,0.1

Type RM Length L Ch R = 1 ,12041   ,544,544,544
BEGIN DESCRIPTION:
SIMMONS CREEK 22.0
END DESCRIPTION:
XS GIS Cut Line= 3
      2134130.57      13885057.3        2131675.       13884675.
      2129602.78     13884494.79
#Sta/Elev= 30
  2515.2 1212.27  2617.9 1209.41  3047.1 1198.29    3412 1184.05  3684.7 1175.84
  3862.3 1173.32  4123.9 1171.74  4282.4 1173.49  4443.2 1174.92  4484.2  1171.1
  4560.1 1171.27  4858.7 1165.31  4939.6 1161.05  4966.4 1155.61  4996.5 1152.86
    4997 1152.36  5024.2 1152.86  5040.5 1154.95  5050.5 1160.37  5056.8 1166.79
  5080.7 1176.22  5321.4 1168.03  5363.9 1166.71  5452.1 1162.15  5482.2 1162.78
  5884.8 1184.85    6245 1199.88  6827.2 1213.91  7007.9  1224.6  7080.4 1225.36
#Mann= 10 ,-1 , 0
  2515.2    .035       0  2617.9     .12       0    3412     .07       0
  4282.4     .12       0  4560.1     .07       0  4996.5     .05       0
  5024.2     .07       0  5321.4    .035       0  5363.9     .07       0
  5884.8     .12       0
Bank Sta=4996.5,5024.2
XS Rating Curve= 0 ,0
Exp/Cntr=0.3,0.1

Type RM Length L Ch R = 1 ,11497   ,547,547,547
BEGIN DESCRIPTION:
SIMMONS CREEK 21.0
END DESCRIPTION:
XS GIS Cut Line= 3
      2133456.94     13884786.46        2131625.       13884175.
      2129804.17     13883904.52
#Sta/Elev= 30
  3068.7 1196.77  3389.1  1182.6  3444.2 1179.44  3567.4 1173.92  3877.4 1169.59
  3903.3 1169.27  4006.2 1169.62  4073.3 1169.32  4388.3 1167.33  4750.1 1161.22
  4762.9 1158.55    4921 1154.76  4983.5 1153.34    4984 1152.84  5011.2 1153.34
    5015 1155.43  5020.2 1158.29  5099.1 1159.78  5132.6 1155.07    5349  1165.6
  5529.3 1169.47  5566.6 1165.88  5626.8 1165.56  5713.7 1175.64    5888 1182.82
  5970.5 1188.18  6081.7 1190.02  6182.8 1198.55  6739.7 1212.95  6840.8 1221.04
#Mann= 19 ,-1 , 0
  3068.7     .12       0  3389.1     .07       0  3444.2     .12       0
  3567.4     .07       0  3877.4    .035       0  3903.3     .07       0
  4006.2    .035       0  4073.3     .07       0  4388.3    .035       0
  4750.1     .12       0    4921    .035       0  4983.5    .035       0
  5011.2    .035       0    5015     .07       0  5132.6     .12       0
    5349     .07       0  5529.3     .12       0  5566.6     .07       0
    5888     .12       0
Bank Sta=4983.5,5011.2
XS Rating Curve= 0 ,0
Exp/Cntr=0.3,0.1

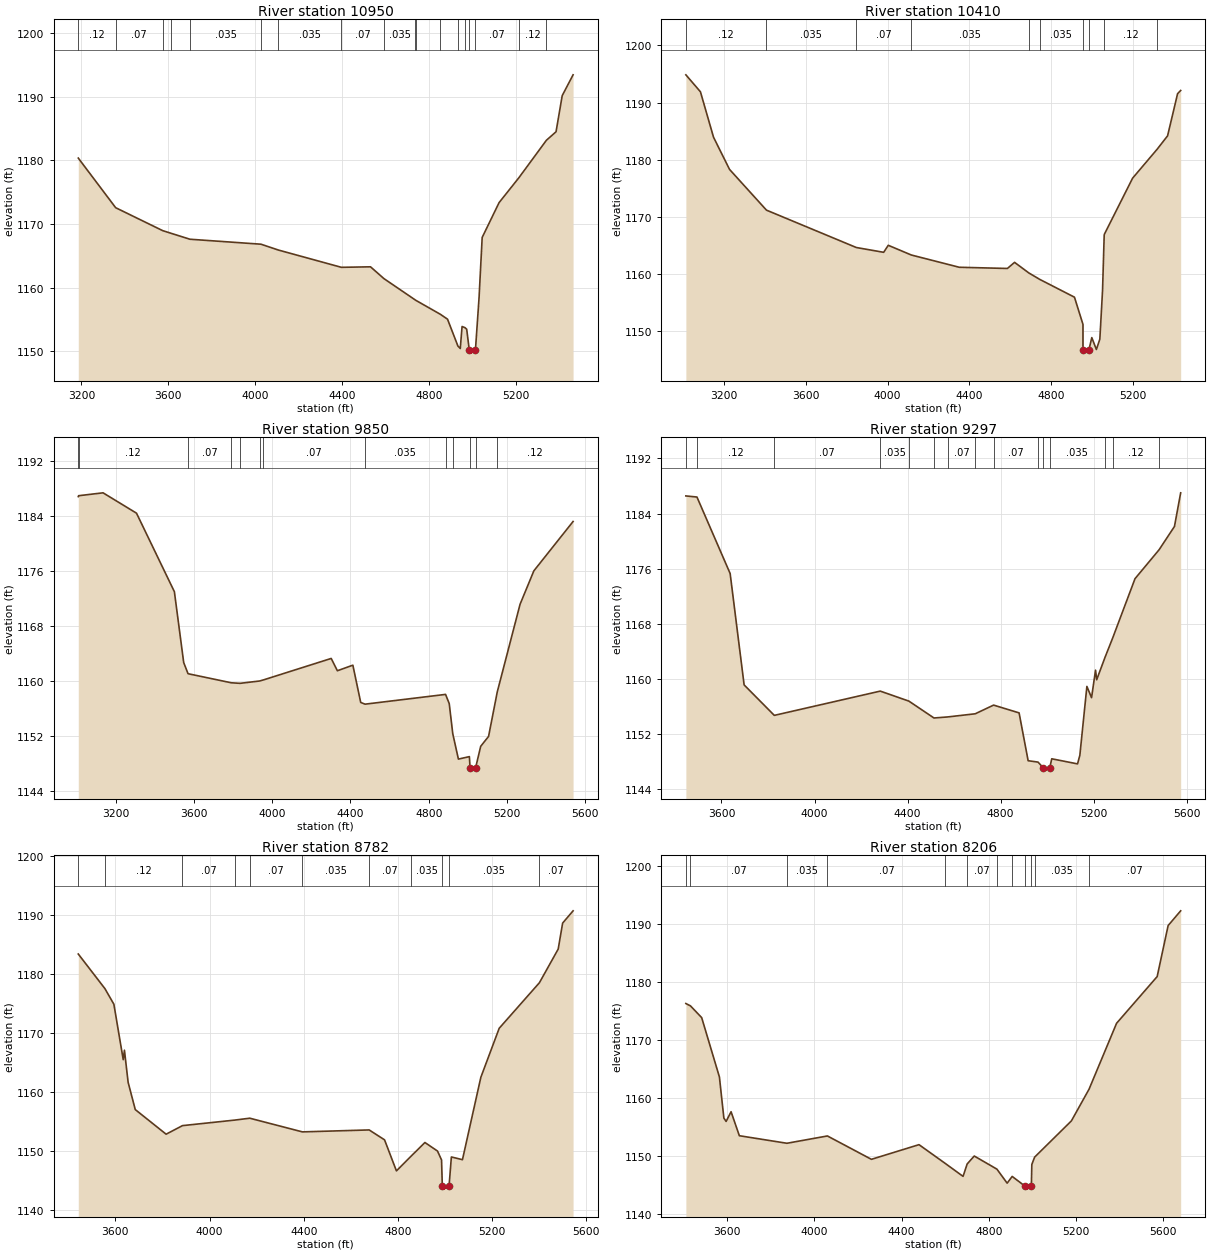
Type RM Length L Ch R = 1 ,10950   ,540,540,540
BEGIN DESCRIPTION:
SIMMONS CREEK 20.0
END DESCRIPTION:
XS GIS Cut Line= 3
      2133125.04     13884625.02        2131575.       13883675.
      2131224.99     13883374.99
#Sta/Elev= 30
  3185.8 1180.36    3358 1172.57  3574.5 1168.97  3613.4 1168.55    3700 1167.62
  4027.2 1166.84  4107.8 1165.92  4397.7 1163.21  4531.9 1163.29  4593.5 1161.44
  4738.3 1158.08  4739.9 1158.04  4853.4 1155.84  4886.5 1155.07  4934.4 1150.85
  4945.2 1150.47  4953.5 1153.92  4966.8 1153.74  4974.8 1153.49  4986.7 1150.24
  4987.2 1149.74  5015.1 1150.24  5031.8 1158.48  5046.1  1167.9    5124 1173.37
  5215.5 1177.29    5342 1183.16  5386.3 1184.49  5414.8 1190.17  5464.8 1193.43
#Mann= 18 ,-1 , 0
  3185.8     .12       0    3358     .07       0  3574.5    .035       0
  3613.4     .07       0    3700    .035       0  4027.2     .07       0
  4107.8    .035       0  4397.7     .07       0  4593.5    .035       0
  4738.3     .07       0  4739.9    .035       0  4853.4     .07       0
  4934.4    .035       0  4966.8     .07       0  4986.7     .05       0
  5015.1     .07       0  5215.5     .12       0    5342     .07       0
Bank Sta=4986.7,5015.1
XS Rating Curve= 0 ,0
Exp/Cntr=0.3,0.1

Type RM Length L Ch R = 1 ,10410   ,560,560,560
BEGIN DESCRIPTION:
SIMMONS CREEK 19.0
END DESCRIPTION:
XS GIS Cut Line= 3
        2133375.       13884475.        2131825.       13883225.
      2131425.03     13883075.01
#Sta/Elev= 30
  3013.9 1194.85  3085.1 1191.88  3149.1 1183.92  3227.4 1178.28  3407.7 1171.15
  3846.9  1164.6  3980.7 1163.76  4003.1 1164.99  4115.7 1163.29  4350.2 1161.14
  4585.3 1160.93  4620.5    1162  4689.6 1160.16  4742.8 1159.03  4913.2  1155.9
  4954.8 1151.13  4954.9  1146.6  4955.4  1146.1  4983.4  1146.6  4997.9 1148.82
  5020.3 1146.74  5037.2 1148.54  5050.5 1157.11  5058.5 1166.77  5059.8 1166.95
  5197.4 1176.75  5317.1 1181.81  5368.3 1184.16  5417.2 1191.55  5432.3 1192.11
#Mann= 10 ,-1 , 0
  3013.9     .12       0  3407.7    .035       0  3846.9     .07       0
  4115.7    .035       0  4689.6     .07       0  4742.8    .035       0
  4954.9    .035       0  4983.4    .035       0  5059.8     .12       0
  5317.1     .07       0
Bank Sta=4954.9,4983.4
XS Rating Curve= 0 ,0
Exp/Cntr=0.3,0.1

Type RM Length L Ch R = 1 ,9850    ,553,553,553
BEGIN DESCRIPTION:
SIMMONS CREEK 18.0
END DESCRIPTION:
XS GIS Cut Line= 3
      2134061.05     13882967.01        2132075.       13882775.
      2131545.67     13882719.85
#Sta/Elev= 30
  3009.7 1186.86  3011.4 1186.99  3136.3 1187.41  3307.1 1184.45  3500.6 1173.03
  3548.2 1162.72  3570.4  1161.1  3791.2 1159.78    3836  1159.7  3935.8 1160.04
  3955.8  1160.2  4301.7 1163.32  4333.2 1161.53  4412.3 1162.34  4452.4 1156.92
  4474.7 1156.67  4885.8 1158.09  4904.5 1156.76  4922.6 1152.38  4951.4 1148.68
  5007.5 1149.04  5010.9 1147.43  5011.4 1146.93  5039.4 1147.43  5065.3 1150.54
  5105.5 1151.98    5150 1158.46  5266.4  1171.2  5336.8 1176.06  5537.2 1183.24
#Mann= 13 ,-1 , 0
  3009.7     .07       0  3011.4     .12       0  3570.4     .07       0
  3791.2    .035       0    3836     .07       0  3935.8    .035       0
  3955.8     .07       0  4474.7    .035       0  4885.8     .12       0
  4922.6    .035       0  5010.9    .035       0  5039.4    .035       0
    5150     .12       0
Bank Sta=5010.9,5039.4
XS Rating Curve= 0 ,0
Exp/Cntr=0.3,0.1

Type RM Length L Ch R = 1 ,9297    ,515,515,515
BEGIN DESCRIPTION:
SIMMONS CREEK 17.0
END DESCRIPTION:
XS GIS Cut Line= 3
      2133674.96       13882225.        2132125.       13882325.
      2131554.56      13882393.3
#Sta/Elev= 30
  3446.8 1186.55  3494.5 1186.39  3637.2 1175.29  3697.3 1159.13  3827.1 1154.71
  4282.7 1158.23  4405.7 1156.78  4513.7 1154.33  4571.9 1154.48  4691.1 1154.94
  4770.1  1156.2  4879.7 1155.07  4918.6 1148.13  4961.1 1147.93  4983.2 1147.12
  4983.7 1146.62  5011.7 1147.12  5020.1 1148.41  5131.1 1147.67    5141 1148.93
  5171.2 1158.91  5191.3 1157.28  5208.4 1161.27  5213.4 1159.88  5248.5 1163.07
  5282.5 1165.97  5378.1 1174.54  5481.7 1178.74  5547.8 1182.12  5574.5    1187
#Mann= 15 ,-1 , 0
  3446.8     .07       0  3494.5     .12       0  3827.1     .07       0
  4282.7    .035       0  4405.7     .07       0  4513.7    .035       0
  4571.9     .07       0  4691.1    .035       0  4770.1     .07       0
  4961.1    .035       0  4983.2    .035       0  5011.7    .035       0
  5248.5     .07       0  5282.5     .12       0  5481.7     .07       0
Bank Sta=4983.2,5011.7
XS Rating Curve= 0 ,0
Exp/Cntr=0.3,0.1

Type RM Length L Ch R = 1 ,8782    ,576,576,576
BEGIN DESCRIPTION:
SIMMONS CREEK 16.0
END DESCRIPTION:
XS GIS Cut Line= 3
      2133574.97       13882075.        2132025.       13881875.
      2131525.03     13882074.99
#Sta/Elev= 30
  3442.6 1183.35  3555.5  1177.5  3593.8 1174.84  3633.5 1165.45  3638.6 1167.05
  3654.3 1161.61  3684.6 1156.99  3815.6 1152.82  3885.1 1154.27  4107.6 1155.21
  4170.7 1155.53  4394.4 1153.21  4677.9 1153.54  4743.3 1151.86  4793.7  1146.6
  4857.1 1149.14  4914.7 1151.41  4968.2 1149.96  4985.3 1148.45  4988.6 1144.01
  4989.1 1143.51  5017.2 1144.01    5027 1148.96  5074.1  1148.5  5152.2 1162.46
  5230.2 1170.77    5401 1178.49  5480.7 1184.19  5499.5 1188.59  5543.9 1190.67
#Mann= 11 ,-1 , 0
  3442.6     .07       0  3555.5     .12       0  3885.1     .07       0
  4107.6    .035       0  4170.7     .07       0  4394.4    .035       0
  4677.9     .07       0  4857.1    .035       0  4988.6    .035       0
  5017.2    .035       0    5401     .07       0
Bank Sta=4988.6,5017.2
XS Rating Curve= 0 ,0
Exp/Cntr=0.3,0.1

Type RM Length L Ch R = 1 ,8206    ,365,365,365
BEGIN DESCRIPTION:
SIMMONS CREEK 15.0
END DESCRIPTION:
XS GIS Cut Line= 3
      2133425.03     13881775.01        2131875.       13881425.
      2131325.02     13881824.98
#Sta/Elev= 30
  3410.4 1176.23  3431.4 1175.83  3482.9  1173.8  3564.2 1163.57  3584.7 1156.47
    3595  1155.9  3617.7 1157.57  3655.7 1153.43  3873.8 1152.13  4059.5 1153.39
  4261.3 1149.36  4479.5 1151.89    4600 1148.65  4681.6 1146.42  4700.4 1148.56
  4732.9 1149.93  4836.7 1147.67  4883.8 1145.25  4906.8 1146.41  4966.1 1144.72
  4966.6 1144.22  4994.7 1144.72  4996.9 1148.47  5009.8 1149.74  5178.4 1155.99
  5259.4 1161.46  5385.5 1172.82  5571.7 1180.88    5622 1189.68  5679.5 1192.22
#Mann= 12 ,-1 , 0
  3410.4     .12       0  3431.4     .07       0  3873.8    .035       0
  4059.5     .07       0    4600    .035       0  4700.4     .07       0
  4836.7    .035       0  4906.8     .07       0  4966.1     .05       0
  4994.7     .07       0  5009.8    .035       0  5259.4     .07       0
Bank Sta=4966.1,4994.7
XS Rating Curve= 0 ,0
Exp/Cntr=0.3,0.1

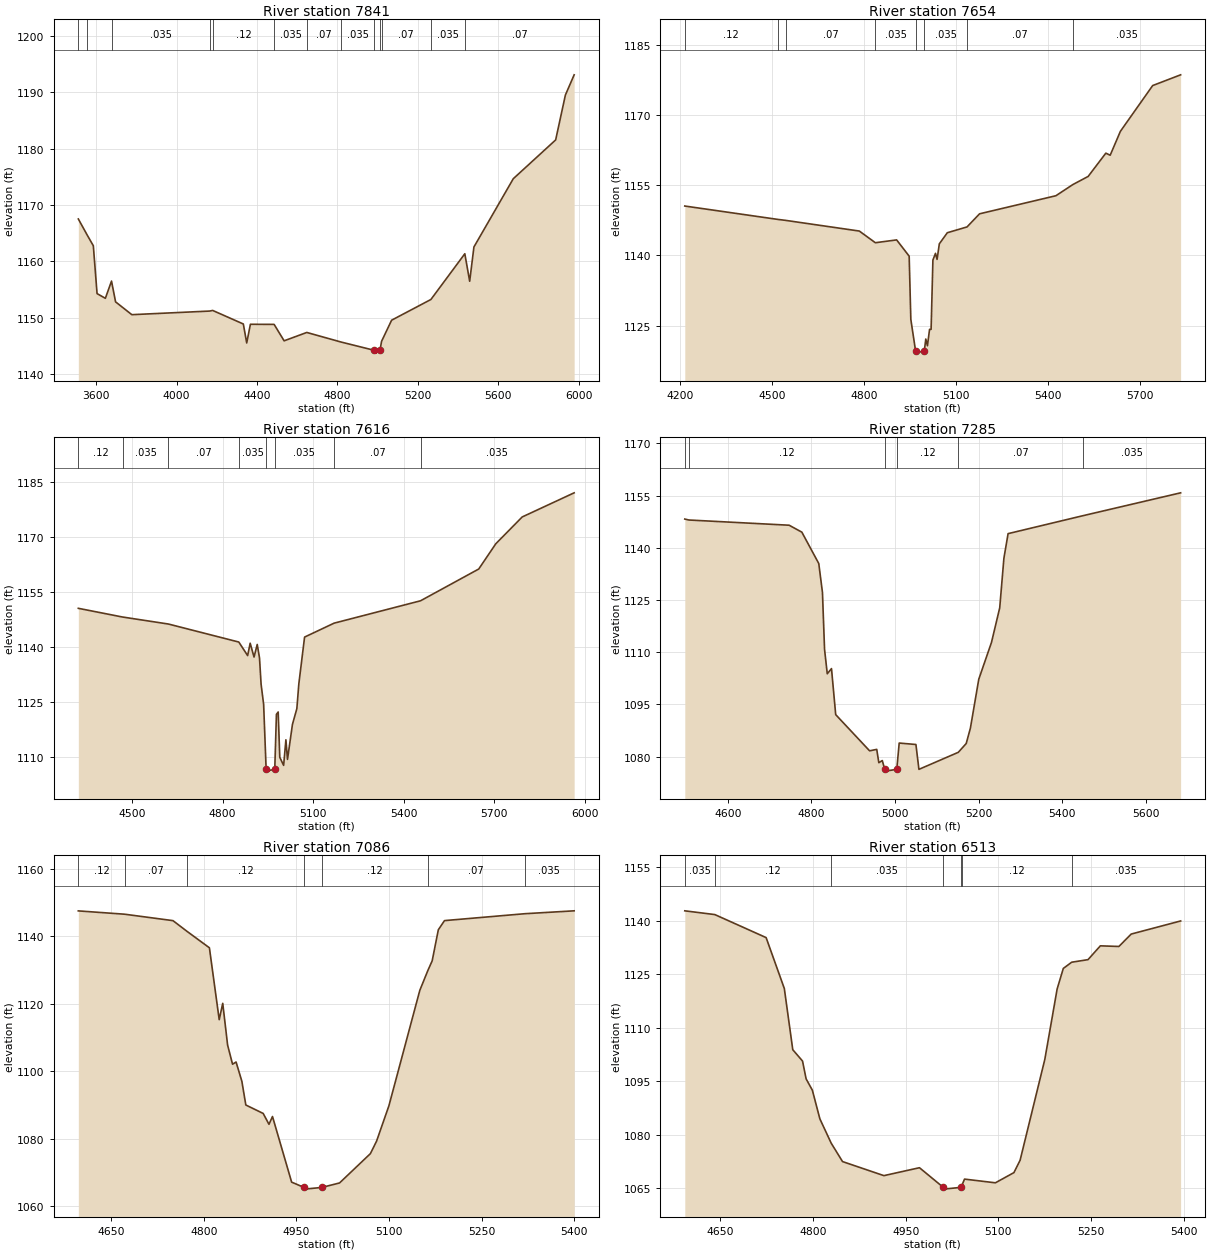
Type RM Length L Ch R = 1 ,7841    ,225,225,225
BEGIN DESCRIPTION:
SIMMONS CREEK 14.5
END DESCRIPTION:
XS GIS Cut Line= 3
      2133315.12     13881438.17      2131874.85     13881059.94
      2131058.58     13881597.53
#Sta/Elev= 30
  3510.9 1167.53  3556.5 1164.59  3585.5 1162.79  3604.1 1154.31  3645.4 1153.48
    3676 1156.53  3696.2 1152.85    3777 1150.58  4164.3 1151.22  4179.2 1151.33
  4331.7 1148.93  4348.5 1145.57  4366.9 1148.88  4484.9 1148.86  4534.6 1145.95
  4647.4 1147.43  4819.4 1145.72  4982.9 1144.27  4983.4 1143.77  5011.5 1144.27
  5019.4 1145.86  5069.3  1149.6  5264.8 1153.27  5433.5 1161.37  5457.7  1156.5
  5478.8 1162.57  5674.6 1174.66  5885.4 1181.53  5933.8 1189.48  5977.4 1193.06
#Mann= 13 ,-1 , 0
  3510.9    .035       0  3556.5     .07       0    3676    .035       0
  4164.3     .07       0  4179.2     .12       0  4484.9    .035       0
  4647.4     .07       0  4819.4    .035       0  4982.9    .035       0
  5011.5    .035       0  5019.4     .07       0  5264.8    .035       0
  5433.5     .07       0
Bank Sta=4982.9,5011.5
XS Rating Curve= 0 ,0
Exp/Cntr=0.3,0.1

Type RM Length L Ch R = 1 ,7654    ,38,38,38
BEGIN DESCRIPTION:
SIMMONS CREEK 14.2
END DESCRIPTION:
XS GIS Cut Line= 3
      2132676.65     13881189.41      2131930.71     13880894.98
      2131151.52     13880664.54
#Sta/Elev= 30
  4216.7 1150.54  4519.1 1147.69  4544.9 1147.48    4785  1145.2  4837.2 1142.71
  4906.5 1143.31  4947.3 1139.84  4952.7 1126.35  4968.1 1119.64  4968.6 1119.14
  4996.7 1119.64  5001.4 1122.15  5006.8 1120.72  5013.7 1124.21  5018.7 1124.21
  5024.6 1139.01    5033 1140.44  5038.2 1139.15  5045.5 1142.47  5071.5 1144.84
  5135.7 1146.08  5176.5 1148.88  5425.1 1152.74  5480.2 1155.12  5530.1 1156.86
  5587.7 1161.83  5601.9 1161.39  5635.1 1166.49  5740.2 1176.26  5831.2 1178.55
#Mann= 8 ,-1 , 0
  4216.7     .12       0  4519.1    .035       0  4544.9     .07       0
  4837.2    .035       0  4968.1    .035       0  4996.7    .035       0
  5135.7     .07       0  5480.2    .035       0
Bank Sta=4968.1,4996.7
XS Rating Curve= 0 ,0
Exp/Cntr=0.3,0.1

Type RM Length L Ch R = 1 ,7616    ,530,530,530
BEGIN DESCRIPTION:
SIMMONS CREEK 14.0
END DESCRIPTION:
XS GIS Cut Line= 3
      2132614.06      13881100.7        2131975.       13880875.
      2131064.54     13880553.81
#Sta/Elev= 30
  4322.2 1150.58  4468.8 1148.21  4620.9  1146.3    4854  1141.4  4883.3 1137.72
  4891.7 1141.08  4904.5 1137.32  4915.1 1140.74  4922.6  1137.1  4927.9 1129.92
  4936.3 1124.44  4944.6 1106.76  4945.1 1106.26  4973.2 1106.76  4978.7 1121.72
  4984.5 1122.36  4989.8 1110.03  5002.6 1107.83  5010.1 1114.79  5015.4 1109.46
  5031.8 1118.98  5046.4 1123.27    5053 1130.05    5072 1142.75  5169.8 1146.54
  5456.3 1152.63  5649.2 1161.28  5705.7 1168.15  5793.2 1175.45  5965.4 1182.02
#Mann= 8 ,-1 , 0
  4322.2     .12       0  4468.8    .035       0  4620.9     .07       0
    4854    .035       0  4944.6    .035       0  4973.2    .035       0
  5169.8     .07       0  5456.3    .035       0
Bank Sta=4944.6,4973.2
XS Rating Curve= 0 ,0
Exp/Cntr=0.3,0.1

Type RM Length L Ch R = 1 ,7285    ,199,199,199
BEGIN DESCRIPTION:
SIMMONS CREEK 13.5
END DESCRIPTION:
XS GIS Cut Line= 3
      2132621.48     13880702.01      2132126.03     13880623.63
      2131443.18     13880582.58
#Sta/Elev= 30
  4497.4 1148.26    4507 1147.99  4746.9 1146.49  4777.3  1144.5  4817.8 1135.48
  4826.6 1127.17  4831.6 1110.82  4838.1  1103.8  4848.2 1105.29  4858.3 1092.05
  4939.3 1081.66  4956.4 1082.07  4961.4 1078.24  4969.7 1078.86  4975.6 1076.32
  4976.1 1075.82  5004.3 1076.32  5010.1 1083.89  5050.1 1083.47  5057.3 1076.33
  5151.5 1081.23  5170.4 1083.76  5180.4 1088.18  5200.4 1102.23  5230.8 1112.81
  5250.5 1122.75  5260.5 1136.99  5270.5 1144.07  5449.3 1149.22  5683.1  1155.8
#Mann= 6 ,-1 , 0
  4497.4     .07       0    4507     .12       0  4975.6     .05       0
  5004.3     .12       0  5151.5     .07       0  5449.3    .035       0
Bank Sta=4975.6,5004.3
XS Rating Curve= 0 ,0
Exp/Cntr=0.3,0.1

Type RM Length L Ch R = 1 ,7086    ,573,573,573
BEGIN DESCRIPTION:
SIMMONS CREEK 13.0
END DESCRIPTION:
XS GIS Cut Line= 3
      2132474.97     13880624.98        2132125.       13880425.
      2131724.98       13880425.
#Sta/Elev= 30
  4596.9 1147.49  4671.7 1146.51  4750.2  1144.6  4772.9 1141.43  4809.2 1136.55
  4825.1 1115.24  4830.8 1120.09  4838.7  1107.7  4846.7 1102.03  4852.4 1102.69
  4861.8 1096.96  4868.2 1089.94  4896.3 1087.44  4905.7 1084.22  4911.4 1086.53
  4942.4 1067.07  4962.6  1065.5  4963.1    1065  4991.3  1065.5    5020 1066.83
    5070 1075.53    5080 1079.24    5100 1089.74    5150 1123.93  5163.1 1129.84
    5170 1132.66    5180 1141.89    5190 1144.61  5319.8 1146.65    5400 1147.51
#Mann= 7 ,-1 , 0
  4596.9     .12       0  4671.7     .07       0  4772.9     .12       0
  4962.6     .05       0  4991.3     .12       0  5163.1     .07       0
  5319.8    .035       0
Bank Sta=4962.6,4991.3
XS Rating Curve= 0 ,0
Exp/Cntr=0.3,0.1

Type RM Length L Ch R = 1 ,6513    ,507,507,507
BEGIN DESCRIPTION:
SIMMONS CREEK 12.0
END DESCRIPTION:
XS GIS Cut Line= 3
      2132524.99     13880274.98        2132325.       13879925.
      2131924.99       13879925.
#Sta/Elev= 30
  4592.2 1142.76  4640.8 1141.71  4723.9 1135.26  4753.4    1121  4767.1 1103.84
  4782.9 1100.66  4788.7 1095.67  4798.8  1092.5    4811 1084.46  4829.3 1077.66
  4847.7 1072.49  4914.7 1068.55  4972.3 1070.77  5010.9 1065.27  5011.4 1064.77
  5039.7 1065.27  5040.6 1065.64  5045.3 1067.58  5095.3 1066.54  5125.3  1069.4
  5135.3 1072.86  5175.3  1101.1  5195.3 1120.86  5205.3 1126.62  5218.9 1128.36
  5245.3 1129.08  5265.3 1132.95  5295.3 1132.77  5315.3 1136.25  5395.3 1139.92
#Mann= 7 ,-1 , 0
  4592.2    .035       0  4640.8     .12       0  4829.3    .035       0
  5010.9    .035       0  5039.7    .035       0  5040.6     .12       0
  5218.9    .035       0
Bank Sta=5010.9,5039.7
XS Rating Curve= 0 ,0
Exp/Cntr=0.3,0.1