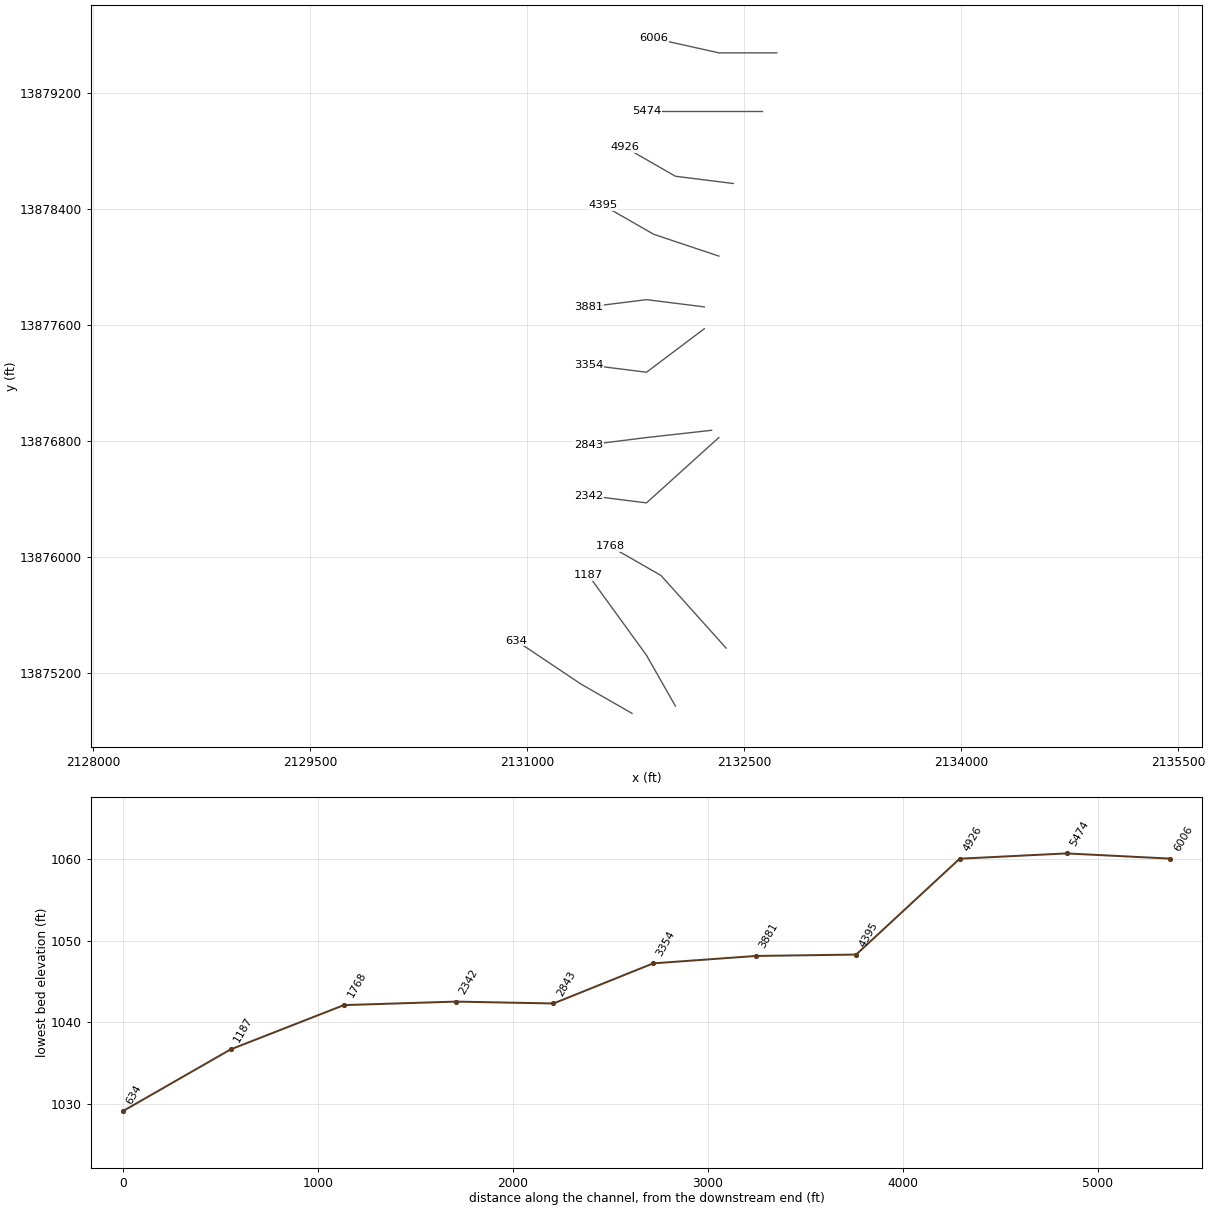
HEC-RAS study SIMMONS CREEK.prj: SIMMONS CREEK Base Level Engineering

--- SIMMONS CREEK.g01 (geometry) --- (continued)

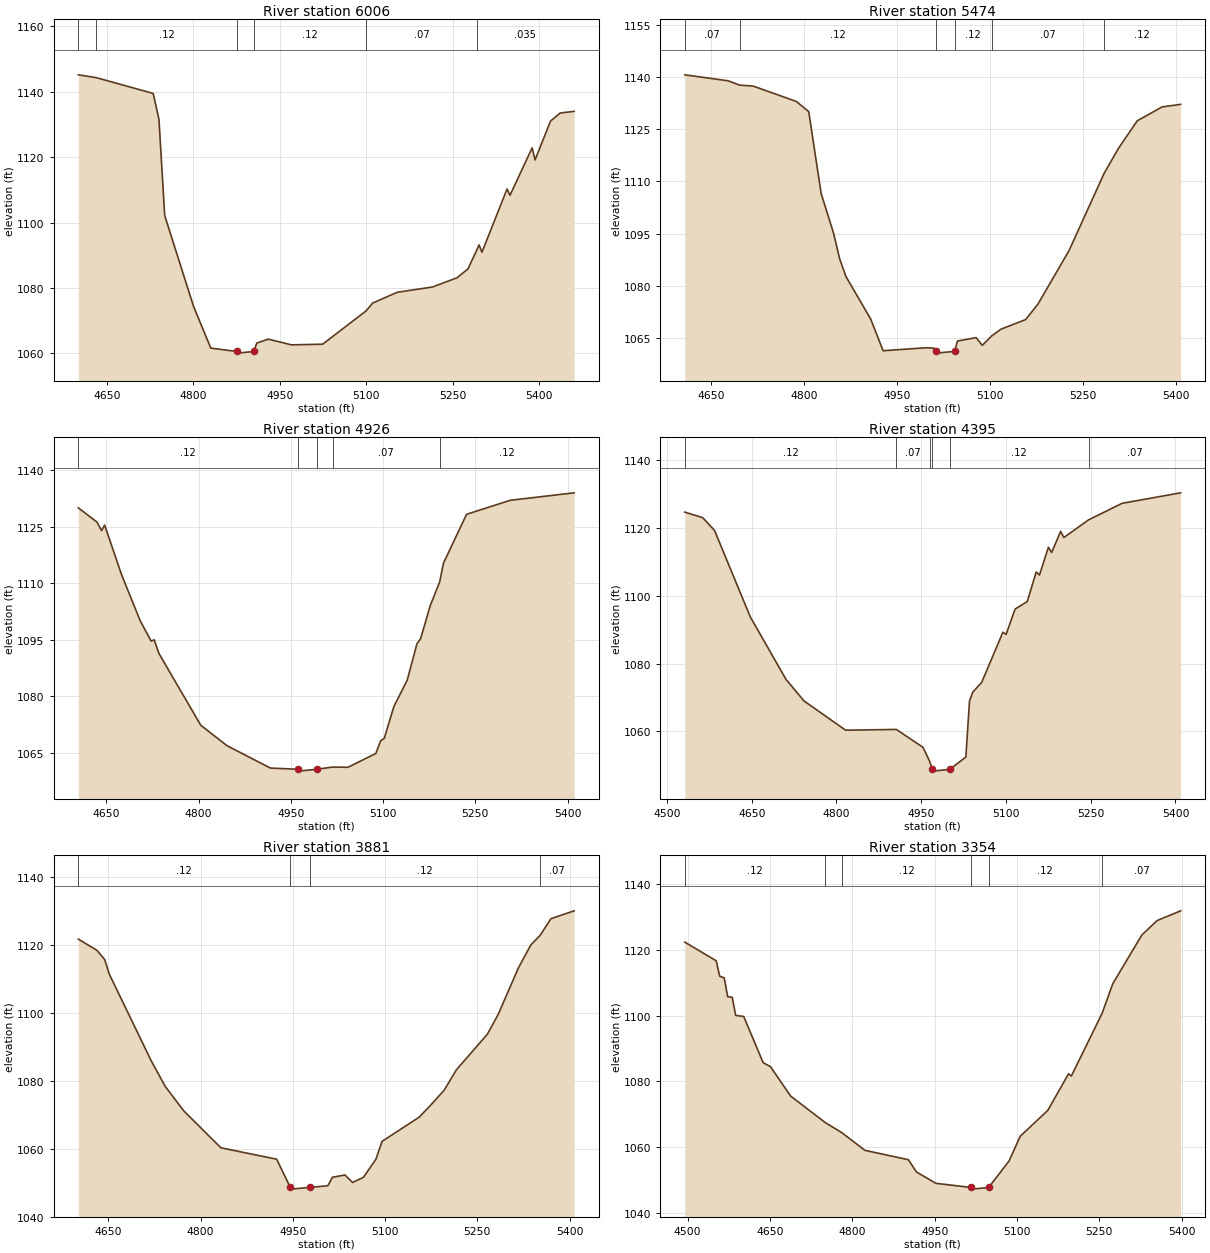
Type RM Length L Ch R = 1 ,6006    ,532,532,532
BEGIN DESCRIPTION:
SIMMONS CREEK 11.0
END DESCRIPTION:
XS GIS Cut Line= 3
      2132725.01       13879475.        2132325.       13879475.
      2131874.99       13879575.
#Sta/Elev= 30
  4600.1 1145.19  4631.3 1144.33  4730.1 1139.49  4740.1 1131.58  4750.1 1102.14
  4800.1  1074.4  4830.1 1061.59  4875.7 1060.56  4876.2 1060.06  4904.5 1060.56
  4910.1 1063.15  4930.1 1064.34  4970.1 1062.59  5024.4 1062.79  5099.7 1072.97
  5111.5  1075.4  5153.8 1078.66  5215.2 1080.29  5257.5 1083.09  5276.7 1085.82
  5291.8 1091.52  5295.9 1093.17    5301 1090.92  5344.6 1110.28  5349.7 1108.34
  5388.1 1122.85  5393.2 1119.15  5420.1 1131.05  5436.8  1133.5  5461.1 1134.02
#Mann= 6 ,-1 , 0
  4600.1     .07       0  4631.3     .12       0  4875.7     .05       0
  4904.5     .12       0  5099.7     .07       0  5291.8    .035       0
Bank Sta=4875.7,4904.5
XS Rating Curve= 0 ,0
Exp/Cntr=0.3,0.1

Type RM Length L Ch R = 1 ,5474    ,548,548,548
BEGIN DESCRIPTION:
SIMMONS CREEK 10.0
END DESCRIPTION:
XS GIS Cut Line= 3
      2132624.98       13879075.        2132225.       13879075.
      2131824.98       13879075.
#Sta/Elev= 30
  4607.8 1140.63  4677.8 1138.91  4696.5 1137.66  4717.8 1137.42  4787.8 1132.98
  4807.8 1130.06  4827.8 1106.53  4847.8 1095.18  4857.8  1087.7  4867.8 1082.71
  4907.8 1070.47  4927.8 1061.39  4997.8 1062.25  5010.3 1062.12  5012.4  1061.2
  5012.9  1060.7  5043.1  1061.2  5047.8 1064.17  5077.8 1065.15  5087.8 1062.94
  5103.1 1065.66  5117.8 1067.57  5157.8 1070.34  5177.8 1074.84  5227.8 1090.16
  5284.3 1112.32  5307.8 1119.59  5337.8 1127.42  5377.8 1131.41  5407.8 1132.15
#Mann= 6 ,-1 , 0
  4607.8     .07       0  4696.5     .12       0  5012.4     .05       0
  5043.1     .12       0  5103.1     .07       0  5284.3     .12       0
Bank Sta=5012.4,5043.1
XS Rating Curve= 0 ,0
Exp/Cntr=0.3,0.1

Type RM Length L Ch R = 1 ,4926    ,531,531,531
BEGIN DESCRIPTION:
SIMMONS CREEK 9.0
END DESCRIPTION:
XS GIS Cut Line= 3
      2132424.97       13878575.        2132025.       13878625.
      2131674.99       13878825.
#Sta/Elev= 30
  4604.5 1130.07  4634.7  1126.3  4642.3 1124.02  4647.3 1125.47    4675  1112.2
  4705.2 1100.01  4722.9 1094.63  4727.9 1094.97  4735.5 1091.37  4803.5 1072.27
  4846.3 1066.81  4916.9 1060.86  4961.9 1060.55  4962.4 1060.05  4992.7 1060.55
  5017.8 1061.13  5042.9 1061.07  5088.2 1064.74  5096.1 1068.12  5101.9 1068.75
  5117.7 1077.28  5139.3 1084.26  5155.1 1093.93  5160.9 1095.21  5176.7 1104.05
  5192.1  1110.4  5198.3 1115.39  5235.8 1128.35    5307 1132.08  5410.7 1134.06
#Mann= 5 ,-1 , 0
  4604.5     .12       0  4961.9     .05       0  4992.7     .12       0
  5017.8     .07       0  5192.1     .12       0
Bank Sta=4961.9,4992.7
XS Rating Curve= 0 ,0
Exp/Cntr=0.3,0.1

Type RM Length L Ch R = 1 ,4395    ,514,514,514
BEGIN DESCRIPTION:
SIMMONS CREEK 8.0
END DESCRIPTION:
XS GIS Cut Line= 3
      2132325.03     13878074.99        2131875.       13878225.
      2131524.99     13878425.01
#Sta/Elev= 30
  4531.6  1124.7  4563.3 1123.07  4584.3 1119.27  4647.6 1093.76  4710.8 1075.34
  4742.4 1069.03  4816.2 1060.36    4906 1060.59  4953.3  1055.3  4965.1 1051.14
  4969.5 1048.79    4970 1048.29  5000.3 1048.79    5029 1052.44  5035.5 1068.98
  5041.2 1071.57  5057.1 1074.49  5094.5 1089.25  5100.3 1088.64  5116.1 1096.09
  5137.7 1098.32  5153.5 1107.04  5159.3 1106.14  5175.1 1114.34  5180.9 1112.79
  5196.7 1119.02  5202.5 1117.22  5246.2 1122.41  5305.4 1127.29  5409.1 1130.39
#Mann= 6 ,-1 , 0
  4531.6     .12       0    4906     .07       0  4965.1     .12       0
  4969.5     .05       0  5000.3     .12       0  5246.2     .07       0
Bank Sta=4969.5,5000.3
XS Rating Curve= 0 ,0
Exp/Cntr=0.3,0.1

Type RM Length L Ch R = 1 ,3881    ,527,527,527
BEGIN DESCRIPTION:
SIMMONS CREEK 7.0
END DESCRIPTION:
XS GIS Cut Line= 3
      2132225.02       13877725.        2131825.       13877775.
      2131425.05     13877725.01
#Sta/Elev= 30
  4601.2 1121.83  4631.5 1118.52  4644.1 1115.79  4651.6 1111.48  4719.6 1085.99
  4742.3 1078.46  4772.5 1071.22    4833 1060.31  4923.7 1056.94  4945.9 1048.62
  4946.4 1048.12  4977.2 1048.62  5006.9 1049.12  5014.4 1051.62  5034.6 1052.29
  5047.2 1050.09  5064.8 1051.61    5085 1056.91    5095 1062.19  5155.5 1069.35
  5175.7  1073.2  5195.8 1077.23    5216 1083.32  5266.4 1093.81    5284 1099.68
  5316.7 1113.32  5336.9  1120.1  5351.9  1122.9  5369.7 1127.85  5407.4 1130.17
#Mann= 4 ,-1 , 0
  4601.2     .12       0  4945.9     .05       0  4977.2     .12       0
  5351.9     .07       0
Bank Sta=4945.9,4977.2
XS Rating Curve= 0 ,0
Exp/Cntr=0.3,0.1

Type RM Length L Ch R = 1 ,3354    ,511,511,511
BEGIN DESCRIPTION:
SIMMONS CREEK 6.0
END DESCRIPTION:
XS GIS Cut Line= 3
      2132224.98     13877574.98        2131825.       13877275.
      2131424.99       13877325.
#Sta/Elev= 30
  4494.9 1122.39  4552.2 1116.71  4558.4 1112.03  4566.7 1111.51    4573  1105.8
  4581.3  1105.6  4587.6 1100.08  4602.2 1099.77  4637.6 1085.71  4651.1 1084.47
  4687.6 1075.55  4750.8 1067.46  4780.9  1064.4    4823 1059.02  4902.2 1056.16
  4916.7 1052.45  4952.2 1048.98    5017 1047.71  5017.5 1047.21  5048.4 1047.71
  5085.6  1055.8  5105.7 1063.28  5156.1 1071.18  5193.9 1082.32    5199 1081.65
  5254.8 1100.64  5274.5 1109.76  5327.4 1124.56  5355.2 1128.96    5398 1131.92
#Mann= 6 ,-1 , 0
  4494.9     .12       0  4750.8     .07       0  4780.9     .12       0
    5017     .05       0  5048.4     .12       0  5254.8     .07       0
Bank Sta=5017,5048.4
XS Rating Curve= 0 ,0
Exp/Cntr=0.3,0.1

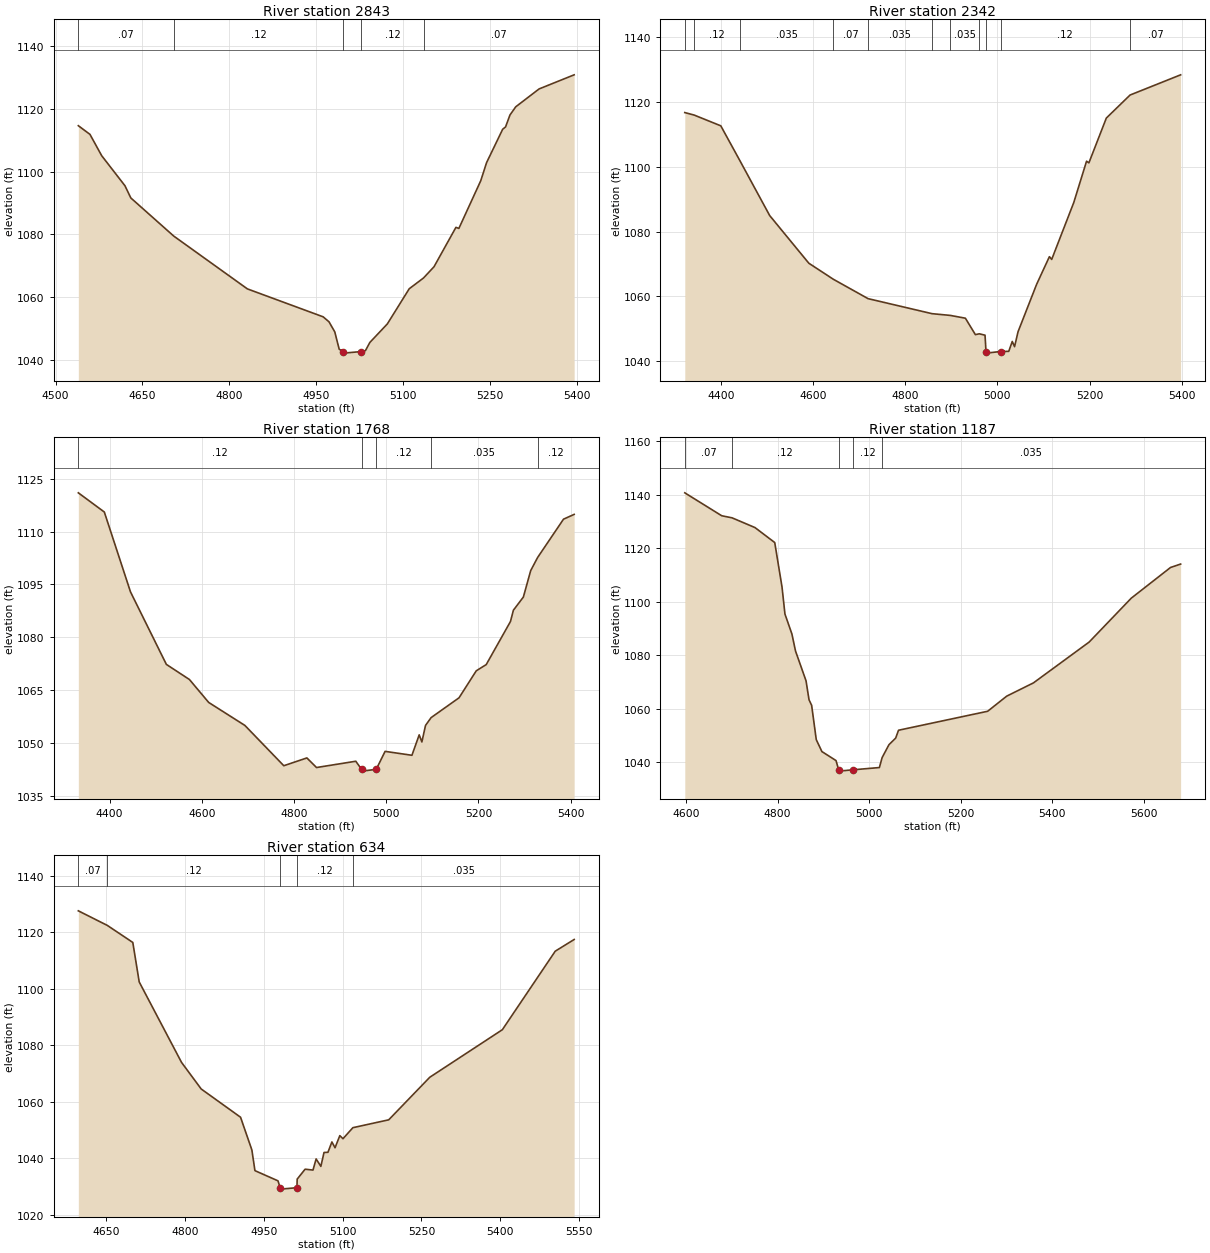
Type RM Length L Ch R = 1 ,2843    ,501,501,501
BEGIN DESCRIPTION:
SIMMONS CREEK 5.0
END DESCRIPTION:
XS GIS Cut Line= 3
      2132275.03       13876875.        2131825.       13876825.
      2131425.01       13876775.
#Sta/Elev= 30
  4539.4 1114.58  4559.5 1111.82  4579.7 1105.05  4619.9 1095.49    4630 1091.62
    4704 1079.51  4831.2 1062.71    4962 1053.83  4972.1 1052.25  4982.1 1049.04
  4989.7 1043.53  4996.6 1042.79  4997.1 1042.29  5028.2 1042.79    5035 1043.07
  5042.6 1045.68  5072.8 1051.57  5110.6 1062.75  5135.3 1066.18  5153.4 1069.75
  5191.2 1082.26  5196.3 1081.93  5234.1  1097.1  5244.1 1102.83  5271.9 1113.45
  5276.9  1114.2  5284.5 1117.99  5294.5 1120.59  5334.8 1126.27  5395.3 1130.75
#Mann= 5 ,-1 , 0
  4539.4     .07       0    4704     .12       0  4996.6     .05       0
  5028.2     .12       0  5135.3     .07       0
Bank Sta=4996.6,5028.2
XS Rating Curve= 0 ,0
Exp/Cntr=0.3,0.1

Type RM Length L Ch R = 1 ,2342    ,574,574,574
BEGIN DESCRIPTION:
SIMMONS CREEK 4.0
END DESCRIPTION:
XS GIS Cut Line= 3
        2132325.       13876825.        2131825.       13876375.
        2131425.       13876425.
#Sta/Elev= 30
  4321.7 1116.77    4342    1116  4399.8 1112.68  4441.3 1101.91  4505.9 1084.98
  4590.8 1070.27  4644.1 1065.31  4719.3 1059.34  4858.1  1054.7  4897.9 1054.16
  4930.5  1053.3  4952.2 1048.23  4960.7 1048.48  4973.1 1048.06  4975.2 1043.02
  4975.7 1042.52  5006.8 1043.02  5024.6 1043.07  5032.2 1046.12  5037.2 1044.51
  5044.8 1049.14  5085.1 1063.77  5112.8 1072.29  5117.8 1071.45  5165.7 1089.02
  5193.4 1101.76  5198.5 1101.25  5236.3 1115.07  5287.8 1122.18  5397.5 1128.42
#Mann= 11 ,-1 , 0
  4321.7     .07       0    4342     .12       0  4441.3    .035       0
  4644.1     .07       0  4719.3    .035       0  4858.1     .12       0
  4897.9    .035       0  4960.7     .12       0  4975.2     .05       0
  5006.8     .12       0  5287.8     .07       0
Bank Sta=4975.2,5006.8
XS Rating Curve= 0 ,0
Exp/Cntr=0.3,0.1

Type RM Length L Ch R = 1 ,1768    ,581,581,581
BEGIN DESCRIPTION:
SIMMONS CREEK 3.0
END DESCRIPTION:
XS GIS Cut Line= 3
      2132374.99     13875375.01        2131925.       13875875.
      2131574.98     13876075.01
#Sta/Elev= 30
    4332 1120.96  4388.4 1115.52  4445.2 1092.88    4523 1072.34    4573 1068.06
  4614.9 1061.55  4693.4 1055.04  4777.8 1043.62  4827.9 1045.83  4848.8 1043.11
    4934 1044.89  4946.6 1042.59  4947.1 1042.09  4978.3 1042.59  4997.6 1047.69
  5055.8 1046.58  5071.6 1052.37  5077.4 1050.36  5085.3 1055.04  5097.4 1057.25
    5158 1062.87  5195.4 1070.52    5217 1072.28  5269.6 1084.49    5276  1087.7
  5297.6 1091.42  5313.5 1098.91  5328.5 1102.63  5384.7 1113.49  5407.8 1114.85
#Mann= 5 ,-1 , 0
    4332     .12       0  4946.6     .05       0  4978.3     .12       0
  5097.4    .035       0  5328.5     .12       0
Bank Sta=4946.6,4978.3
XS Rating Curve= 0 ,0
Exp/Cntr=0.3,0.1

Type RM Length L Ch R = 1 ,1187    ,553,553,553
BEGIN DESCRIPTION:
SIMMONS CREEK 2.0
END DESCRIPTION:
XS GIS Cut Line= 3
        2132025.     13874974.99        2131825.       13875325.
        2131425.       13875875.
#Sta/Elev= 30
  4597.1 1140.75  4677.7 1132.18  4700.3  1131.4  4750.4 1127.76  4793.6 1122.15
  4809.5 1105.52  4815.9 1095.41  4831.1 1087.95    4839 1081.57    4862 1070.41
  4868.5 1063.33  4874.2 1061.28  4884.3 1048.44  4896.6 1043.97  4927.5 1040.59
  4933.2 1037.15  4933.7 1036.65  4965.1 1037.15  5022.2 1037.99  5028.2 1041.72
  5043.1 1046.53  5057.8 1049.01    5064 1051.94  5258.7 1059.04  5300.5 1064.71
  5358.8 1069.66  5480.5 1084.93  5572.5 1101.35  5658.3 1112.83  5680.3  1114.1
#Mann= 5 ,-1 , 0
  4597.1     .07       0  4700.3     .12       0  4933.2     .05       0
  4965.1     .12       0  5028.2    .035       0
Bank Sta=4933.2,4965.1
XS Rating Curve= 0 ,0
Exp/Cntr=0.3,0.1

Type RM Length L Ch R = 1 ,634     ,0,0,0
BEGIN DESCRIPTION:
SIMMONS CREEK 1.0
END DESCRIPTION:
XS GIS Cut Line= 3
        2131725.       13874925.        2131375.       13875125.
      2130925.04     13875424.98
#Sta/Elev= 30
  4596.9 1127.53  4652.2 1122.36  4700.6 1116.34  4712.8 1102.37  4793.4  1073.9
  4830.8  1064.5  4905.7 1054.51  4927.3 1042.91  4933.1 1035.61    4977    1032
  4981.1 1029.57  4981.6 1029.07  5013.1 1029.57  5013.5  1032.6  5028.6 1036.12
  5043.6 1035.81  5049.6 1039.75  5058.6 1037.12  5064.6 1042.03  5072.1  1042.1
  5079.6 1045.76  5085.6 1043.71  5094.7    1048  5100.7 1046.91  5119.6 1050.81
  5187.8 1053.59  5265.9 1068.64  5404.1 1085.47  5504.8 1113.25  5540.8 1117.39
#Mann= 5 ,-1 , 0
  4596.9     .07       0  4652.2     .12       0  4981.1     .05       0
  5013.1     .12       0  5119.6    .035       0
Bank Sta=4981.1,5013.1
XS Rating Curve= 0 ,0
Exp/Cntr=0.3,0.1

Chan Stop Cuts=-1
Use User Specified Reach Order=0
Composite Channel Slope=5