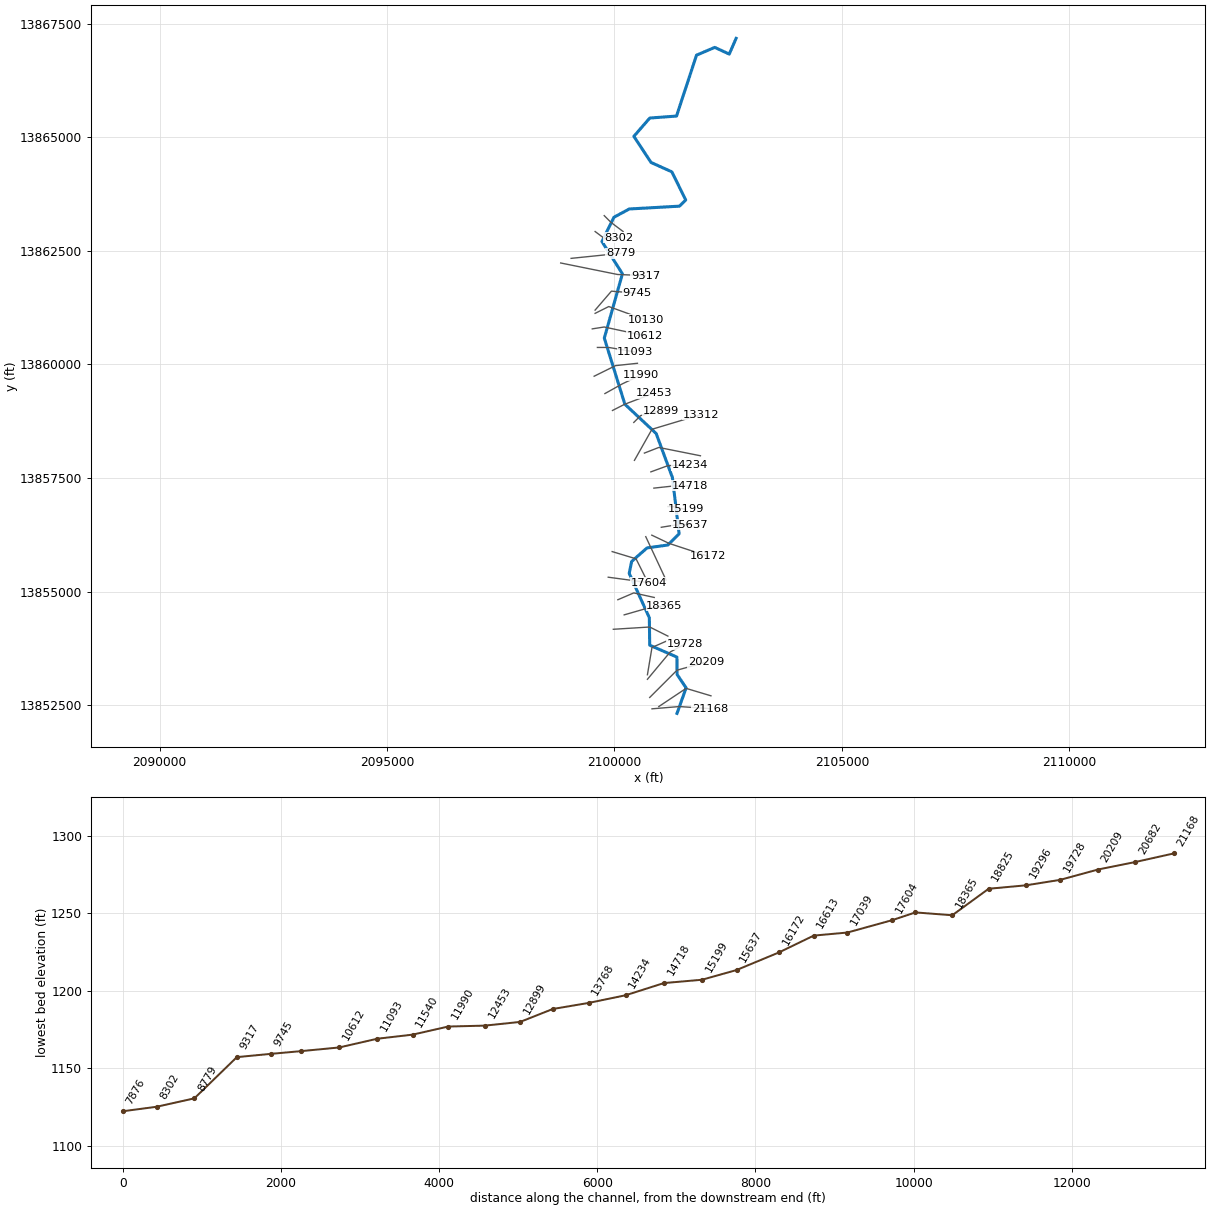
--- SWEDE CREEK.prj (project) ---

Proj Title=SWEDE CREEK Base Level Engineering
Current Plan=p01
Default Exp/Contr=0.3,0.1
English Units
Geom File=g01
Flow File=f01
Plan File=p01
Y Axis Title=Elevation
X Axis Title(PF)=Main Channel Distance
X Axis Title(XS)=Station
BEGIN DESCRIPTION:
SWEDE CREEK
END DESCRIPTION:
DSS Export Rating Curves= 0
DSS Export Rating Curve Sorted= 0
DSS Export Volume Flow Curves= 0
DXF OffsetX= 0
DXF OffsetY= 0
DXF ScaleX= 1
DXF ScaleY= 10

--- SWEDE CREEK.p01 (plan) ---

Plan Title=Multiple Run
Short Identifier=Multiple
Geom File=g01
Flow File=f01
Subcritical Flow
K Sum by GR= 0
Std Step Tol= 0.01
Critical Tol= 0.01
Num of Std Step Trials= 20
Max Error Tol= 0.3
Flow Tol Ratio= 0.001
Split Flow NTrial= 30
Split Flow Tol= 0.02
Split Flow Ratio= 0.02
Log Output Level= 0
Friction Slope Method= 1
Unsteady Friction Slope Method= 2
Unsteady Bridges Friction Slope Method= 1
Parabolic Critical Depth
Global Vel Dist=  1 , 1 , 1
Global Log Level= 0
CheckData=True
Encroach Param= -1, 0, 0, 0
BEGIN DESCRIPTION:
Multiple Run
END DESCRIPTION:

--- SWEDE CREEK.f01 (steady flow) ---

Flow Title=Multiple
Program Version=4.10
Number of Profiles= 7
Profile Names=10-year,25-year,50-year,1pct_min,100-year,1pct_plu,500-year
River Rch & RM=SWEDE CREEK,Reach-1         ,21168
    1155    1972    2756    1869    3729    7440    6747
River Rch & RM=SWEDE CREEK,Reach-1         ,18825
    2533    4484    6419    4441    8862   17682   16721
River Rch & RM=SWEDE CREEK,Reach-1         ,12453
    2686    4761    6820    4720    9418   18792   17784
River Rch & RM=SWEDE CREEK,Reach-1         ,9317
    4291    7747   11235    7860   15683   31291   30261
River Rch & RM=SWEDE CREEK,Reach-1         ,1902
    4773    8652   12582    8822   17602   35120   34120
Boundary for River Rch & Prof#=SWEDE CREEK,Reach-1         , 1
Up Type= 0
Dn Type= 3
Dn Slope=0.005
Boundary for River Rch & Prof#=SWEDE CREEK,Reach-1         , 2
Up Type= 0
Dn Type= 3
Dn Slope=0.005
Boundary for River Rch & Prof#=SWEDE CREEK,Reach-1         , 3
Up Type= 0
Dn Type= 3
Dn Slope=0.005
Boundary for River Rch & Prof#=SWEDE CREEK,Reach-1         , 4
Up Type= 0
Dn Type= 3
Dn Slope=0.005
Boundary for River Rch & Prof#=SWEDE CREEK,Reach-1         , 5
Up Type= 0
Dn Type= 3
Dn Slope=0.005
Boundary for River Rch & Prof#=SWEDE CREEK,Reach-1         , 6
Up Type= 0
Dn Type= 3
Dn Slope=0.005
Boundary for River Rch & Prof#=SWEDE CREEK,Reach-1         , 7
Up Type= 0
Dn Type= 3
Dn Slope=0.005
DSS Import GetInterval= 0
DSS Import GetPeak= 0
DSS Import FillOption= 0

--- SWEDE CREEK.g01 (geometry) ---

Geom Title=Existing Conditions

River Reach=SWEDE CREEK,Reach-1
Reach XY= 30
      2101375.00     13852325.00      2101575.46     13852885.19
      2101377.06     13853180.85      2101373.38     13853563.17
      2100775.00     13853825.00      2100766.92     13854428.30
      2100324.41     13855404.95      2100378.08     13855666.70
      2100715.20     13855964.52      2101173.45     13856028.75
      2101421.46     13856276.47      2101273.78     13857514.50
      2100917.12     13858481.16      2100228.54     13859126.47
      2099777.26     13860580.94      2100175.39     13861995.13
      2099724.80     13862705.08      2099988.48     13863238.56
      2100326.55     13863421.25      2101428.34     13863482.99
      2101567.19     13863618.81      2101261.37     13864238.21
      2100804.45     13864444.44      2100426.78     13865018.87
      2100776.47     13865421.45      2101364.39     13865464.94
      2101804.57     13866805.27      2102204.96     13866975.61
      2102523.72     13866828.37      2102675.00     13867175.00

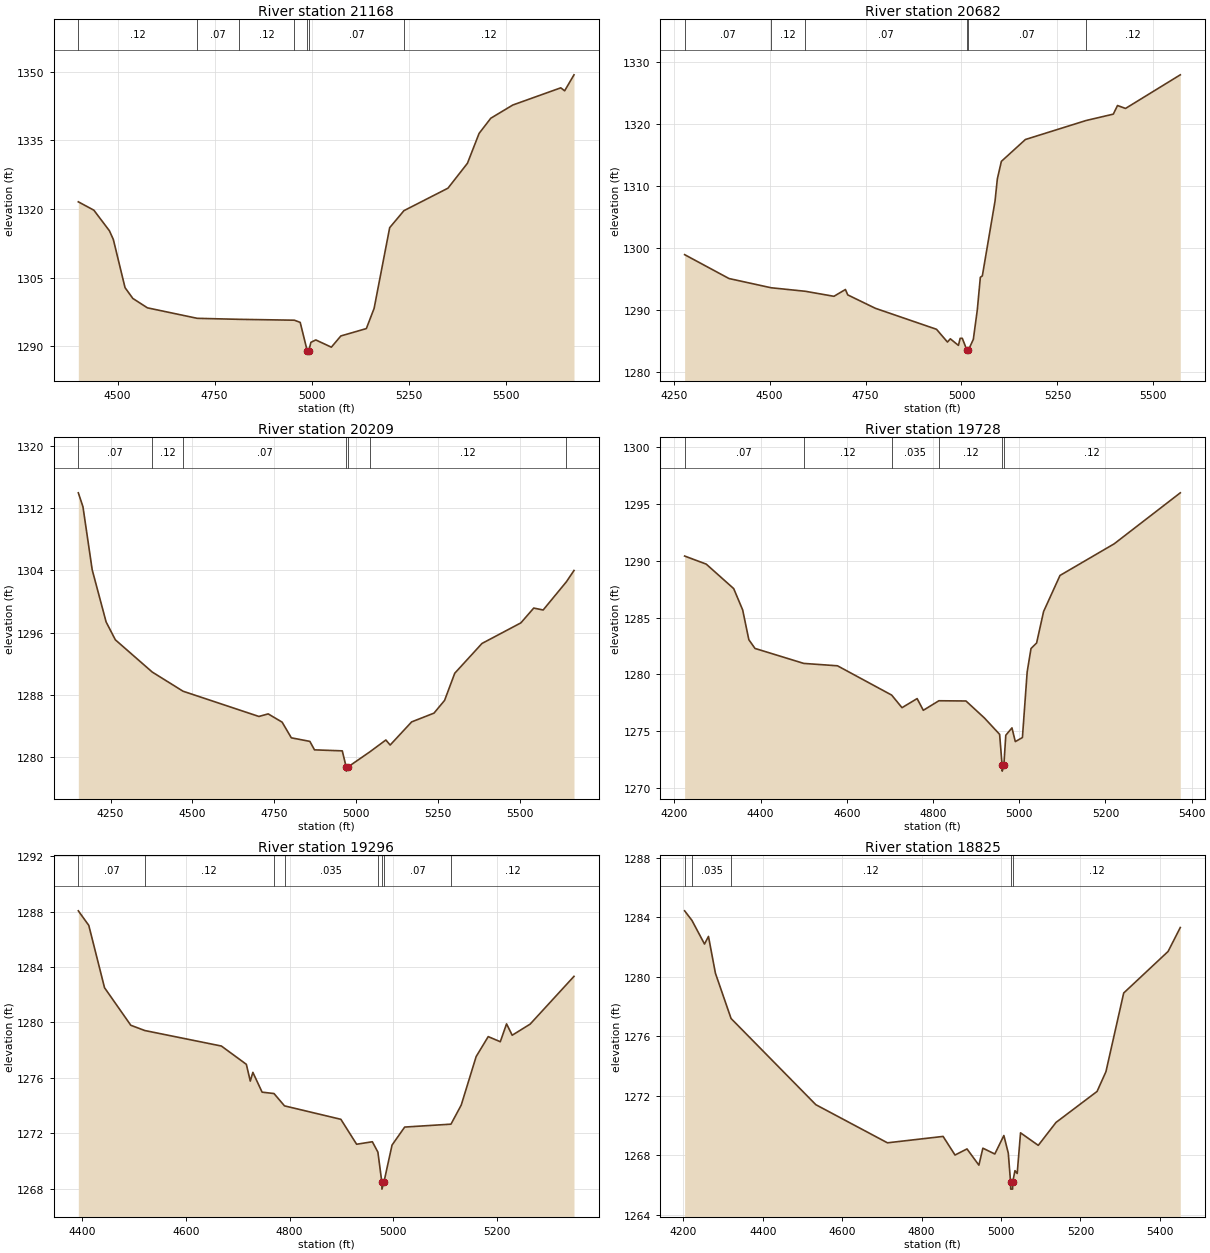
Type RM Length L Ch R = 1,21168,486,486,486
BEGIN DESCRIPTION:
SWEDE CREEK 46.0
END DESCRIPTION:
XS GIS Cut Line= 3
      2100825.03     13852425.00      2101425.00     13852475.00
      2102099.02     13852429.50
#Sta/Elev= 30
  4398.7 1321.58  4438.8 1319.75  4478.9 1315.25  4489.0 1313.34  4519.1 1302.84
  4539.2 1300.48  4576.8 1298.43  4705.2 1296.14  4813.1 1295.92  4955.6 1295.73
  4970.6 1295.25  4988.7 1289.04  4989.0 1288.54  4992.7 1289.04  4998.2 1290.90
  5010.8 1291.42  5050.9 1289.84  5075.4 1292.29  5141.1 1293.90  5161.1 1298.31
  5201.2 1315.93  5238.0 1319.65  5351.5 1324.56  5401.7 1330.00  5431.7 1336.52
  5461.8 1339.83  5518.6 1342.72  5642.2 1346.47  5652.2 1345.82  5676.3 1349.31
#Mann=7,-1,0
  4398.7    0.12       0  4705.2    0.07       0  4813.1    0.12       0
  4955.6    0.07       0  4988.7    0.05       0  4992.7    0.07       0
  5238.0    0.12       0
Bank Sta=4988.7,4992.7
Exp/Cntr=0.3,0.1

Type RM Length L Ch R = 1,20682,473,473,473
BEGIN DESCRIPTION:
SWEDE CREEK 45.0
END DESCRIPTION:
XS GIS Cut Line= 3
      2100975.01     13852475.01      2101575.00     13852875.00
      2102121.71     13852711.24
#Sta/Elev= 30
  4278.5 1298.92  4394.2 1295.06  4503.9 1293.57  4593.2 1293.00  4667.6 1292.19
  4697.6 1293.29  4703.6 1292.42  4775.7 1290.25  4935.0 1286.86  4963.5 1284.80
  4971.0 1285.32  4992.1 1284.26  4996.6 1285.40  5002.2 1285.40  5014.1 1283.51
  5014.4 1283.01  5018.1 1283.51  5030.9 1285.23  5041.3 1290.00  5049.2 1295.26
  5054.4 1295.49  5087.5 1307.58  5093.5 1311.16  5104.0 1313.99  5166.6 1317.52
  5324.8 1320.59  5395.7 1321.62  5406.7 1323.01  5427.6 1322.54  5570.3 1327.97
#Mann=6,-1,0
  4278.5    0.07       0  4503.9    0.12       0  4593.2    0.07       0
  5014.1    0.05       0  5018.1    0.07       0  5324.8    0.12       0
Bank Sta=5014.1,5018.1
Exp/Cntr=0.3,0.1

Type RM Length L Ch R = 1,20209,481,481,481
BEGIN DESCRIPTION:
SWEDE CREEK 44.0
END DESCRIPTION:
XS GIS Cut Line= 3
      2100775.00     13852675.00      2101375.00     13853275.00
      2102015.69     13853453.79
#Sta/Elev= 30
  4151.6 1314.00  4165.7 1312.22  4194.0 1304.08  4236.5 1297.37  4264.7 1295.07
  4377.3 1290.92  4471.4 1288.45  4703.1 1285.20  4731.4 1285.53  4773.9 1284.47
  4802.1 1282.45  4858.7 1281.99  4872.8 1280.90  4957.7 1280.77  4969.8 1278.66
  4970.1 1278.16  4973.8 1278.66  5042.1 1280.65  5090.8 1282.17  5103.9 1281.52
  5169.5 1284.50  5237.8 1285.63  5270.1 1287.27  5301.2 1290.77  5384.3 1294.60
  5503.0 1297.25  5542.4 1299.16  5571.1 1298.91  5642.2 1302.55  5665.3 1304.00
#Mann=7,-1,0
  4151.6    0.07       0  4377.3    0.12       0  4471.4    0.07       0
  4969.8    0.05       0  4973.8    0.07       0  5042.1    0.12       0
  5642.2    0.07       0
Bank Sta=4969.8,4973.8
Exp/Cntr=0.3,0.1

Type RM Length L Ch R = 1,19728,432,432,432
BEGIN DESCRIPTION:
SWEDE CREEK 43.0
END DESCRIPTION:
XS GIS Cut Line= 3
      2100725.02     13853075.03      2101225.00     13853675.00
      2101549.99     13853850.00
#Sta/Elev= 30
  4223.6 1290.42  4273.7 1289.71  4337.5 1287.55  4358.3 1285.67  4372.6 1283.05
  4386.9 1282.28  4500.1 1280.96  4578.3 1280.75  4704.0 1278.17  4728.0 1277.06
  4763.1 1277.86  4777.4 1276.83  4813.6 1277.67  4876.4 1277.65  4919.3 1276.15
  4954.5 1274.71  4960.3 1271.97  4960.5 1271.47  4964.3 1271.97  4968.8 1274.63
  4983.1 1275.28  4990.9 1274.07  5007.4 1274.43  5018.4 1280.21  5027.3 1282.27
  5040.3 1282.76  5056.5 1285.53  5094.6 1288.71  5220.4 1291.50  5373.7 1295.99
#Mann=6,-1,0
  4223.6    0.07       0  4500.1    0.12       0  4704.0   0.035       0
  4813.6    0.12       0  4960.3    0.05       0  4964.3    0.12       0
Bank Sta=4960.3,4964.3
Exp/Cntr=0.3,0.1

Type RM Length L Ch R = 1,19296,471,471,471
BEGIN DESCRIPTION:
SWEDE CREEK 42.0
END DESCRIPTION:
XS GIS Cut Line= 3
      2100725.01     13853175.04      2100825.00     13853775.00
      2101144.17     13853915.60
#Sta/Elev= 30
  4392.2 1288.05  4412.4 1287.00  4442.8 1282.50  4493.5 1279.79  4520.4 1279.41
  4668.4 1278.29  4716.6 1276.97  4724.2 1275.76  4729.2 1276.39  4747.0 1274.96
  4770.0 1274.86  4790.3 1273.97  4899.1 1273.00  4929.5 1271.20  4959.9 1271.38
  4970.6 1270.63  4978.2 1268.46  4978.4 1267.96  4982.2 1268.46  4997.9 1271.14
  5022.3 1272.44  5111.7 1272.65  5131.5 1274.03  5160.3 1277.53  5183.6 1278.97
  5206.9 1278.60  5219.0 1279.89  5229.9 1279.07  5264.5 1279.87  5349.2 1283.32
#Mann=8,-1,0
  4392.2    0.07       0  4520.4    0.12       0  4770.0    0.07       0
  4790.3   0.035       0  4970.6    0.07       0  4978.2    0.05       0
  4982.2    0.07       0  5111.7    0.12       0
Bank Sta=4978.2,4982.2
Exp/Cntr=0.3,0.1

Type RM Length L Ch R = 1,18825,460,460,460
BEGIN DESCRIPTION:
SWEDE CREEK 41.0
END DESCRIPTION:
XS GIS Cut Line= 3
      2099975.02     13854175.00      2100775.00     13854225.00
      2101175.04     13854024.98
#Sta/Elev= 30
  4202.9 1284.43  4221.3 1283.79  4253.0 1282.20  4263.0 1282.71  4280.5 1280.24
  4319.9 1277.20  4533.5 1271.41  4713.9 1268.85  4854.1 1269.28  4884.2 1268.03
  4914.3 1268.44  4944.3 1267.35  4954.3 1268.49  4984.4 1268.10  5007.2 1269.34
  5018.4 1268.15  5024.0 1266.24  5024.5 1265.74  5029.2 1265.74  5029.6 1266.24
  5035.2 1266.98  5040.8 1266.79  5049.2 1269.52  5093.9 1268.68  5138.6 1270.22
  5242.0 1272.30  5264.4 1273.63  5309.1 1278.91  5420.9 1281.70  5451.7 1283.31
#Mann=5,-1,0
  4202.9    0.12       0  4221.3   0.035       0  4319.9    0.12       0
  5024.0    0.05       0  5029.6    0.12       0
Bank Sta=5024,5029.6
Exp/Cntr=0.3,0.1

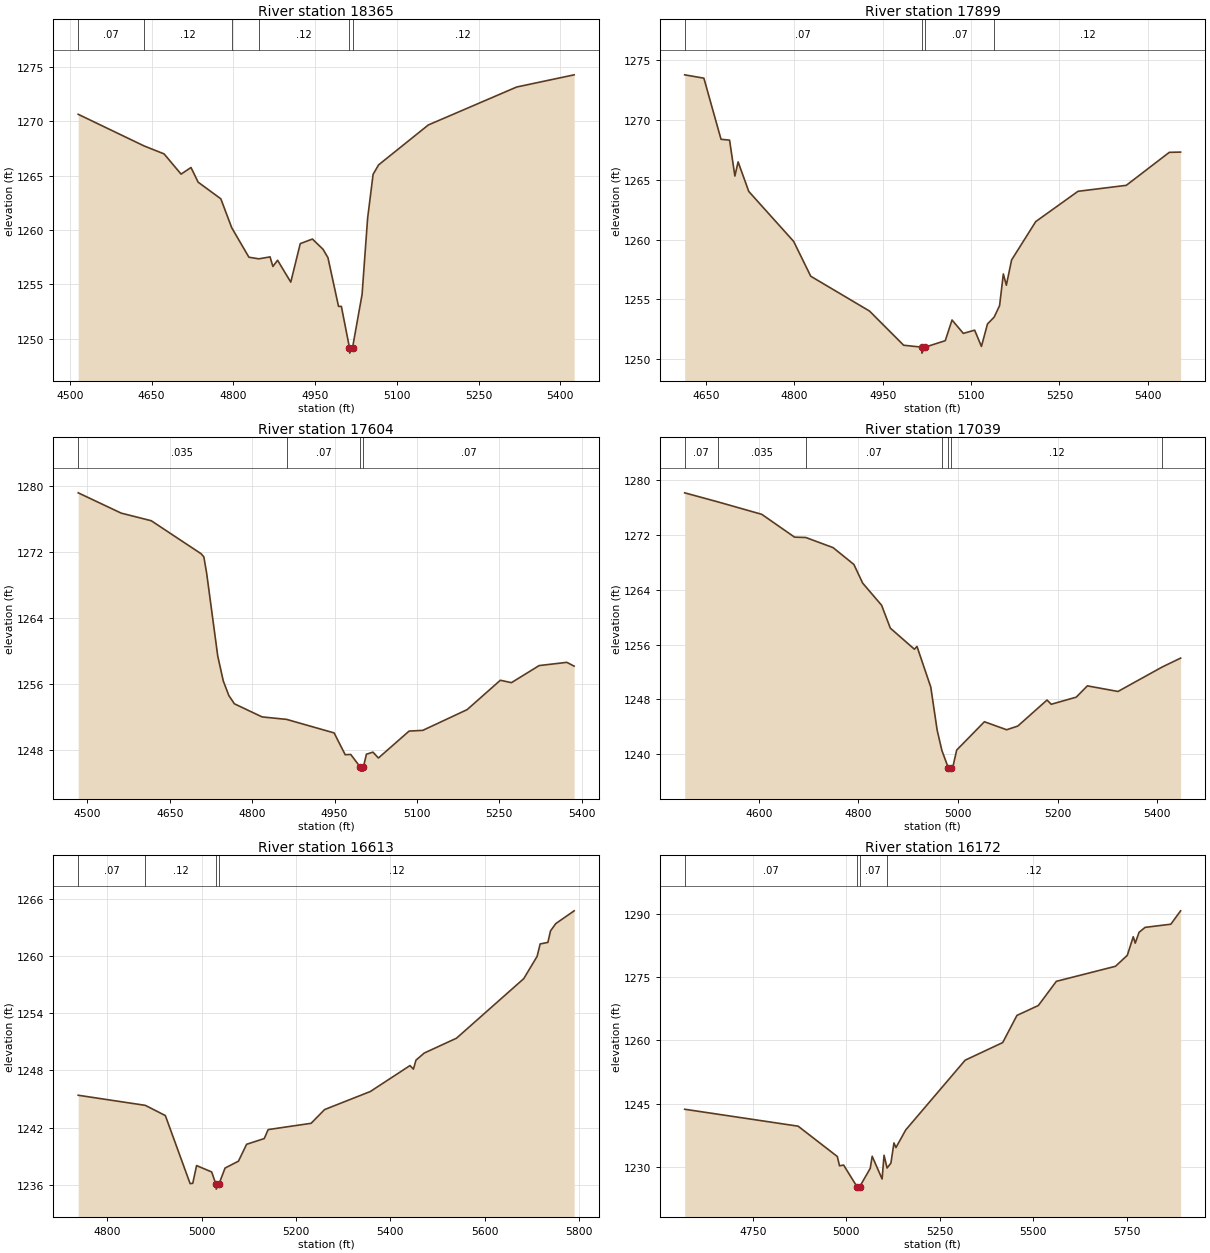
Type RM Length L Ch R = 1,18365,466,466,466
BEGIN DESCRIPTION:
SWEDE CREEK 40.0
END DESCRIPTION:
XS GIS Cut Line= 3
      2100213.65     13854492.00      2100675.00     13854625.00
      2101099.08     13854693.39
#Sta/Elev= 30
  4515.5 1270.63  4636.4 1267.72  4673.0 1266.99  4704.2 1265.13  4722.4 1265.74
  4735.5 1264.39  4777.1 1262.86  4797.1 1260.20  4828.6 1257.49  4846.9 1257.34
  4867.4 1257.52  4872.6 1256.64  4881.2 1257.21  4905.4 1255.20  4922.8 1258.74
  4945.1 1259.16  4964.4 1258.23  4973.6 1257.45  4993.0 1252.97  4998.2 1252.97
  5013.1 1249.17  5013.5 1248.67  5018.7 1249.17  5036.2 1254.07  5046.3 1261.05
  5056.4 1265.11  5066.5 1265.98  5157.7 1269.65  5319.8 1273.14  5425.2 1274.26
#Mann=6,-1,0
  4515.5    0.07       0  4636.4    0.12       0  4797.1    0.07       0
  4846.9    0.12       0  5013.1    0.05       0  5018.7    0.12       0
Bank Sta=5013.1,5018.7
Exp/Cntr=0.3,0.1

Type RM Length L Ch R = 1,17899,295,295,295
BEGIN DESCRIPTION:
SWEDE CREEK 39.0
END DESCRIPTION:
XS GIS Cut Line= 3
      2100075.00     13854825.00      2100425.00     13854975.00
      2100875.03     13854874.99
#Sta/Elev= 30
  4613.8 1273.77  4646.4 1273.49  4675.5 1268.38  4690.0 1268.31  4699.0 1265.31
  4704.5 1266.49  4722.6 1264.02  4798.8 1259.84  4827.8 1256.93  4927.5 1254.02
  4985.5 1251.16  5016.0 1251.00  5016.5 1250.50  5021.8 1251.00  5056.1 1251.54
  5067.6 1253.27  5086.8 1252.15  5106.0 1252.42  5117.5 1251.06  5127.8 1252.94
  5139.1 1253.51  5148.3 1254.47  5154.7 1257.12  5159.8 1256.18  5168.7 1258.29
  5209.7 1261.50  5281.4 1264.03  5363.4 1264.53  5436.4 1267.29  5455.6 1267.31
#Mann=4,-1,0
  4613.8    0.07       0  5016.0    0.05       0  5021.8    0.07       0
  5139.1    0.12       0
Bank Sta=5016,5021.8
Exp/Cntr=0.3,0.1

Type RM Length L Ch R = 1,17604,565,565,565
BEGIN DESCRIPTION:
SWEDE CREEK 38.0
END DESCRIPTION:
XS GIS Cut Line= 2
      2099863.16     13855320.58      2100758.15     13855199.86
#Sta/Elev= 30
  4483.3 1279.21  4561.6 1276.75  4616.3 1275.83  4707.1 1271.83  4712.1 1271.45
  4717.2 1269.47  4737.4 1259.43  4747.5 1256.41  4757.6 1254.65  4767.7 1253.65
  4818.1 1252.06  4862.7 1251.76  4949.3 1250.12  4969.5 1247.48  4979.6 1247.51
  4996.8 1245.99  4997.3 1245.49  5002.2 1245.49  5002.7 1245.99  5008.1 1247.54
  5020.0 1247.79  5030.0 1247.08  5085.8 1250.34  5110.8 1250.43  5191.5 1252.94
  5252.0 1256.50  5272.2 1256.21  5322.7 1258.28  5373.1 1258.67  5386.4 1258.21
#Mann=4,-1,0
  4483.3   0.035       0  4862.7    0.07       0  4996.8    0.05       0
  5002.7    0.07       0
Bank Sta=4996.8,5002.7
Exp/Cntr=0.3,0.1

Type RM Length L Ch R = 1,17039,426,426,426
BEGIN DESCRIPTION:
SWEDE CREEK 37.0
END DESCRIPTION:
XS GIS Cut Line= 3
      2099949.75     13855884.35      2100475.00     13855725.00
      2100675.00     13855325.00
#Sta/Elev= 30
  4450.9 1278.16  4517.6 1276.84  4605.8 1275.02  4671.6 1271.69  4694.1 1271.64
  4749.0 1270.16  4790.8 1267.70  4808.4 1264.98  4846.5 1261.74  4863.9 1258.41
  4912.3 1255.33  4917.5 1255.73  4945.2 1249.80  4958.0 1243.52  4967.5 1240.55
  4980.3 1238.03  4980.8 1237.53  4986.3 1238.03  4989.3 1238.06  4997.2 1240.60
  5052.9 1244.74  5097.6 1243.57  5120.0 1244.11  5178.7 1247.91  5187.1 1247.29
  5237.4 1248.33  5259.7 1249.98  5321.2 1249.16  5409.7 1252.72  5447.0 1254.03
#Mann=7,-1,0
  4450.9    0.07       0  4517.6   0.035       0  4694.1    0.07       0
  4967.5    0.12       0  4980.3    0.05       0  4986.3    0.12       0
  5409.7    0.07       0
Bank Sta=4980.3,4986.3
Exp/Cntr=0.3,0.1

Type RM Length L Ch R = 1,16613,441,441,441
BEGIN DESCRIPTION:
SWEDE CREEK 36.0
END DESCRIPTION:
XS GIS Cut Line= 2
      2100688.28     13856212.40      2101133.64     13855259.65
#Sta/Elev= 30
  4738.2 1245.39  4880.6 1244.33  4923.0 1243.26  4975.5 1236.13  4981.1 1236.16
  4989.2 1238.02  5021.2 1237.35  5030.4 1236.05  5030.9 1235.55  5036.4 1236.05
  5049.6 1237.76  5078.0 1238.48  5095.3 1240.25  5132.7 1240.85  5141.0 1241.79
  5232.1 1242.45  5260.7 1243.89  5357.6 1245.78  5441.8 1248.50  5449.0 1248.13
  5454.5 1249.07  5471.9 1249.81  5540.4 1251.37  5683.0 1257.61  5711.4 1259.95
  5717.8 1261.25  5734.2 1261.41  5739.8 1262.62  5750.9 1263.38  5789.9 1264.72
#Mann=4,-1,0
  4738.2    0.07       0  4880.6    0.12       0  5030.4    0.05       0
  5036.4    0.12       0
Bank Sta=5030.4,5036.4
Exp/Cntr=0.3,0.1

Type RM Length L Ch R = 1,16172,535,535,535
BEGIN DESCRIPTION:
SWEDE CREEK 35.0
END DESCRIPTION:
XS GIS Cut Line= 3
      2100821.23     13856245.49      2101199.75     13856064.91
      2102060.44     13855780.33
#Sta/Elev= 30
  4567.8 1243.66  4871.1 1239.64  4975.9 1232.43  4981.8 1230.22  4992.7 1230.40
  5029.1 1225.18  5029.6 1224.68  5035.2 1225.18  5063.9 1229.62  5069.1 1232.49
  5095.6 1227.09  5100.8 1232.73  5108.9 1229.70  5119.1 1230.85  5127.3 1235.66
  5132.6 1234.55  5159.0 1238.77  5317.7 1255.32  5418.1 1259.51  5456.1 1265.96
  5513.3 1268.31  5561.5 1274.06  5719.5 1277.63  5751.1 1280.23  5767.1 1284.66
  5772.4 1283.13  5782.6 1285.71  5798.8 1286.88  5867.5 1287.63  5893.7 1290.81
#Mann=4,-1,0
  4567.8    0.07       0  5029.1    0.05       0  5035.2    0.07       0
  5108.9    0.12       0
Bank Sta=5029.1,5035.2
Exp/Cntr=0.3,0.1

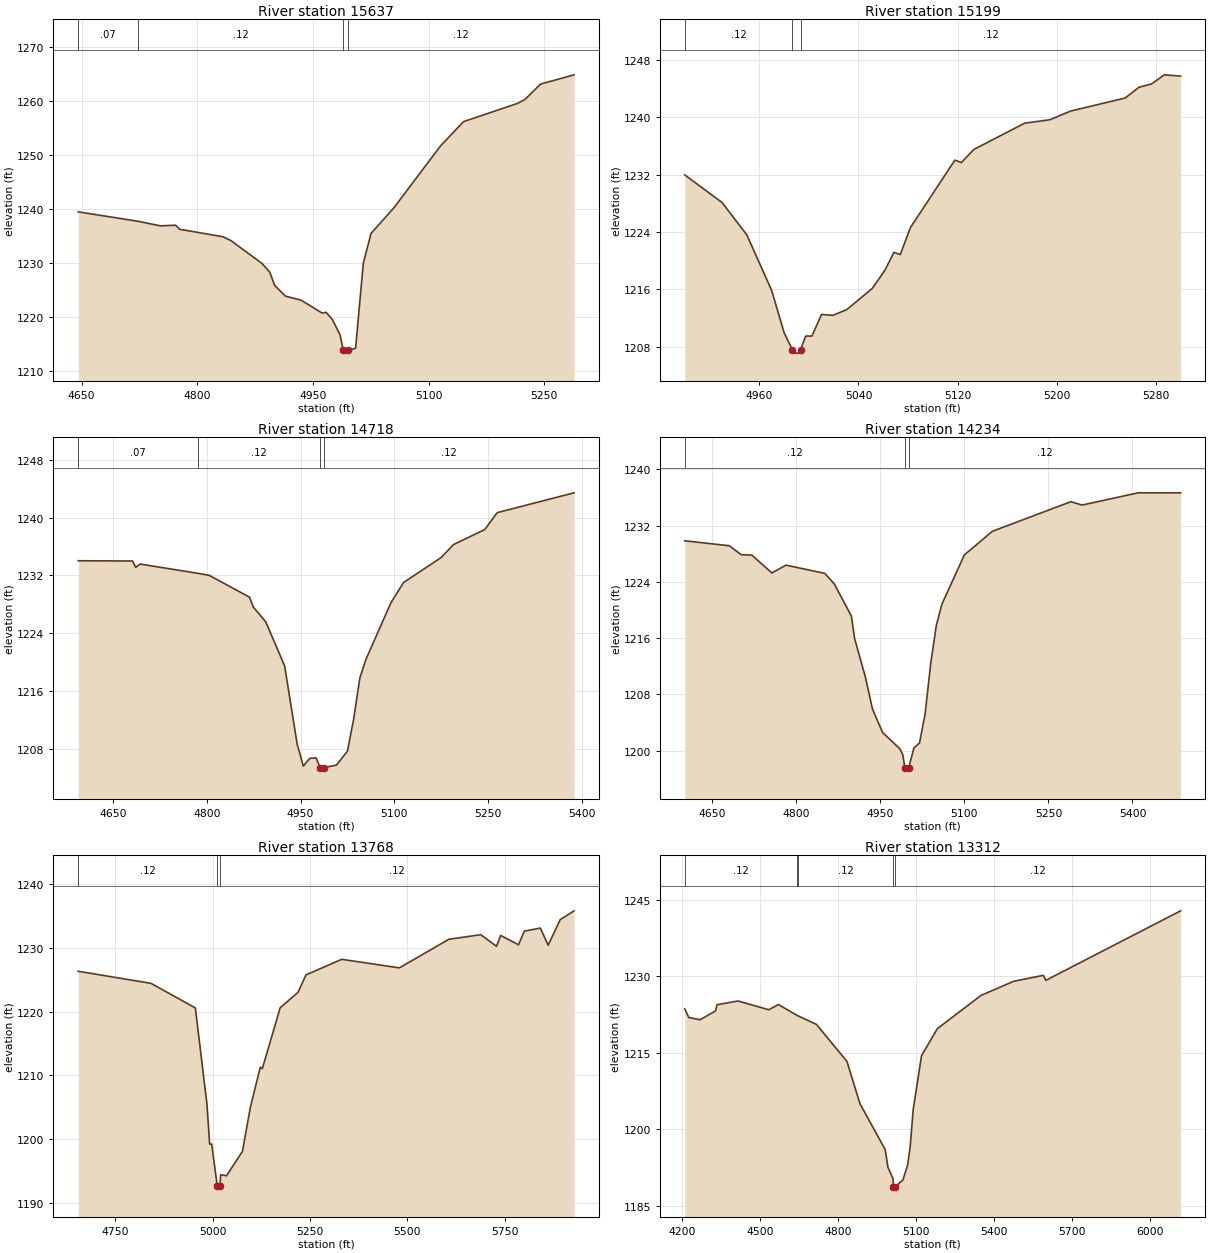
Type RM Length L Ch R = 1,15637,438,438,438
BEGIN DESCRIPTION:
SWEDE CREEK 34.0
END DESCRIPTION:
XS GIS Cut Line= 3
      2101029.63     13856419.08      2101375.00     13856475.00
      2101668.52     13856478.11
#Sta/Elev= 30
  4645.5 1239.47  4723.3 1237.72  4752.2 1236.88  4771.9 1237.00  4777.0 1236.25
  4833.3 1234.87  4843.7 1234.15  4883.9 1229.94  4894.1 1228.31  4900.3 1225.89
  4914.3 1223.89  4934.6 1223.15  4962.0 1220.75  4967.1 1220.90  4975.1 1219.60
  4985.2 1216.74  4989.5 1213.85  4990.0 1213.35  4995.6 1213.35  4996.1 1213.85
  5005.4 1214.25  5015.4 1229.94  5025.4 1235.47  5055.4 1240.27  5115.4 1251.62
  5145.4 1256.14  5215.4 1259.51  5225.4 1260.28  5245.4 1263.09  5288.9 1264.80
#Mann=4,-1,0
  4645.5    0.07       0  4723.3    0.12       0  4989.5    0.05       0
  4996.1    0.12       0
Bank Sta=4989.5,4996.1
Exp/Cntr=0.3,0.1

Type RM Length L Ch R = 1,15199,481,481,481
BEGIN DESCRIPTION:
SWEDE CREEK 33.0
END DESCRIPTION:
XS GIS Cut Line= 3
      2101175.02     13856875.00      2101275.00     13856875.00
      2101567.80     13856811.44
#Sta/Elev= 30
  4900.0 1231.95  4930.0 1228.11  4950.0 1223.59  4970.0 1215.85  4980.0 1209.97
  4986.6 1207.58  4987.1 1207.08  4992.8 1207.08  4993.3 1207.58  4997.5 1209.46
  5002.5 1209.46  5010.2 1212.47  5019.4 1212.35  5030.7 1213.17  5051.1 1216.10
  5061.4 1218.67  5068.6 1221.15  5073.7 1220.83  5081.8 1224.58  5117.7 1234.01
  5122.9 1233.67  5133.0 1235.50  5173.9 1239.16  5194.4 1239.65  5210.9 1240.85
  5255.0 1242.68  5266.0 1244.17  5276.3 1244.65  5286.5 1245.91  5299.6 1245.73
#Mann=3,-1,0
  4900.0    0.12       0  4986.6    0.05       0  4993.3    0.12       0
Bank Sta=4986.6,4993.3
Exp/Cntr=0.3,0.1

Type RM Length L Ch R = 1,14718,484,484,484
BEGIN DESCRIPTION:
SWEDE CREEK 32.0
END DESCRIPTION:
XS GIS Cut Line= 3
      2100866.38     13857280.19      2101275.00     13857325.00
      2101658.11     13857328.80
#Sta/Elev= 30
  4593.8 1234.04  4680.9 1234.00  4685.9 1233.13  4693.0 1233.58  4785.5 1232.30
  4803.7 1232.02  4868.2 1229.00  4874.1 1227.65  4894.2 1225.59  4924.4 1219.51
  4944.5 1208.68  4954.3 1205.65  4964.6 1206.71  4974.7 1206.78  4981.3 1205.45
  4981.8 1204.95  4987.6 1204.95  4988.1 1205.45  5007.4 1205.78  5024.9 1207.70
  5034.9 1212.11  5044.9 1217.84  5054.9 1220.46  5094.9 1228.28  5114.9 1231.03
  5174.9 1234.47  5194.9 1236.28  5244.9 1238.35  5264.9 1240.69  5388.0 1243.43
#Mann=4,-1,0
  4593.8    0.07       0  4785.5    0.12       0  4981.3    0.05       0
  4988.1    0.12       0
Bank Sta=4981.3,4988.1
Exp/Cntr=0.3,0.1

Type RM Length L Ch R = 1,14234,466,466,466
BEGIN DESCRIPTION:
SWEDE CREEK 31.0
END DESCRIPTION:
XS GIS Cut Line= 3
      2100800.43     13857637.82      2101175.00     13857775.00
      2101660.75     13857787.11
#Sta/Elev= 30
  4601.1 1229.83  4680.5 1229.13  4701.8 1227.86  4720.8 1227.80  4756.6 1225.26
  4781.8 1226.37  4850.9 1225.20  4868.0 1223.70  4898.5 1219.12  4904.2 1215.94
  4923.7 1210.38  4936.1 1205.91  4954.2 1202.58  4984.7 1200.28  4990.1 1199.45
  4993.9 1197.59  4994.4 1197.09  5000.8 1197.59  5010.0 1200.38  5020.0 1201.09
  5030.0 1205.21  5040.0 1212.38  5050.0 1217.79  5060.0 1220.83  5100.0 1227.82
  5150.0 1231.18  5290.1 1235.39  5310.1 1234.91  5410.1 1236.65  5485.9 1236.65
#Mann=3,-1,0
  4601.1    0.12       0  4993.9    0.05       0  5000.8    0.12       0
Bank Sta=4993.9,5000.8
Exp/Cntr=0.3,0.1

Type RM Length L Ch R = 1,13768,456,456,456
BEGIN DESCRIPTION:
SWEDE CREEK 30.0
END DESCRIPTION:
XS GIS Cut Line= 3
      2100658.13     13858051.04      2100975.00     13858175.00
      2101890.34     13857992.07
#Sta/Elev= 30
  4654.6 1226.31  4841.5 1224.42  4955.5 1220.56  4985.3 1205.48  4992.2 1199.23
  4997.4 1199.23  5011.8 1192.67  5012.3 1192.17  5018.7 1192.67  5020.4 1194.42
  5035.6 1194.27  5076.5 1198.10  5096.8 1205.01  5122.4 1211.29  5127.5 1211.05
  5173.4 1220.59  5219.2 1223.01  5239.6 1225.74  5331.5 1228.18  5479.4 1226.84
  5606.7 1231.32  5688.6 1232.04  5729.1 1230.22  5739.6 1231.93  5785.5 1230.46
  5800.5 1232.60  5841.6 1233.08  5861.7 1230.39  5892.6 1234.40  5928.3 1235.78
#Mann=3,-1,0
  4654.6    0.12       0  5011.8    0.05       0  5018.7    0.12       0
Bank Sta=5011.8,5018.7
Exp/Cntr=0.3,0.1

Type RM Length L Ch R = 1,13312,413,413,413
BEGIN DESCRIPTION:
SWEDE CREEK 29.0
END DESCRIPTION:
XS GIS Cut Line= 3
      2100439.35     13857891.33      2100825.00     13858575.00
      2101900.59     13858898.08
#Sta/Elev= 30
  4210.7 1223.62  4226.4 1221.93  4269.8 1221.50  4329.1 1223.22  4334.8 1224.45
  4415.7 1225.18  4534.2 1223.46  4570.8 1224.48  4641.1 1222.42  4647.8 1222.23
  4717.6 1220.58  4834.9 1213.30  4885.1 1204.98  4981.9 1196.00  4992.8 1192.47
  5012.2 1190.26  5013.5 1188.72  5014.0 1188.22  5021.2 1188.72  5050.4 1190.03
  5068.7 1193.04  5078.2 1196.57  5089.6 1203.79  5121.7 1214.42  5182.6 1219.74
  5350.6 1226.27  5475.9 1229.04  5590.8 1230.22  5600.0 1229.23  6118.7 1242.89
#Mann=5,-1,0
  4210.7    0.12       0  4641.1    0.07       0  4647.8    0.12       0
  5013.5    0.05       0  5021.2    0.12       0
Bank Sta=5013.5,5021.2
Exp/Cntr=0.3,0.1

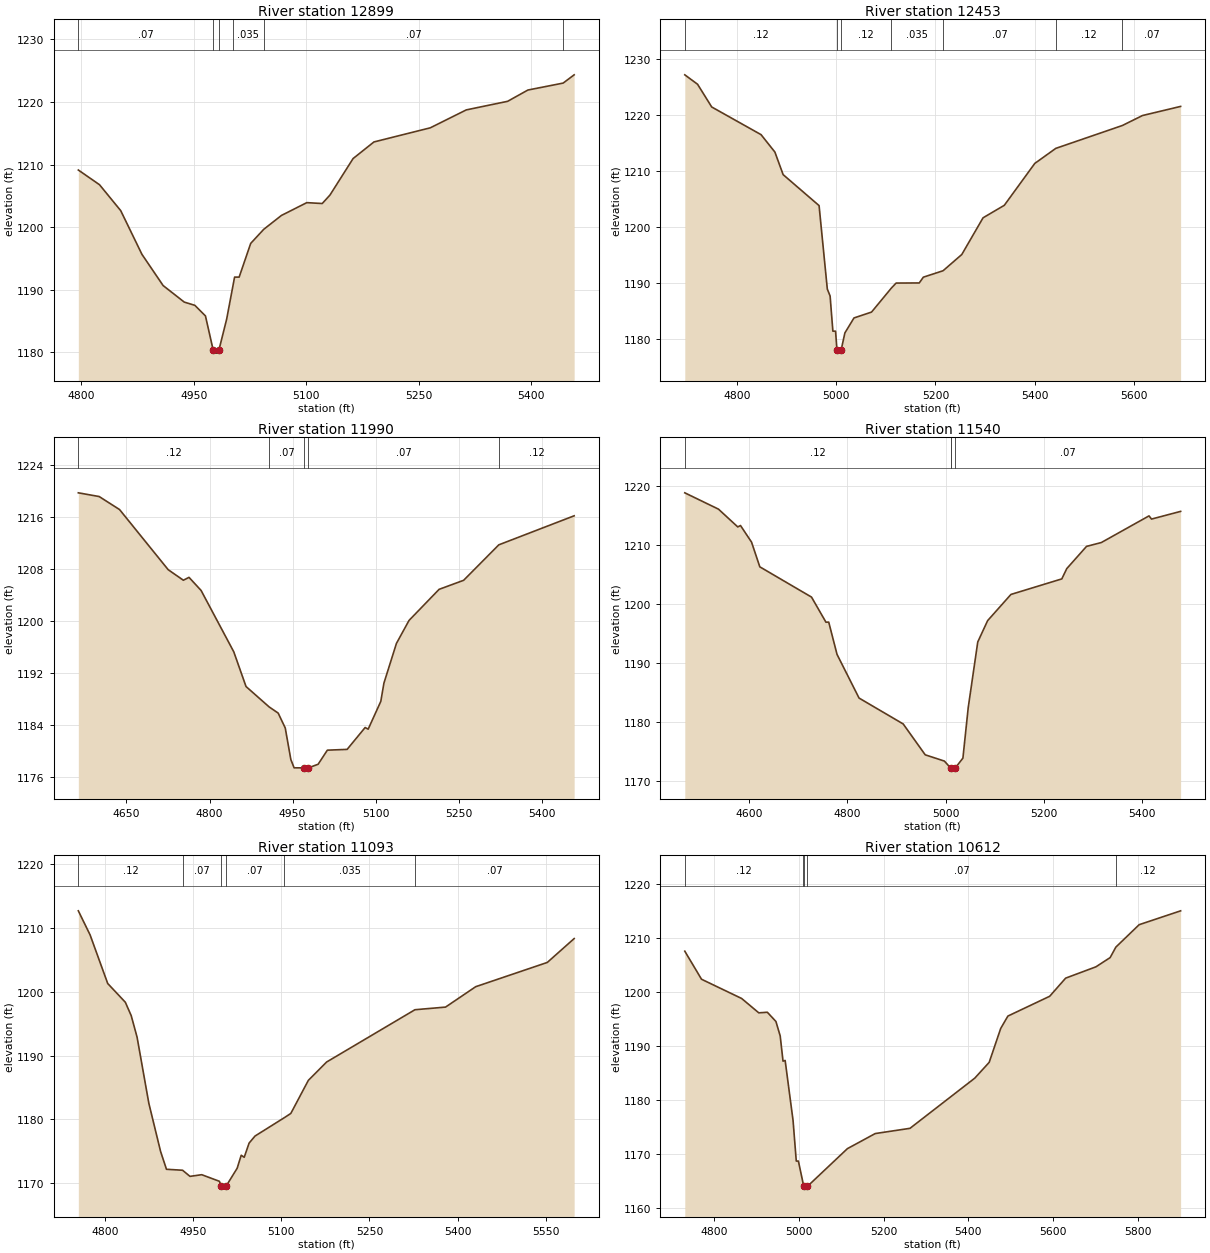
Type RM Length L Ch R = 1,12899,446,446,446
BEGIN DESCRIPTION:
SWEDE CREEK 28.0
END DESCRIPTION:
XS GIS Cut Line= 3
      2100424.99     13858724.99      2100575.00     13858875.00
      2101011.15     13858984.77
#Sta/Elev= 30
  4795.8 1209.13  4824.1 1206.78  4852.4 1202.64  4880.7 1195.67  4909.0 1190.68
  4937.2 1188.04  4951.4 1187.52  4965.5 1185.83  4975.8 1180.39  4976.3 1179.89
  4983.0 1179.89  4983.5 1180.39  4993.8 1185.31  5001.7 1190.32  5004.4 1192.03
  5010.5 1192.03  5025.9 1197.41  5043.4 1199.67  5067.0 1201.88  5100.8 1203.92
  5121.4 1203.78  5131.7 1205.13  5162.6 1210.96  5190.4 1213.61  5265.7 1215.87
  5313.7 1218.73  5368.9 1220.10  5395.9 1221.90  5443.0 1223.01  5457.7 1224.33
#Mann=6,-1,0
  4795.8    0.07       0  4975.8    0.05       0  4983.5    0.07       0
  5001.7   0.035       0  5043.4    0.07       0  5443.0    0.12       0
Bank Sta=4975.8,4983.5
Exp/Cntr=0.3,0.1

Type RM Length L Ch R = 1,12453,463,463,463
BEGIN DESCRIPTION:
SWEDE CREEK 27.0
END DESCRIPTION:
XS GIS Cut Line= 3
      2099956.66     13858988.51      2100225.00     13859125.00
      2100876.83     13859373.94
#Sta/Elev= 30
  4695.1 1227.20  4720.9 1225.51  4749.3 1221.46  4848.7 1216.52  4876.6 1213.41
  4893.2 1209.38  4965.6 1203.85  4982.2 1188.94  4987.8 1187.72  4993.4 1181.43
  4998.8 1181.43  5001.7 1178.01  5002.2 1177.51  5009.9 1178.01  5017.6 1181.12
  5035.9 1183.79  5071.3 1184.84  5111.1 1189.11  5120.8 1190.02  5167.4 1190.04
  5175.6 1191.07  5215.4 1192.22  5253.1 1195.12  5295.9 1201.67  5338.7 1203.90
  5400.1 1211.38  5442.5 1214.07  5576.8 1218.16  5617.0 1219.93  5693.9 1221.56
#Mann=7,-1,0
  4695.1    0.12       0  5001.7    0.05       0  5009.9    0.12       0
  5111.1   0.035       0  5215.4    0.07       0  5442.5    0.12       0
  5576.8    0.07       0
Bank Sta=5001.7,5009.9
Exp/Cntr=0.3,0.1

Type RM Length L Ch R = 1,11990,450,450,450
BEGIN DESCRIPTION:
SWEDE CREEK 26.0
END DESCRIPTION:
XS GIS Cut Line= 3
      2099790.03     13859360.05      2100175.00     13859575.00
      2100585.19     13859769.78
#Sta/Elev= 30
  4563.2 1219.68  4600.8 1219.11  4637.6 1217.11  4725.4 1207.87  4752.8 1206.25
  4763.0 1206.69  4784.8 1204.68  4843.8 1195.25  4865.9 1189.92  4907.7 1186.78
  4923.9 1185.84  4936.7 1183.55  4946.8 1178.70  4952.7 1177.43  4970.3 1177.42
  4970.8 1176.92  4978.6 1177.42  4996.1 1177.98  5012.7 1180.14  5048.4 1180.26
  5080.9 1183.62  5086.4 1183.37  5109.2 1187.64  5114.8 1190.44  5137.4 1196.54
  5160.1 1200.07  5214.4 1204.85  5258.7 1206.24  5322.2 1211.69  5458.2 1216.15
#Mann=5,-1,0
  4563.2    0.12       0  4907.7    0.07       0  4970.3    0.05       0
  4978.6    0.07       0  5322.2    0.12       0
Bank Sta=4970.3,4978.6
Exp/Cntr=0.3,0.1

Type RM Length L Ch R = 1,11540,447,447,447
BEGIN DESCRIPTION:
SWEDE CREEK 25.0
END DESCRIPTION:
XS GIS Cut Line= 3
      2099553.90     13859741.99      2100025.00     13859975.00
      2100505.34     13860026.72
#Sta/Elev= 30
  4469.6 1218.78  4538.1 1216.02  4577.4 1213.01  4582.9 1213.25  4605.4 1210.44
  4622.2 1206.26  4727.4 1201.14  4756.8 1196.89  4762.4 1196.91  4779.3 1191.45
  4824.1 1184.06  4913.9 1179.68  4958.7 1174.46  4997.7 1173.40  5010.6 1172.21
  5011.1 1172.20  5011.6 1171.70  5019.5 1172.20  5035.4 1173.90  5046.2 1182.45
  5065.6 1193.55  5085.7 1197.16  5133.1 1201.59  5236.6 1204.22  5246.6 1205.95
  5286.9 1209.72  5317.0 1210.37  5414.0 1214.88  5419.1 1214.34  5478.3 1215.64
#Mann=4,-1,0
  4469.6    0.12       0  5010.6    0.07       0  5011.1    0.05       0
  5019.5    0.07       0
Bank Sta=5011.1,5019.5
Exp/Cntr=0.3,0.1

Type RM Length L Ch R = 1,11093,481,481,481
BEGIN DESCRIPTION:
SWEDE CREEK 24.0
END DESCRIPTION:
XS GIS Cut Line= 3
      2099625.05     13860375.00      2099875.00     13860375.00
      2100460.07     13860273.26
#Sta/Elev= 30
  4754.7 1212.68  4774.7 1208.91  4804.7 1201.29  4834.7 1198.35  4844.7 1196.25
  4854.7 1192.87  4874.7 1182.51  4894.7 1174.96  4904.7 1172.17  4932.1 1172.02
  4944.7 1171.06  4964.7 1171.32  4994.7 1170.29  4998.0 1169.56  4998.5 1169.06
  5006.4 1169.56  5025.0 1172.33  5031.9 1174.37  5037.0 1174.05  5045.3 1176.27
  5055.4 1177.38  5105.3 1180.26  5116.3 1180.92  5146.1 1186.10  5177.2 1188.98
  5327.6 1197.18  5379.6 1197.59  5431.0 1200.79  5552.8 1204.59  5598.5 1208.33
#Mann=6,-1,0
  4754.7    0.12       0  4932.1    0.07       0  4998.0    0.05       0
  5006.4    0.07       0  5105.3   0.035       0  5327.6    0.07       0
Bank Sta=4998,5006.4
Exp/Cntr=0.3,0.1

Type RM Length L Ch R = 1,10612,482,482,482
BEGIN DESCRIPTION:
SWEDE CREEK 23.0
END DESCRIPTION:
XS GIS Cut Line= 3
      2099512.25     13860783.66      2099775.00     13860825.00
      2100660.77     13860634.52
#Sta/Elev= 30
  4729.8 1207.55  4769.3 1202.35  4864.2 1198.78  4904.7 1196.12  4924.9 1196.23
  4945.2 1194.52  4955.3 1191.84  4962.0 1187.16  4967.0 1187.29  4985.7 1176.17
  4993.3 1168.64  4998.3 1168.64  5009.8 1164.39  5011.1 1163.94  5011.6 1163.44
  5019.5 1163.94  5114.1 1170.94  5179.9 1173.74  5262.1 1174.71  5415.2 1184.01
  5449.3 1186.94  5476.5 1193.22  5493.5 1195.52  5592.3 1199.19  5630.0 1202.55
  5701.6 1204.65  5735.2 1206.36  5748.8 1208.31  5803.8 1212.46  5901.8 1215.03
#Mann=5,-1,0
  4729.8    0.12       0  5009.8    0.07       0  5011.1    0.05       0
  5019.5    0.07       0  5748.8    0.12       0
Bank Sta=5011.1,5019.5
Exp/Cntr=0.3,0.1

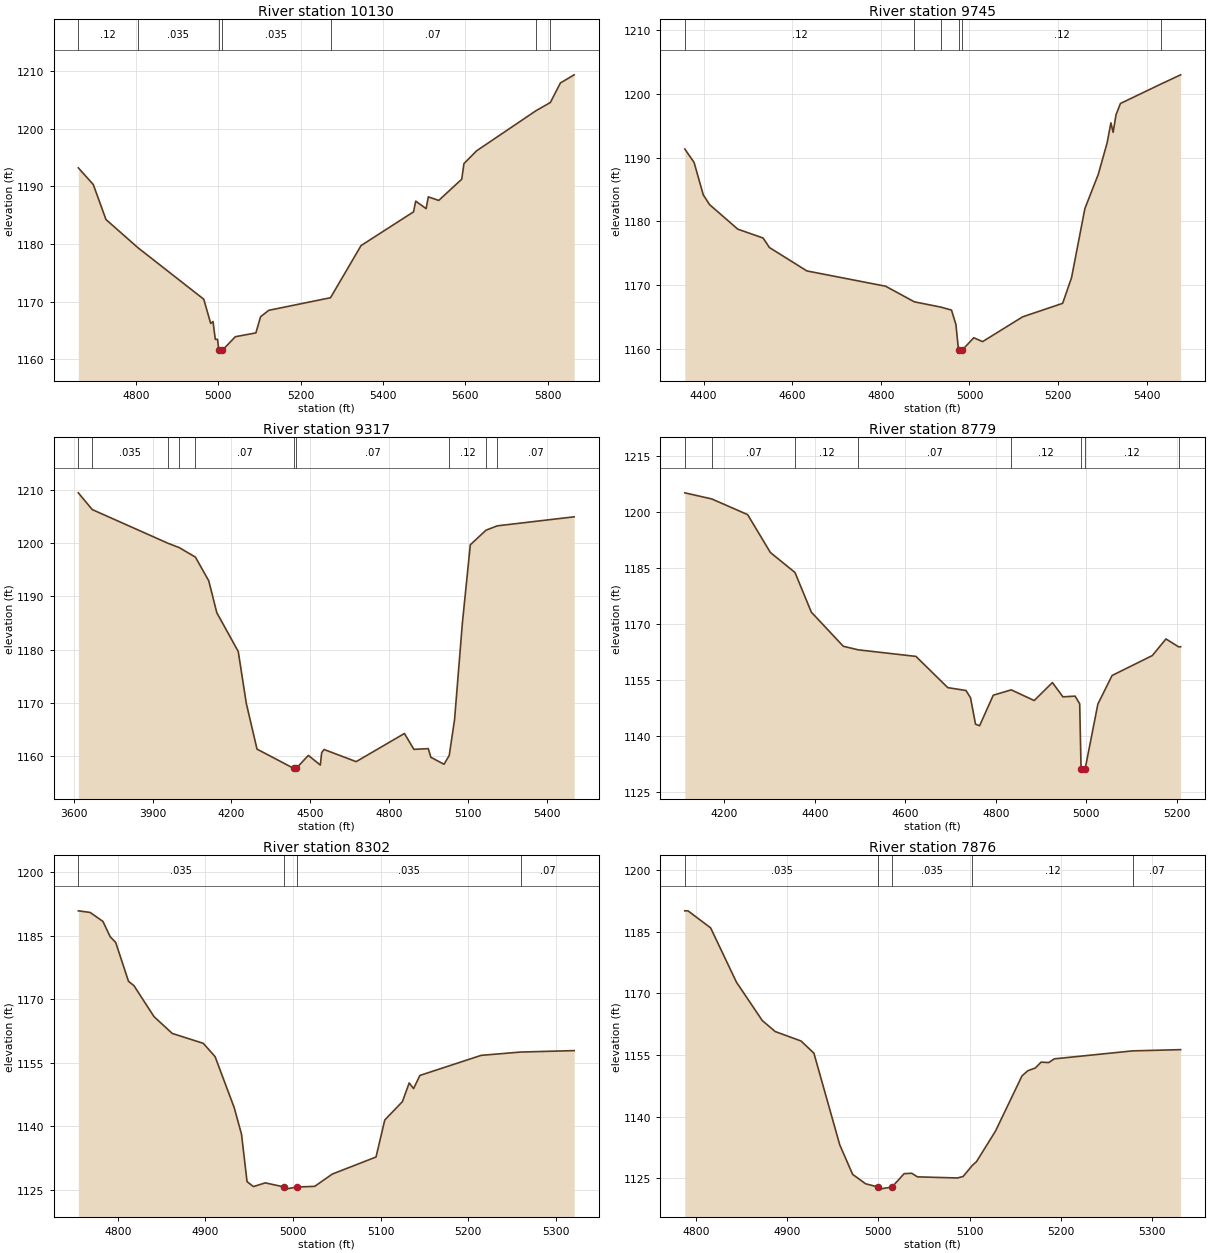
Type RM Length L Ch R = 1,10130,385,385,385
BEGIN DESCRIPTION:
SWEDE CREEK 22.0
END DESCRIPTION:
XS GIS Cut Line= 3
      2099575.02     13861125.01      2099875.00     13861275.00
      2100691.38     13860978.62
#Sta/Elev= 30
  4660.5 1193.21  4696.8 1190.32  4727.6 1184.25  4805.2 1179.36  4965.1 1170.42
  4981.9 1166.22  4987.5 1166.55  4993.1 1163.46  4998.5 1163.46  5001.6 1161.57
  5002.1 1161.07  5010.1 1161.57  5041.8 1163.92  5091.6 1164.58  5103.0 1167.38
  5123.0 1168.50  5272.8 1170.68  5347.0 1179.73  5474.4 1185.58  5479.7 1187.44
  5505.0 1186.14  5510.3 1188.18  5535.6 1187.56  5591.5 1191.25  5596.8 1193.95
  5627.4 1196.16  5771.8 1203.13  5806.6 1204.55  5831.0 1207.94  5864.4 1209.35
#Mann=7,-1,0
  4660.5    0.12       0  4805.2   0.035       0  5001.6   0.035       0
  5010.1   0.035       0  5272.8    0.07       0  5771.8    0.12       0
  5806.6    0.07       0
Bank Sta=5001.6,5010.1
Exp/Cntr=0.3,0.1

Type RM Length L Ch R = 1,9745,428,428,428
BEGIN DESCRIPTION:
SWEDE CREEK 21.0
END DESCRIPTION:
XS GIS Cut Line= 3
      2099574.58     13861196.29      2099933.96     13861613.41
      2100500.33     13861567.60
#Sta/Elev= 30
  4357.7 1191.36  4378.6 1189.26  4399.4 1184.16  4413.7 1182.62  4477.3 1178.77
  4534.4 1177.38  4548.6 1175.89  4633.2 1172.21  4810.8 1169.81  4875.6 1167.36
  4935.9 1166.52  4959.5 1166.06  4969.5 1163.79  4975.3 1159.80  4975.8 1159.30
  4983.9 1159.80  5009.7 1161.71  5029.7 1161.11  5120.0 1165.00  5210.3 1167.12
  5230.4 1171.16  5260.5 1182.01  5290.6 1187.36  5310.6 1192.31  5319.2 1195.47
  5324.2 1193.98  5330.7 1196.73  5340.7 1198.51  5431.4 1201.54  5476.5 1203.01
#Mann=6,-1,0
  4357.7    0.12       0  4875.6    0.07       0  4935.9    0.12       0
  4975.3    0.05       0  4983.9    0.12       0  5431.4   0.035       0
Bank Sta=4975.3,4983.9
Exp/Cntr=0.3,0.1

Type RM Length L Ch R = 1,9317,538,538,538
BEGIN DESCRIPTION:
SWEDE CREEK 20.0
END DESCRIPTION:
XS GIS Cut Line= 3
      2098818.33     13862233.10      2100067.32     13861980.15
      2100679.96     13861955.14
#Sta/Elev= 30
  3617.4 1209.41  3670.3 1206.27  3960.1 1199.92  4001.4 1199.14  4063.2 1197.35
  4114.0 1192.90  4144.6 1186.92  4226.2 1179.65  4256.8 1169.93  4297.6 1161.34
  4438.0 1157.71  4438.5 1157.21  4446.6 1157.71  4493.0 1160.16  4538.6 1158.35
  4543.7 1160.67  4552.7 1161.27  4675.1 1158.99  4858.8 1164.27  4894.9 1161.29
  4949.5 1161.43  4959.5 1159.80  5009.5 1158.50  5029.3 1160.14  5049.6 1166.86
  5079.6 1185.10  5109.6 1199.66  5169.3 1202.40  5212.4 1203.22  5504.9 1204.91
#Mann=10,-1,0
  3617.4    0.07       0  3670.3   0.035       0  3960.1    0.07       0
  4001.4    0.12       0  4063.2    0.07       0  4438.0    0.05       0
  4446.6    0.07       0  5029.3    0.12       0  5169.3   0.035       0
  5212.4    0.07       0
Bank Sta=4438,4446.6
Exp/Cntr=0.3,0.1

Type RM Length L Ch R = 1,8779,477,477,477
BEGIN DESCRIPTION:
SWEDE CREEK 19.0
END DESCRIPTION:
XS GIS Cut Line= 3
      2099046.79     13862334.63      2099925.00     13862425.00
      2100137.26     13862443.38
#Sta/Elev= 30
  4112.3 1205.21  4172.0 1203.57  4251.2 1199.37  4301.5 1189.21  4355.8 1183.87
  4392.0 1173.23  4462.6 1164.09  4495.6 1163.13  4623.2 1161.37  4693.6 1153.00
  4733.8 1152.23  4743.8 1150.29  4754.9 1143.20  4763.9 1142.79  4794.1 1150.97
  4833.8 1152.40  4884.6 1149.54  4924.8 1154.36  4948.1 1150.53  4975.0 1150.72
  4985.1 1148.67  4988.2 1131.12  4988.7 1130.62  4997.0 1131.12  5025.3 1148.59
  5056.7 1156.25  5145.7 1161.60  5175.8 1166.05  5203.9 1163.92  5208.2 1163.96
#Mann=8,-1,0
  4112.3   0.035       0  4172.0    0.07       0  4355.8    0.12       0
  4495.6    0.07       0  4833.8    0.12       0  4988.2    0.05       0
  4997.0    0.12       0  5203.9    0.07       0
Bank Sta=4988.2,4997
Exp/Cntr=0.3,0.1

Type RM Length L Ch R = 1,8302,426,426,426
BEGIN DESCRIPTION:
SWEDE CREEK 18.0
END DESCRIPTION:
XS GIS Cut Line= 3
      2099575.02     13862924.98      2099775.00     13862775.00
      2100091.10     13862787.09
#Sta/Elev= 30
  4754.8 1190.88  4768.3 1190.50  4782.9 1188.38  4791.2 1184.77  4797.5 1183.41
  4812.1 1174.25  4818.3 1173.23  4841.2 1165.92  4862.1 1161.94  4897.5 1159.61
  4911.0 1156.47  4932.9 1144.40  4941.2 1138.12  4947.5 1126.96  4954.8 1125.80
  4968.3 1126.68  4990.1 1125.70  4990.6 1125.20  5004.9 1125.70  5024.8 1125.86
  5044.8 1128.75  5094.8 1132.78  5104.8 1141.52  5124.9 1145.84  5132.7 1150.26
  5137.7 1148.93  5144.9 1152.03  5214.9 1156.77  5259.9 1157.55  5321.1 1157.89
#Mann=4,-1,0
  4754.8   0.035       0  4990.1    0.05       0  5004.9   0.035       0
  5259.9    0.07       0
Bank Sta=4990.1,5004.9
Exp/Cntr=0.3,0.1

Type RM Length L Ch R = 1,7876,463,463,463
BEGIN DESCRIPTION:
SWEDE CREEK 17.0
END DESCRIPTION:
XS GIS Cut Line= 3
      2099775.01     13863274.99      2099925.00     13863125.00
      2100189.36     13862926.00
#Sta/Elev= 30
  4788.0 1190.14  4791.5 1190.14  4816.3 1185.99  4844.6 1172.74  4872.8 1163.42
  4887.0 1160.72  4915.3 1158.42  4929.4 1155.45  4957.7 1133.11  4971.8 1125.92
  4986.0 1123.63  5000.0 1122.82  5000.5 1122.32  5014.9 1122.82  5028.2 1126.09
  5036.5 1126.19  5042.8 1125.31  5086.5 1125.04  5092.8 1125.40  5102.9 1128.11
  5107.4 1129.00  5128.2 1136.44  5157.3 1149.92  5163.6 1151.16  5171.9 1151.85
  5178.2 1153.27  5186.5 1153.16  5192.7 1154.07  5278.4 1156.01  5331.0 1156.31
#Mann=5,-1,0
  4788.0   0.035       0  5000.0   0.035       0  5014.9   0.035       0
  5102.9    0.12       0  5278.4    0.07       0
Bank Sta=5000,5014.9
Exp/Cntr=0.3,0.1