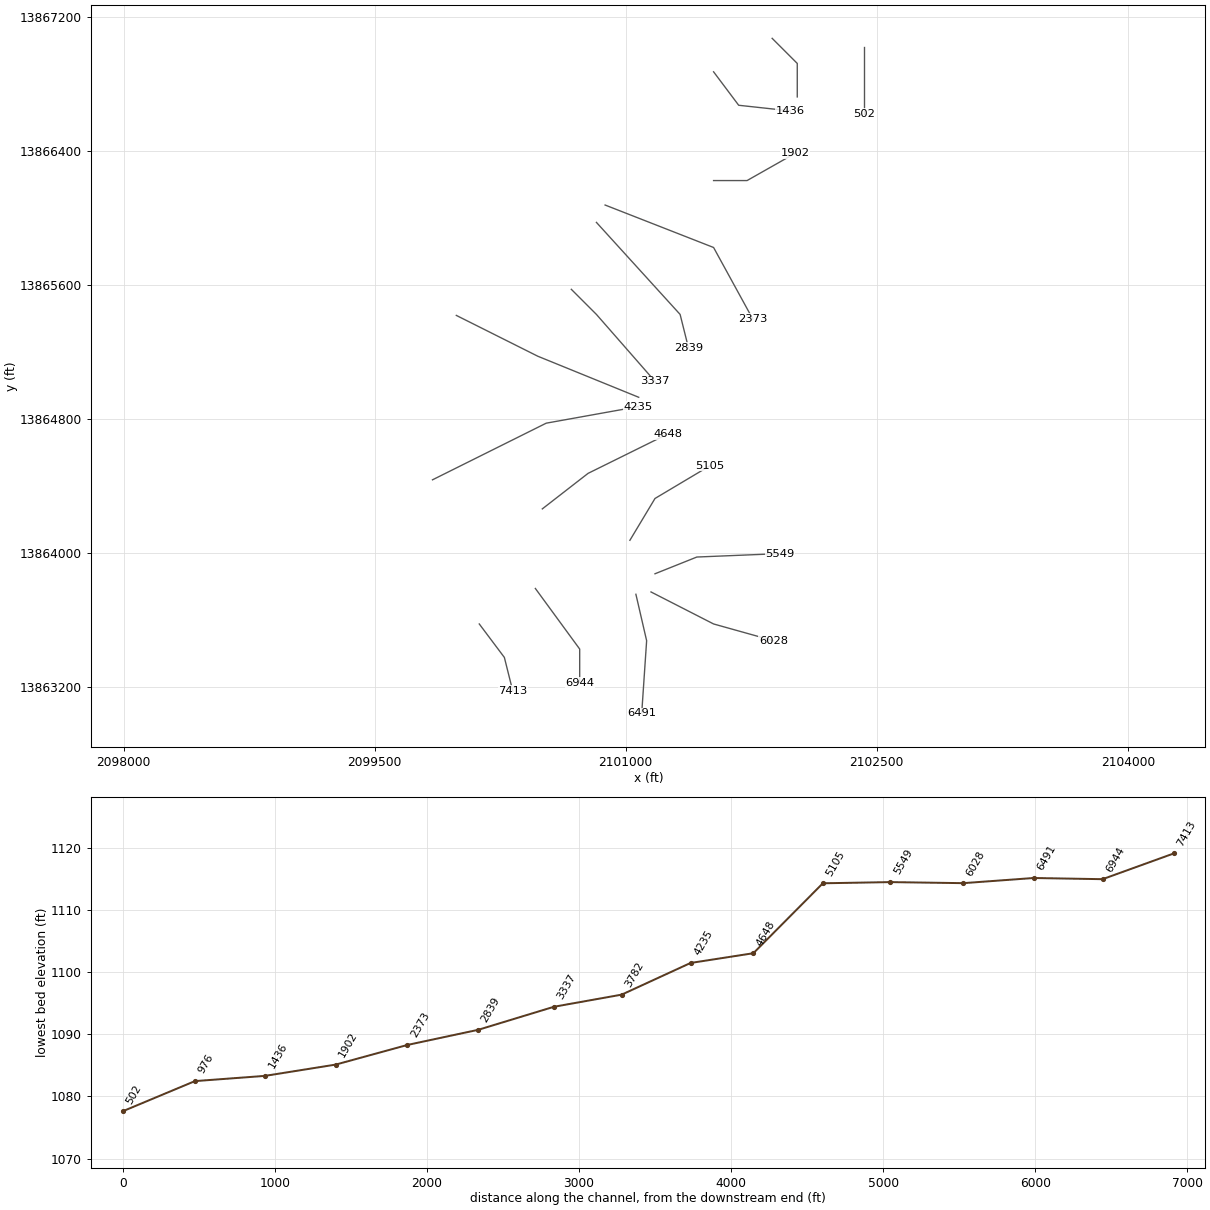
HEC-RAS study SWEDE CREEK.prj: SWEDE CREEK Base Level Engineering

--- SWEDE CREEK.g01 (geometry) --- (continued)

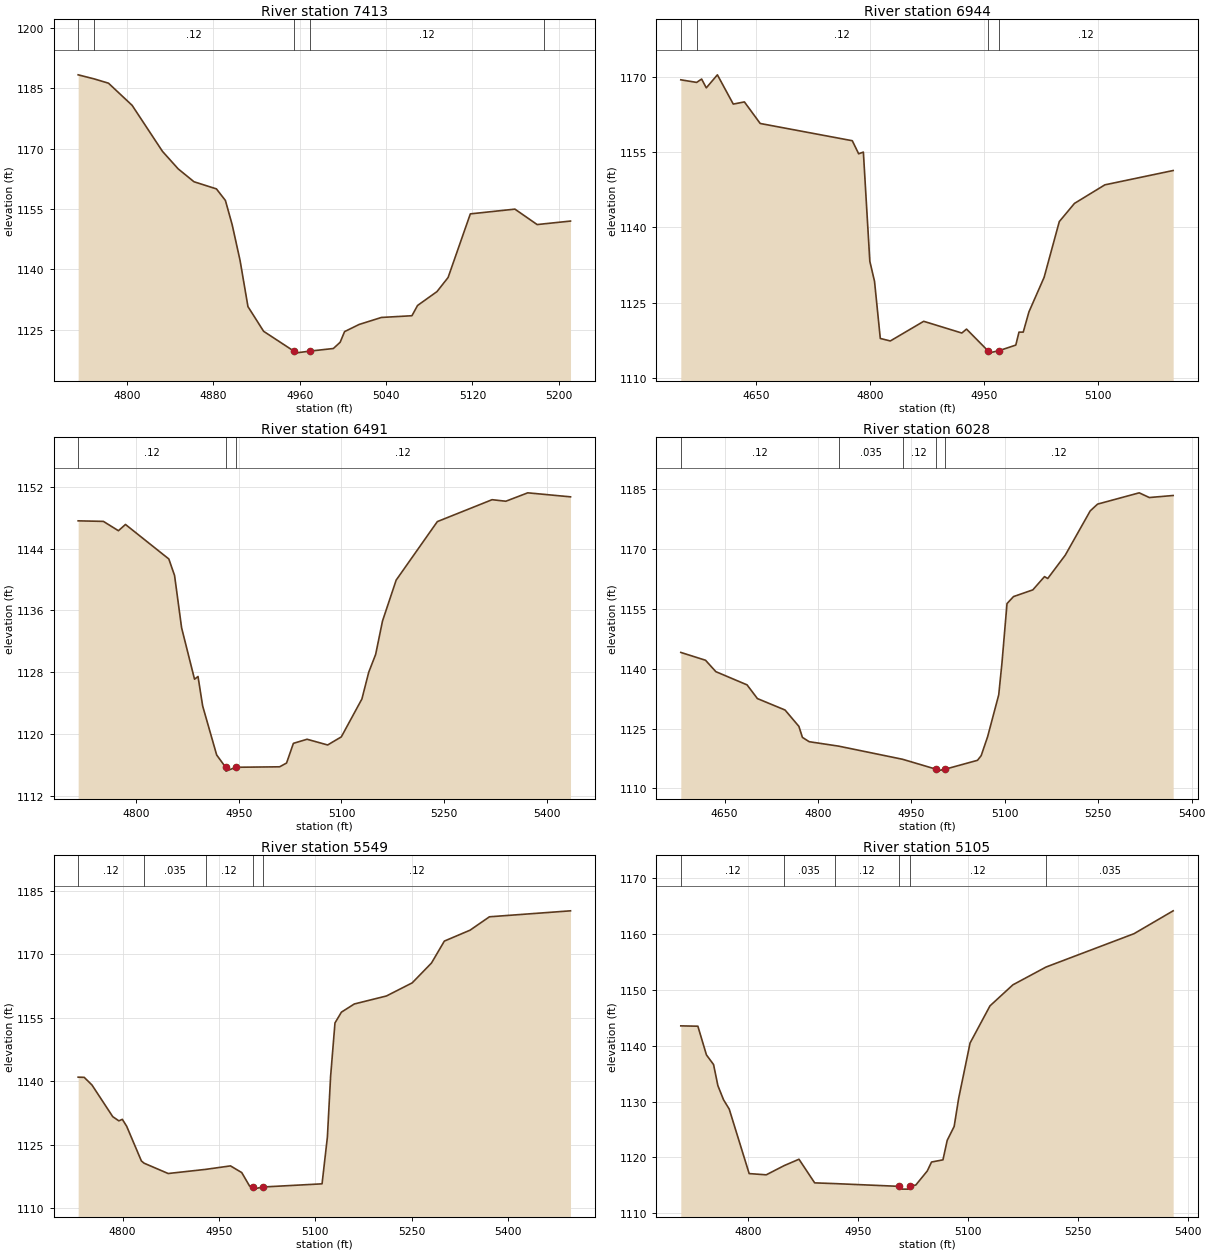
Type RM Length L Ch R = 1,7413,469,469,469
BEGIN DESCRIPTION:
SWEDE CREEK 16.0
END DESCRIPTION:
XS GIS Cut Line= 3
      2100125.02     13863574.97      2100275.00     13863375.00
      2100325.00     13863175.02
#Sta/Elev= 30
  4754.8 1188.34  4769.6 1187.33  4782.9 1186.26  4804.8 1180.75  4832.9 1169.31
  4847.5 1164.94  4862.1 1161.75  4882.9 1159.97  4891.2 1157.10  4897.5 1151.04
  4904.8 1142.16  4912.1 1130.70  4926.6 1124.56  4954.6 1119.63  4955.1 1119.13
  4969.5 1119.63  4991.2 1120.28  4997.5 1121.83  5001.6 1124.48  5015.1 1126.26
  5035.7 1128.00  5064.0 1128.43  5069.2 1130.98  5087.2 1134.43  5097.5 1137.94
  5118.1 1153.76  5159.4 1154.94  5180.0 1151.10  5185.9 1151.27  5210.9 1151.97
#Mann=5,-1,0
  4754.8   0.035       0  4769.6    0.12       0  4954.6    0.05       0
  4969.5    0.12       0  5185.9   0.035       0
Bank Sta=4954.6,4969.5
Exp/Cntr=0.3,0.1

Type RM Length L Ch R = 1,6944,453,453,453
BEGIN DESCRIPTION:
SWEDE CREEK 15.0
END DESCRIPTION:
XS GIS Cut Line= 3
      2100460.19     13863787.10      2100725.00     13863425.00
      2100725.00     13863225.00
#Sta/Elev= 30
  4551.0 1169.36  4571.9 1168.84  4578.4 1169.51  4584.6 1167.76  4599.2 1170.35
  4620.1 1164.53  4634.8 1164.96  4655.6 1160.67  4776.9 1157.24  4785.3 1154.64
  4791.5 1154.98  4800.0 1133.26  4806.2 1129.26  4813.8 1117.90  4827.0 1117.40
  4871.0 1121.31  4921.2 1118.98  4927.4 1119.76  4955.4 1115.48  4955.9 1114.98
  4970.4 1115.48  4992.3 1116.58  4996.5 1119.16  5002.1 1119.16  5009.6 1123.18
  5029.6 1130.06  5049.6 1141.15  5069.6 1144.77  5109.6 1148.46  5199.6 1151.31
#Mann=4,-1,0
  4551.0    0.07       0  4571.9    0.12       0  4955.4    0.05       0
  4970.4    0.12       0
Bank Sta=4955.4,4970.4
Exp/Cntr=0.3,0.1

Type RM Length L Ch R = 1,6491,463,463,463
BEGIN DESCRIPTION:
SWEDE CREEK 14.0
END DESCRIPTION:
XS GIS Cut Line= 3
      2101060.86     13863752.40      2101125.00     13863475.00
      2101095.58     13863040.61
#Sta/Elev= 30
  4714.9 1147.60  4751.8 1147.53  4773.8 1146.32  4784.1 1147.13  4847.5 1142.66
  4855.9 1140.52  4866.2 1133.74  4885.1 1127.08  4890.2 1127.43  4897.0 1123.61
  4917.5 1117.26  4930.6 1115.67  4931.1 1115.17  4945.6 1115.67  5009.6 1115.73
  5019.7 1116.22  5029.7 1118.77  5049.7 1119.30  5079.8 1118.56  5099.8 1119.61
  5129.9 1124.52  5139.9 1127.99  5150.0 1130.29  5160.0 1134.61  5180.0 1139.92
  5240.2 1147.50  5320.3 1150.34  5340.4 1150.14  5372.5 1151.23  5435.0 1150.71
#Mann=3,-1,0
  4714.9    0.12       0  4930.6    0.05       0  4945.6    0.12       0
Bank Sta=4930.6,4945.6
Exp/Cntr=0.3,0.1

Type RM Length L Ch R = 1,6028,479,479,479
BEGIN DESCRIPTION:
SWEDE CREEK 13.0
END DESCRIPTION:
XS GIS Cut Line= 3
      2101151.13     13863766.30      2101525.00     13863575.00
      2101881.92     13863475.15
#Sta/Elev= 30
  4579.7 1144.08  4619.4 1142.12  4636.0 1139.26  4686.1 1135.95  4702.7 1132.52
  4747.1 1129.65  4769.3 1125.56  4775.0 1122.79  4785.9 1121.71  4833.2 1120.60
  4935.8 1117.31  4989.2 1114.84  4989.7 1114.34  5004.6 1114.84  5056.1 1117.05
  5062.0 1118.21  5072.4 1122.98  5090.2 1133.45  5095.4 1141.45  5103.5 1156.32
  5113.9 1158.07  5145.0 1159.76  5163.7 1163.08  5168.9 1162.60  5197.0 1168.44
  5237.1 1179.54  5248.9 1181.24  5315.8 1184.07  5332.0 1182.89  5370.3 1183.40
#Mann=5,-1,0
  4579.7    0.12       0  4833.2   0.035       0  4935.8    0.12       0
  4989.2    0.05       0  5004.6    0.12       0
Bank Sta=4989.2,5004.6
Exp/Cntr=0.3,0.1

Type RM Length L Ch R = 1,5549,444,444,444
BEGIN DESCRIPTION:
SWEDE CREEK 12.0
END DESCRIPTION:
XS GIS Cut Line= 3
      2101175.01     13863875.00      2101425.00     13863975.00
      2101921.03     13863995.43
#Sta/Elev= 30
  4731.0 1140.96  4740.4 1140.92  4752.5 1139.11  4784.8 1131.63  4794.3 1130.64
  4799.7 1131.00  4806.4 1129.38  4829.3 1121.18  4833.5 1120.64  4871.0 1118.20
  4929.5 1119.18  4967.9 1120.00  4985.4 1118.42  4997.6 1115.24  5002.6 1115.01
  5003.1 1114.51  5018.0 1115.01  5110.3 1115.76  5118.6 1126.80  5123.6 1141.14
  5130.4 1153.77  5140.4 1156.32  5160.4 1158.25  5210.4 1160.14  5250.5 1163.24
  5280.5 1167.93  5300.5 1173.11  5340.5 1175.69  5370.6 1178.85  5496.7 1180.26
#Mann=5,-1,0
  4731.0    0.12       0  4833.5   0.035       0  4929.5    0.12       0
  5002.6    0.05       0  5018.0    0.12       0
Bank Sta=5002.6,5018
Exp/Cntr=0.3,0.1

Type RM Length L Ch R = 1,5105,457,457,457
BEGIN DESCRIPTION:
SWEDE CREEK 11.0
END DESCRIPTION:
XS GIS Cut Line= 3
      2101024.99     13864074.99      2101175.00     13864325.00
      2101501.81     13864519.76
#Sta/Elev= 30
  4708.4 1143.54  4731.7 1143.48  4743.4 1138.34  4753.1 1136.62  4759.0 1132.85
  4766.7 1130.32  4774.5 1128.64  4801.7 1117.10  4825.0 1116.88  4849.5 1118.53
  4869.7 1119.67  4891.1 1115.44  4918.3 1115.31  5005.9 1114.82  5006.4 1114.32
  5020.8 1114.32  5021.3 1114.82  5029.2 1115.06  5044.8 1117.57  5050.6 1119.17
  5066.2 1119.56  5072.0 1123.05  5081.5 1125.54  5087.6 1130.54  5103.2 1140.47
  5130.4 1147.12  5161.6 1150.88  5206.9 1154.07  5327.0 1160.04  5380.4 1164.13
#Mann=6,-1,0
  4708.4    0.12       0  4849.5   0.035       0  4918.3    0.12       0
  5005.9    0.05       0  5021.3    0.12       0  5206.9   0.035       0
Bank Sta=5005.9,5021.3
Exp/Cntr=0.3,0.1

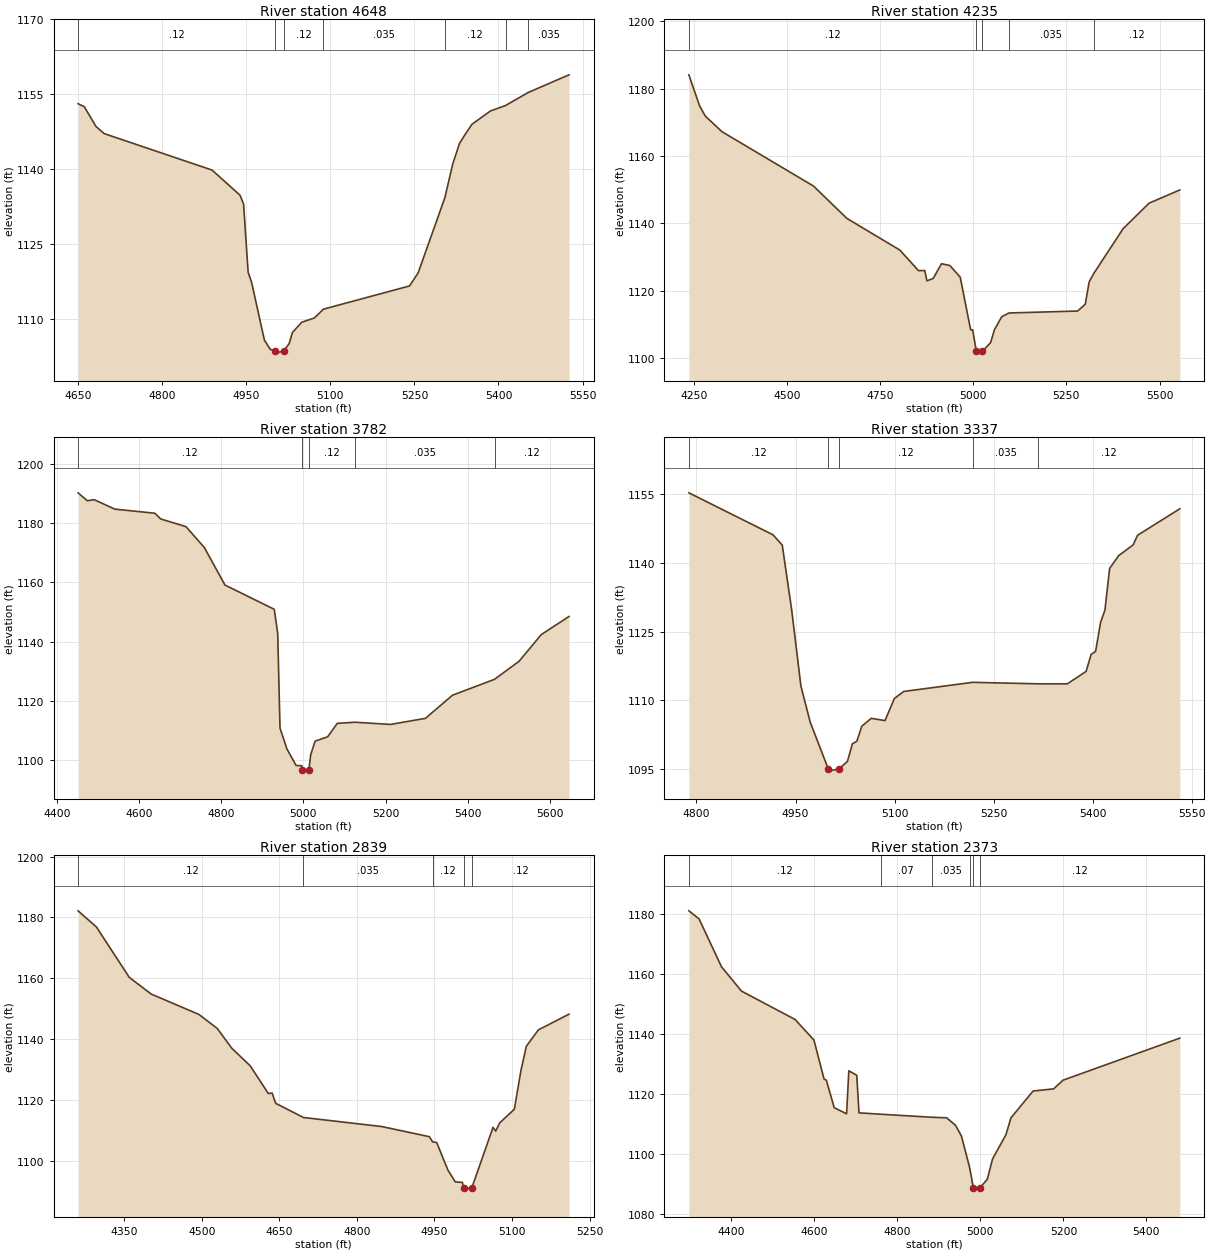
Type RM Length L Ch R = 1,4648,413,413,413
BEGIN DESCRIPTION:
SWEDE CREEK 10.0
END DESCRIPTION:
XS GIS Cut Line= 3
      2100501.79     13864262.80      2100775.00     13864475.00
      2101250.16     13864709.92
#Sta/Elev= 30
  4649.9 1153.08  4661.0 1152.48  4681.8 1148.52  4696.3 1147.09  4889.0 1139.77
  4938.8 1134.73  4945.2 1132.98  4953.3 1119.31  4959.6 1117.22  4982.3 1105.70
  4992.7 1103.82  5002.1 1103.56  5002.6 1103.06  5017.6 1103.56  5026.7 1105.01
  5032.3 1107.19  5049.1 1109.26  5071.6 1110.11  5087.8 1111.88  5241.3 1116.53
  5256.7 1119.15  5304.4 1134.24  5318.4 1140.97  5330.5 1145.12  5340.8 1146.96
  5352.8 1148.96  5385.7 1151.62  5412.6 1152.71  5453.0 1155.32  5525.9 1158.87
#Mann=7,-1,0
  4649.9    0.12       0  5002.1    0.05       0  5017.6    0.12       0
  5087.8   0.035       0  5304.4    0.12       0  5412.6    0.07       0
  5453.0   0.035       0
Bank Sta=5002.1,5017.6
Exp/Cntr=0.3,0.1

Type RM Length L Ch R = 1,4235,453,453,453
BEGIN DESCRIPTION:
SWEDE CREEK 9.0
END DESCRIPTION:
XS GIS Cut Line= 3
      2099845.55     13864436.43      2100525.00     13864775.00
      2101074.74     13864873.94
#Sta/Elev= 30
  4236.8 1184.06  4265.7 1174.80  4280.9 1171.82  4325.6 1167.19  4571.4 1151.05
  4660.7 1141.48  4802.9 1132.08  4853.2 1125.96  4870.0 1126.00  4875.6 1122.95
  4892.4 1123.62  4914.8 1128.01  4937.2 1127.49  4965.1 1124.04  4993.1 1108.40
  4998.5 1108.40  5008.5 1101.99  5009.0 1101.49  5024.0 1101.99  5046.7 1104.60
  5056.9 1108.43  5076.4 1112.27  5095.8 1113.40  5280.4 1113.98  5300.8 1116.01
  5311.2 1122.61  5323.8 1125.16  5402.4 1138.42  5472.1 1145.99  5554.5 1149.90
#Mann=5,-1,0
  4236.8    0.12       0  5008.5    0.05       0  5024.0    0.12       0
  5095.8   0.035       0  5323.8    0.12       0
Bank Sta=5008.5,5024
Exp/Cntr=0.3,0.1

Type RM Length L Ch R = 1,3782,445,445,445
BEGIN DESCRIPTION:
SWEDE CREEK 8.0
END DESCRIPTION:
XS GIS Cut Line= 3
      2099987.94     13865419.08      2100475.00     13865175.00
      2101077.61     13864929.74
#Sta/Elev= 30
  4451.3 1190.14  4473.8 1187.48  4490.5 1187.83  4540.8 1184.65  4638.2 1183.26
  4652.5 1181.34  4714.0 1178.75  4758.7 1171.72  4808.9 1159.08  4929.0 1150.90
  4937.4 1142.78  4943.0 1110.89  4959.8 1103.89  4982.1 1098.30  4996.1 1098.20
  4997.3 1096.89  4997.8 1096.39  5013.5 1096.89  5017.7 1101.93  5028.5 1106.50
  5058.9 1107.94  5082.5 1112.49  5125.9 1112.86  5212.0 1112.12  5297.1 1114.17
  5363.2 1121.98  5465.3 1127.31  5525.1 1133.39  5579.1 1142.37  5646.7 1148.49
#Mann=5,-1,0
  4451.3    0.12       0  4997.3    0.05       0  5013.5    0.12       0
  5125.9   0.035       0  5465.3    0.12       0
Bank Sta=4997.3,5013.5
Exp/Cntr=0.3,0.1

Type RM Length L Ch R = 1,3337,498,498,498
BEGIN DESCRIPTION:
SWEDE CREEK 7.0
END DESCRIPTION:
XS GIS Cut Line= 3
      2100675.01     13865574.99      2100825.00     13865425.00
      2101174.98     13865025.02
#Sta/Elev= 30
  4788.5 1155.36  4915.8 1146.18  4929.9 1143.94  4944.1 1129.84  4958.2 1113.06
  4972.3 1105.14  4999.6 1094.94  5000.1 1094.44  5015.8 1094.94  5028.6 1096.55
  5036.2 1100.43  5042.9 1100.98  5050.4 1104.27  5064.7 1106.00  5085.6 1105.50
  5099.8 1110.35  5114.0 1111.88  5218.2 1113.88  5317.8 1113.55  5361.8 1113.55
  5390.2 1116.27  5397.8 1119.99  5404.5 1120.64  5412.1 1126.97  5418.7 1129.69
  5425.8 1138.82  5439.6 1141.62  5461.4 1143.96  5468.1 1146.07  5532.1 1151.87
#Mann=5,-1,0
  4788.5    0.12       0  4999.6    0.05       0  5015.8    0.12       0
  5218.2   0.035       0  5317.8    0.12       0
Bank Sta=4999.6,5015.8
Exp/Cntr=0.3,0.1

Type RM Length L Ch R = 1,2839,466,466,466
BEGIN DESCRIPTION:
SWEDE CREEK 6.0
END DESCRIPTION:
XS GIS Cut Line= 3
      2100825.00     13865975.00      2101325.00     13865425.00
      2101375.01     13865224.97
#Sta/Elev= 30
  4260.7 1182.19  4296.2 1176.88  4359.7 1160.32  4402.3 1154.82  4494.2 1148.16
  4530.0 1143.52  4558.0 1137.03  4593.5 1131.28  4628.6 1122.16  4636.1 1122.30
  4642.8 1118.93  4696.4 1114.28  4848.3 1111.29  4940.2 1107.96  4946.2 1106.28
  4954.3 1106.05  4976.0 1096.99  4990.2 1093.11  5004.0 1092.94  5006.2 1091.23
  5006.7 1090.73  5022.4 1091.23  5063.3 1111.05  5068.4 1109.78  5076.2 1112.51
  5104.5 1116.98  5117.4 1129.85  5127.7 1137.68  5150.9 1143.06  5210.2 1148.23
#Mann=5,-1,0
  4260.7    0.12       0  4696.4   0.035       0  4946.2    0.12       0
  5006.2    0.05       0  5022.4    0.12       0
Bank Sta=5006.2,5022.4
Exp/Cntr=0.3,0.1

Type RM Length L Ch R = 1,2373,471,471,471
BEGIN DESCRIPTION:
SWEDE CREEK 5.0
END DESCRIPTION:
XS GIS Cut Line= 3
      2100876.87     13866078.78      2101525.00     13865825.00
      2101758.76     13865398.27
#Sta/Elev= 30
  4297.8 1181.10  4322.3 1178.42  4376.5 1162.41  4424.7 1154.31  4553.5 1144.88
  4599.0 1138.01  4623.5 1124.96  4628.8 1124.67  4647.9 1115.45  4677.7 1113.41
  4683.1 1127.76  4702.2 1126.25  4707.6 1113.73  4759.9 1113.27  4882.9 1112.26
  4918.7 1112.08  4940.1 1109.57  4954.5 1105.93  4974.2 1095.44  4983.0 1088.79
  4983.5 1088.29  4999.3 1088.79  5016.6 1091.56  5029.4 1098.39  5061.6 1106.43
  5073.7 1112.08  5127.1 1121.02  5176.4 1121.72  5199.1 1124.62  5480.4 1138.64
#Mann=6,-1,0
  4297.8    0.12       0  4759.9    0.07       0  4882.9   0.035       0
  4974.2    0.12       0  4983.0    0.05       0  4999.3    0.12       0
Bank Sta=4983,4999.3
Exp/Cntr=0.3,0.1

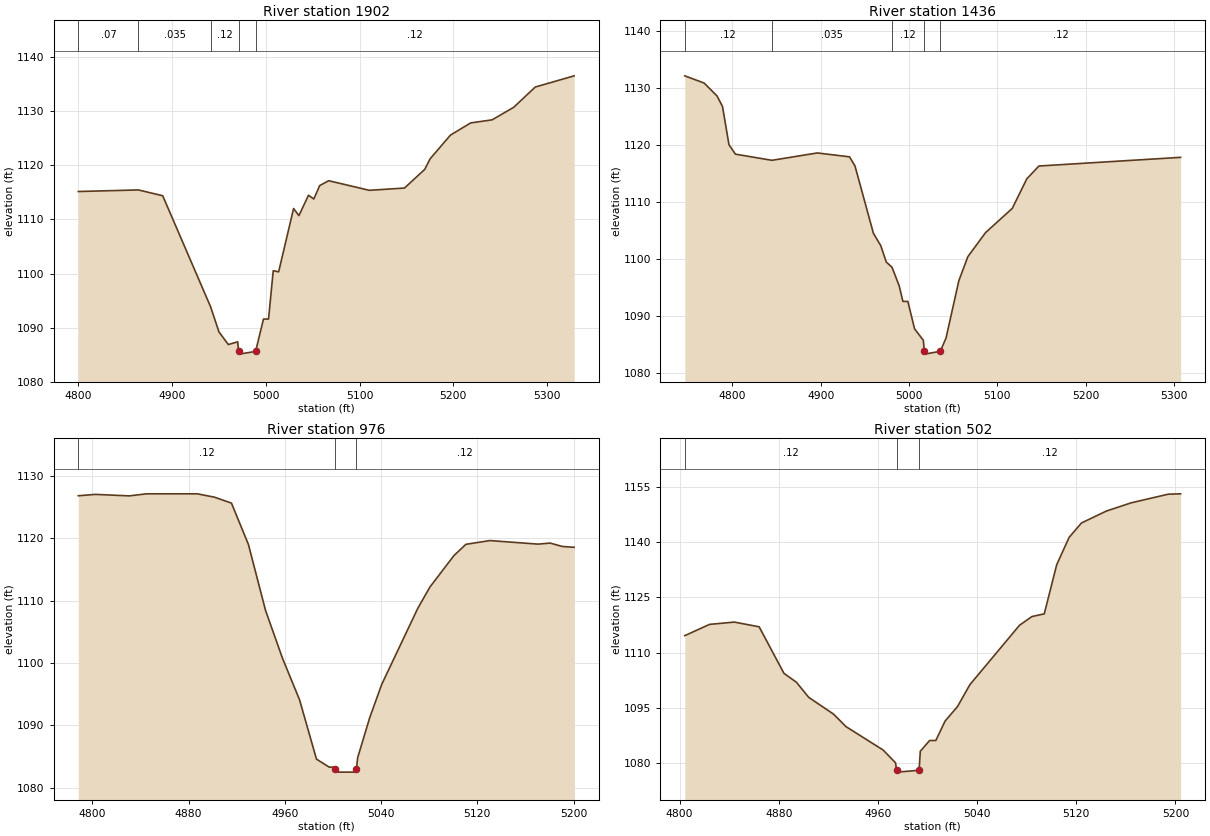
Type RM Length L Ch R = 1,1902,466,466,466
BEGIN DESCRIPTION:
SWEDE CREEK 4.0
END DESCRIPTION:
XS GIS Cut Line= 3
      2101525.00     13866225.00      2101725.00     13866225.00
      2102011.13     13866387.19
#Sta/Elev= 30
  4800.0 1115.13  4864.1 1115.42  4890.0 1114.35  4941.1 1093.86  4950.0 1089.23
  4960.0 1086.90  4970.0 1087.40  4971.0 1085.63  4971.5 1085.13  4989.1 1085.63
  4997.5 1091.60  5002.9 1091.60  5007.9 1100.51  5013.7 1100.32  5029.6 1111.99
  5035.3 1110.68  5045.5 1114.44  5051.2 1113.75  5057.5 1116.23  5067.1 1117.12
  5110.4 1115.35  5147.9 1115.77  5169.5 1119.21  5175.3 1121.17  5196.9 1125.53
  5218.5 1127.78  5241.4 1128.35  5264.4 1130.66  5287.4 1134.40  5328.9 1136.47
#Mann=5,-1,0
  4800.0    0.07       0  4864.1   0.035       0  4941.1    0.12       0
  4971.0    0.05       0  4989.1    0.12       0
Bank Sta=4971,4989.1
Exp/Cntr=0.3,0.1

Type RM Length L Ch R = 1,1436,460,460,460
BEGIN DESCRIPTION:
SWEDE CREEK 3.0
END DESCRIPTION:
XS GIS Cut Line= 3
      2101525.00     13866874.99      2101675.00     13866675.00
      2101984.48     13866641.30
#Sta/Elev= 30
  4746.1 1132.13  4768.0 1130.86  4782.6 1128.60  4788.8 1126.75  4796.1 1120.05
  4803.4 1118.39  4844.7 1117.31  4896.1 1118.60  4932.6 1117.92  4938.8 1116.30
  4959.6 1104.52  4968.0 1102.32  4974.2 1099.46  4980.7 1098.55  4988.8 1095.30
  4993.0 1092.56  4998.6 1092.56  5006.2 1087.76  5016.2 1085.72  5017.2 1083.81
  5017.7 1083.31  5035.3 1083.81  5041.8 1086.12  5056.4 1096.22  5066.5 1100.40
  5086.6 1104.63  5116.8 1108.87  5133.3 1114.07  5147.0 1116.31  5307.4 1117.83
#Mann=5,-1,0
  4746.1    0.12       0  4844.7   0.035       0  4980.7    0.12       0
  5017.2    0.05       0  5035.3    0.12       0
Bank Sta=5017.2,5035.3
Exp/Cntr=0.3,0.1

Type RM Length L Ch R = 1,976,474,474,474
BEGIN DESCRIPTION:
SWEDE CREEK 2.0
END DESCRIPTION:
XS GIS Cut Line= 3
      2101874.98     13867075.02      2102025.00     13866925.00
      2102025.00     13866724.96
#Sta/Elev= 30
  4788.3 1126.81  4802.5 1127.03  4830.7 1126.79  4844.9 1127.12  4887.3 1127.12
  4901.5 1126.58  4915.6 1125.63  4929.7 1119.00  4943.9 1108.44  4958.0 1100.75
  4972.2 1094.08  4986.3 1084.55  4996.9 1083.27  5000.5 1083.27  5001.4 1082.97
  5001.9 1082.47  5019.0 1082.47  5019.5 1082.97  5020.5 1084.77  5030.5 1091.18
  5040.5 1096.54  5070.5 1108.75  5080.5 1112.14  5100.5 1117.20  5110.5 1119.02
  5130.5 1119.62  5170.5 1119.05  5180.5 1119.22  5190.5 1118.68  5200.5 1118.54
#Mann=3,-1,0
  4788.3    0.12       0  5001.4    0.05       0  5019.5    0.12       0
Bank Sta=5001.4,5019.5
Exp/Cntr=0.3,0.1

Type RM Length L Ch R = 1,502,0,0,0
BEGIN DESCRIPTION:
SWEDE CREEK 1.0
END DESCRIPTION:
XS GIS Cut Line= 3
      2102425.00     13867025.00      2102425.00     13866825.00
      2102425.00     13866625.00
#Sta/Elev= 30
  4804.2 1114.60  4824.2 1117.65  4844.2 1118.27  4864.2 1116.99  4884.2 1104.38
  4894.2 1101.99  4904.2 1097.87  4924.2 1093.34  4934.2 1089.96  4964.2 1083.61
  4974.2 1080.15  4975.1 1078.12  4975.6 1077.62  4993.2 1078.12  4994.2 1083.28
  5001.7 1086.19  5006.7 1086.19  5014.2 1091.46  5024.2 1095.38  5034.2 1101.32
  5074.2 1117.40  5084.2 1119.77  5094.2 1120.50  5104.2 1133.78  5114.2 1141.20
  5124.2 1145.12  5144.2 1148.34  5164.2 1150.57  5194.2 1152.92  5204.2 1153.02
#Mann=3,-1,0
  4804.2    0.12       0  4975.1    0.05       0  4993.2    0.12       0
Bank Sta=4975.1,4993.2
Exp/Cntr=0.3,0.1

Chan Stop Cuts=-1