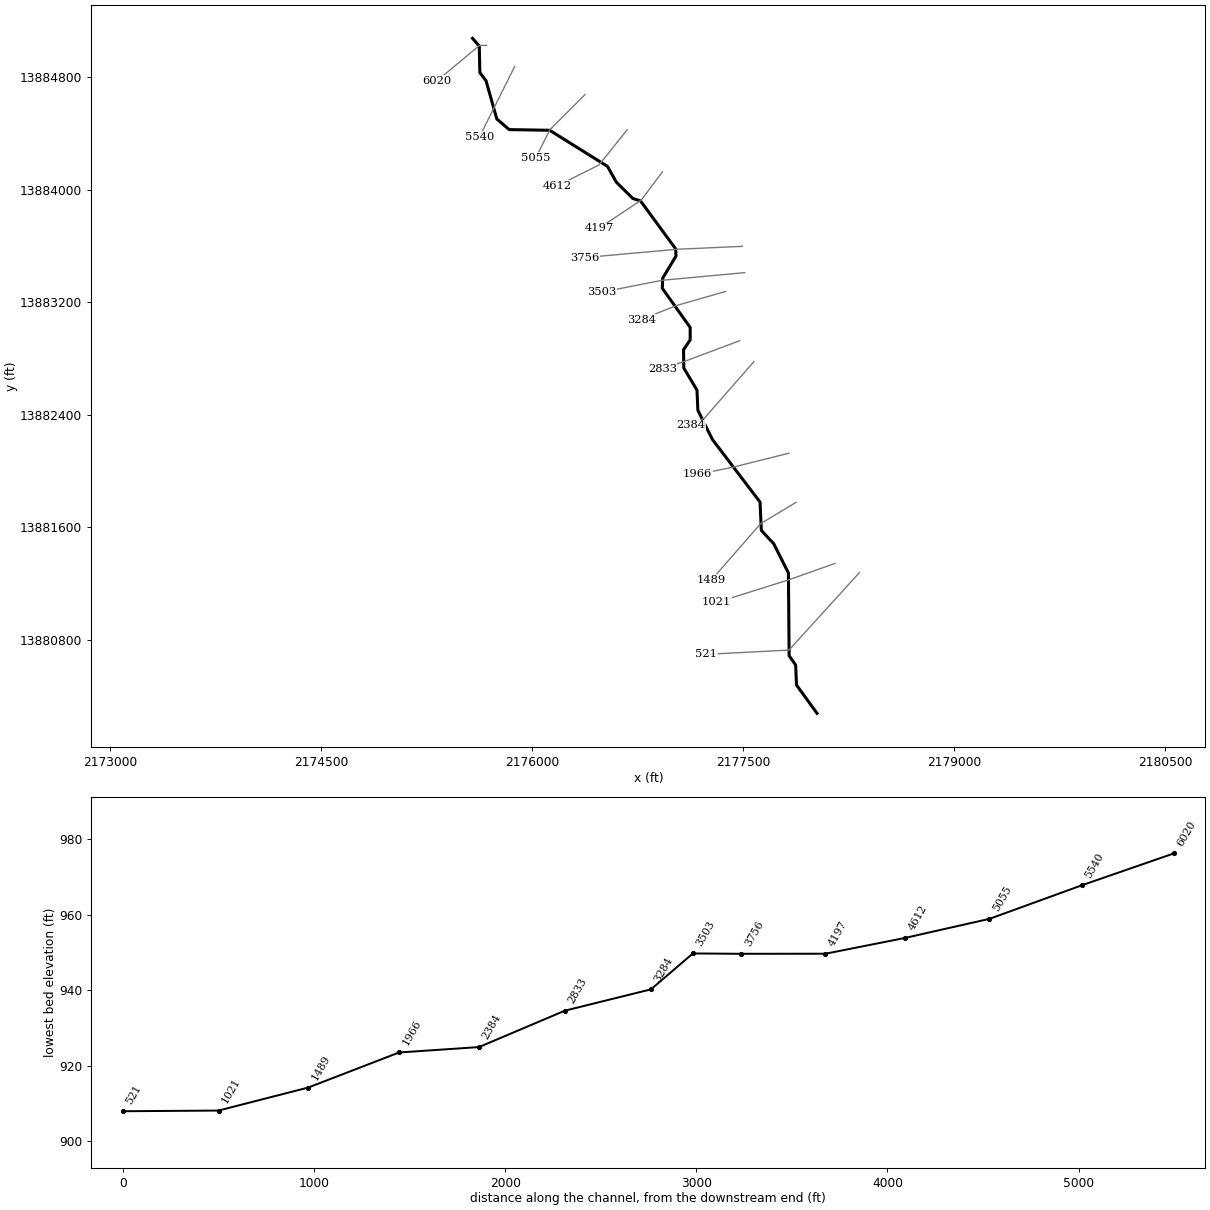
--- Schultz Creek.prj (project) ---

Proj Title=Schultz Creek Base Level Engineering
Current Plan=p01
Default Exp/Contr=0.3,0.1
English Units
Geom File=g01
Flow File=f01
Plan File=p01
BEGIN DESCRIPTION:
Schultz Creek
END DESCRIPTION:

--- Schultz Creek.p01 (plan) ---

Plan Title=Multiple Run
Short Identifier=Multiple
Geom File=g01
Flow File=f01
Subcritical Flow
K Sum by GR= 0
Std Step Tol= 0.01
Critical Tol= 0.01
Num of Std Step Trials= 20
Max Error Tol= 0.3
Flow Tol Ratio= 0.001
Split Flow NTrial= 30
Split Flow Tol= 0.02
Split Flow Ratio= 0.02
Log Output Level= 0
Friction Slope Method= 1
Unsteady Friction Slope Method= 2
Unsteady Bridges Friction Slope Method= 1
Parabolic Critical Depth
Global Vel Dist=  1 , 1 , 1
Global Log Level= 0
CheckData=True
Encroach Param= -1, 0, 0, 0
BEGIN DESCRIPTION:
Multiple Run
END DESCRIPTION:

--- Schultz Creek.f01 (steady flow) ---

Flow Title=Multiple
Number of Profiles=7
Profile Names=10-year,25-year,50-year,1pct_min,100-year,1pct_plu,500-year
River Rch & RM= Schultz Creek,Reach-1,6020
    1135    1941    2714    1841    3673    7329    6653
River Rch & RM= Schultz Creek,Reach-1,5540
    1689    2951    4186    2875    5737   11447   10666
River Rch & RM= Schultz Creek,Reach-1,3756
    1738    3041    4317    2966    5917   11806   11010
Boundary for River Rch & Prof#=Schultz Creek,Reach-1,1
Up Type=0
Dn Type=3
Dn Slope=0.005
Boundary for River Rch & Prof#=Schultz Creek,Reach-1,2
Up Type=0
Dn Type=3
Dn Slope=0.005
Boundary for River Rch & Prof#=Schultz Creek,Reach-1,3
Up Type=0
Dn Type=3
Dn Slope=0.005
Boundary for River Rch & Prof#=Schultz Creek,Reach-1,4
Up Type=0
Dn Type=3
Dn Slope=0.005
Boundary for River Rch & Prof#=Schultz Creek,Reach-1,5
Up Type=0
Dn Type=3
Dn Slope=0.005
Boundary for River Rch & Prof#=Schultz Creek,Reach-1,6
Up Type=0
Dn Type=3
Dn Slope=0.005
Boundary for River Rch & Prof#=Schultz Creek,Reach-1,7
Up Type=0
Dn Type=3
Dn Slope=0.005

--- Schultz Creek.g01 (geometry) ---

Geom Title=Existing Conditions

River Reach=Schultz Creek,Reach-1
Reach XY= 30
      2175575.00     13885075.00      2175623.00     13885019.63
      2175627.26     13884830.94      2175671.14     13884773.40
      2175747.85     13884501.42      2175835.43     13884426.04
      2176123.45     13884421.25      2176535.00     13884164.35
      2176598.02     13884051.54      2176715.58     13883935.89
      2176769.38     13883919.38      2177019.90     13883577.29
      2177021.69     13883526.74      2176927.14     13883369.03
      2176924.62     13883297.72      2177122.86     13883019.03
      2177122.83     13882930.98      2177075.67     13882861.07
      2177077.23     13882730.93      2177171.24     13882573.44
      2177177.36     13882430.52      2177280.85     13882222.71
      2177619.53     13881777.45      2177628.55     13881576.47
      2177716.84     13881481.05      2177821.25     13881273.45
      2177826.38     13880684.66      2177872.73     13880619.06
      2177878.76     13880476.56      2178025.00     13880275.00

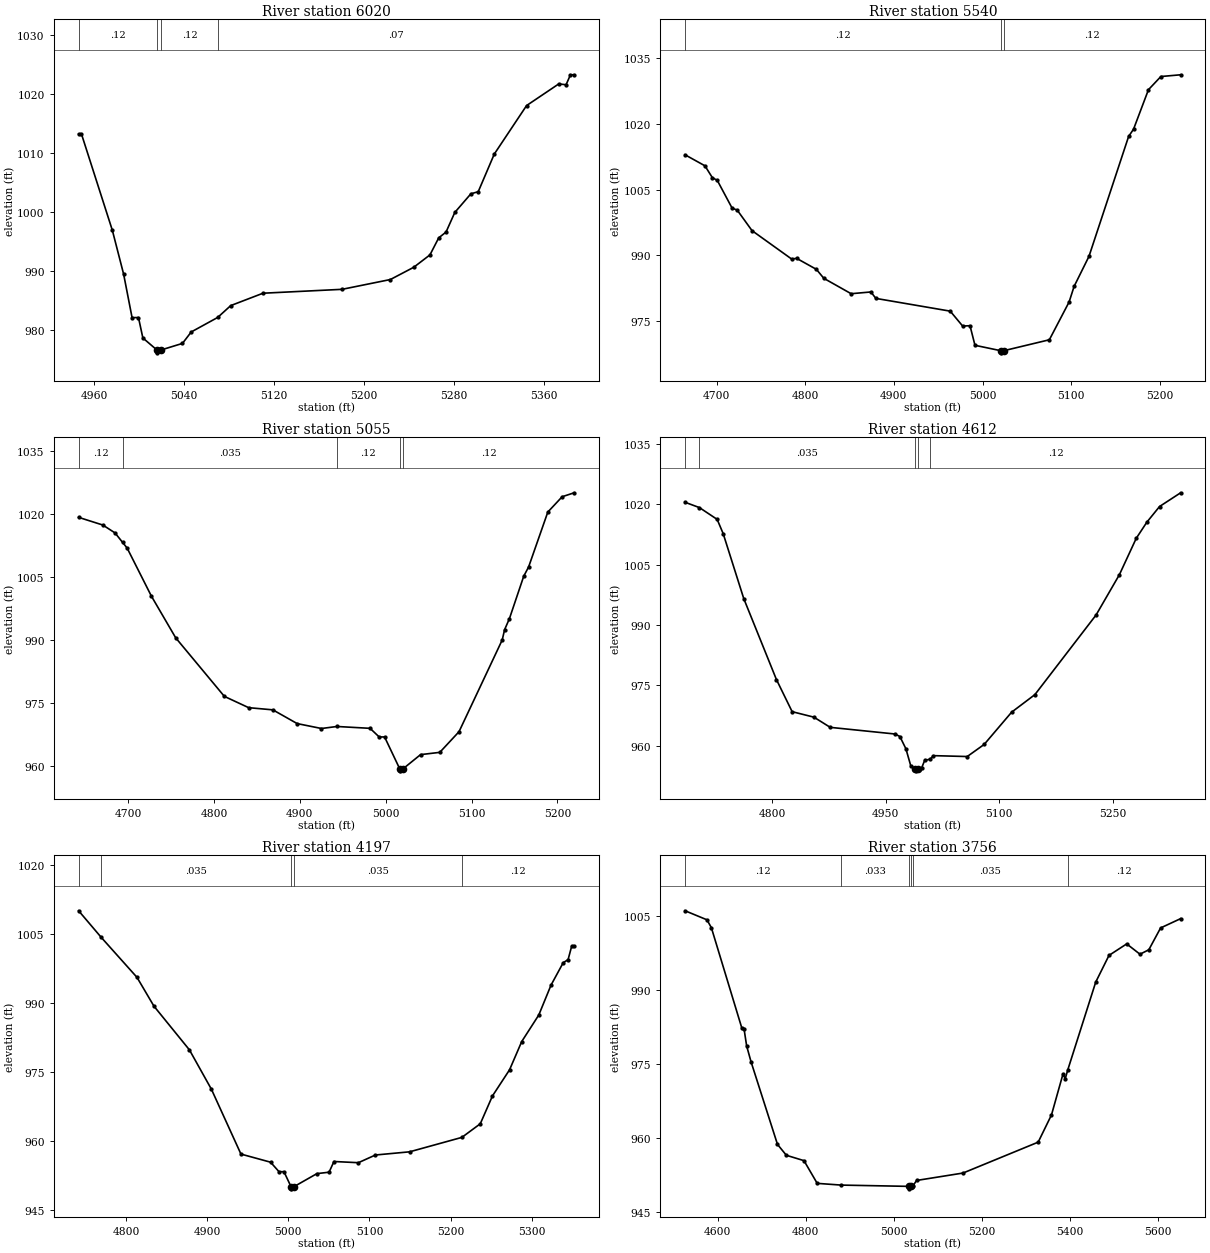
Type RM Length L Ch R = 1,6020,480,480,480
BEGIN DESCRIPTION:
Schultz Creek 13.0
END DESCRIPTION:
XS GIS Cut Line= 3
      2175674.97     13885025.00      2175625.00     13885025.00
      2175324.99     13884774.99
#Sta/Elev= 30
  4946.2 1013.30  4948.7 1013.30  4976.2  996.94  4986.2  989.52  4993.7  982.16
  4999.4  982.16  5003.3  978.70  5015.7  976.68  5015.9  976.18  5019.7  976.68
  5038.5  977.78  5046.3  979.72  5069.8  982.18  5081.4  984.19  5110.1  986.29
  5180.4  986.95  5223.3  988.61  5244.1  990.69  5258.5  992.79  5266.3  995.68
  5272.8  996.66  5280.6  999.99  5294.9 1003.15  5301.4 1003.50  5315.7 1009.89
  5344.4 1018.11  5373.0 1021.78  5379.5 1021.64  5383.4 1023.33  5386.7 1023.33
#Mann=4,-1,0
  4946.2    0.12       0  5015.7    0.05       0  5019.7    0.12       0
  5069.8    0.07       0
Bank Sta=5015.7,5019.7
Exp/Cntr=0.3,0.1

Type RM Length L Ch R = 1,5540,485,485,485
BEGIN DESCRIPTION:
Schultz Creek 12.0
END DESCRIPTION:
XS GIS Cut Line= 3
      2175875.00     13884875.00      2175725.00     13884575.00
      2175625.01     13884375.02
#Sta/Elev= 30
  4664.5 1012.96  4686.9 1010.45  4695.2 1007.76  4700.8 1007.13  4717.6 1000.77
  4723.2 1000.37  4740.0  995.66  4784.7  989.18  4790.3  989.34  4812.6  986.83
  4821.0  984.78  4851.8  981.27  4874.1  981.67  4879.7  980.20  4963.6  977.29
  4977.6  973.89  4985.9  973.97  4991.5  969.50  5020.3  968.28  5020.5  967.78
  5024.3  968.28  5075.4  970.76  5097.7  979.39  5103.3  982.93  5120.1  989.79
  5164.8 1017.14  5170.4 1018.82  5187.2 1027.82  5201.2 1030.82  5223.5 1031.22
#Mann=3,-1,0
  4664.5    0.12       0  5020.3    0.05       0  5024.3    0.12       0
Bank Sta=5020.3,5024.3
Exp/Cntr=0.3,0.1

Type RM Length L Ch R = 1,5055,443,443,443
BEGIN DESCRIPTION:
Schultz Creek 11.0
END DESCRIPTION:
XS GIS Cut Line= 3
      2176374.97     13884674.97      2176125.00     13884425.00
      2176025.01     13884225.02
#Sta/Elev= 30
  4642.4 1019.22  4670.6 1017.39  4684.8 1015.51  4693.6 1013.26  4698.9 1011.90
  4727.2 1000.44  4755.5  990.52  4812.1  976.60  4840.4  973.91  4868.6  973.39
  4896.9  970.12  4925.2  968.95  4943.2  969.43  4981.8  968.99  4992.4  966.94
  4998.7  966.94  5016.3  959.37  5016.5  958.87  5020.3  959.37  5040.6  962.73
  5063.0  963.27  5085.4  968.19  5135.7  990.03  5138.5  992.49  5144.1  995.11
  5160.8 1005.23  5166.4 1007.39  5188.8 1020.48  5205.5 1024.13  5219.5 1025.07
#Mann=5,-1,0
  4642.4    0.12       0  4693.6   0.035       0  4943.2    0.12       0
  5016.3    0.05       0  5020.3    0.12       0
Bank Sta=5016.3,5020.3
Exp/Cntr=0.3,0.1

Type RM Length L Ch R = 1,4612,415,415,415
BEGIN DESCRIPTION:
Schultz Creek 10.0
END DESCRIPTION:
XS GIS Cut Line= 3
      2176674.97     13884424.96      2176475.00     13884175.00
      2176175.02     13884025.01
#Sta/Elev= 30
  4684.5 1020.45  4703.5 1019.13  4726.9 1016.21  4734.9 1012.66  4762.1  996.55
  4805.3  976.47  4826.1  968.49  4854.9  967.13  4876.5  964.60  4962.2  962.95
  4968.6  962.33  4976.6  959.28  4983.0  955.07  4989.0  954.31  4989.3  953.81
  4993.0  954.31  4997.4  954.54  5001.4  956.40  5008.9  956.72  5013.0  957.58
  5057.7  957.36  5080.1  960.36  5116.4  968.36  5147.2  972.72  5228.2  992.50
  5259.0 1002.49  5281.3 1011.52  5295.3 1015.51  5312.1 1019.40  5340.0 1022.81
#Mann=5,-1,0
  4684.5    0.12       0  4703.5   0.035       0  4989.0   0.035       0
  4993.0   0.035       0  5008.9    0.12       0
Bank Sta=4989,4993
Exp/Cntr=0.3,0.1

Type RM Length L Ch R = 1,4197,441,441,441
BEGIN DESCRIPTION:
Schultz Creek 9.0
END DESCRIPTION:
XS GIS Cut Line= 3
      2176925.03     13884125.03      2176775.00     13883925.00
      2176475.00     13883725.00
#Sta/Elev= 30
  4741.6 1009.97  4769.5 1004.19  4813.5  995.53  4834.4  989.28  4878.1  979.80
  4905.2  971.26  4941.6  957.19  4978.1  955.43  4988.5  953.37  4994.6  953.37
  5003.2  950.15  5003.4  949.65  5007.2  950.15  5035.2  952.95  5050.2  953.26
  5056.2  955.58  5086.3  955.32  5107.3  956.99  5149.4  957.68  5213.8  960.81
  5236.5  963.76  5251.5  969.80  5272.6  975.48  5287.6  981.61  5308.6  987.36
  5323.7  993.85  5338.7  998.71  5344.7  999.37  5349.2 1002.34  5352.2 1002.34
#Mann=5,-1,0
  4741.6    0.12       0  4769.5   0.035       0  5003.2   0.035       0
  5007.2   0.035       0  5213.8    0.12       0
Bank Sta=5003.2,5007.2
Exp/Cntr=0.3,0.1

Type RM Length L Ch R = 1,3756,253,253,253
BEGIN DESCRIPTION:
Schultz Creek 8.0
END DESCRIPTION:
XS GIS Cut Line= 3
      2177494.54     13883595.91      2177025.00     13883575.00
      2176373.06     13883516.05
#Sta/Elev= 30
  4526.2 1005.97  4575.8 1004.14  4585.8 1002.55  4655.0  982.19  4660.0  982.03
  4665.9  978.58  4675.9  975.36  4735.9  958.63  4756.0  956.43  4796.0  955.34
  4826.0  950.74  4880.4  950.39  5033.8  950.13  5034.2  949.63  5038.9  950.13
  5042.6  950.15  5051.6  951.33  5156.9  952.83  5327.5  959.09  5357.7  964.61
  5383.8  972.90  5388.8  971.92  5394.9  973.80  5458.1  991.52  5488.2  996.93
  5528.4  999.26  5558.5  997.17  5578.6  998.07  5605.3 1002.49  5650.8 1004.38
#Mann=6,-1,0
  4526.2    0.12       0  4880.4   0.033       0  5033.8   0.033       0
  5038.9   0.033       0  5042.6   0.035       0  5394.9    0.12       0
Bank Sta=5033.8,5038.9
Exp/Cntr=0.3,0.1

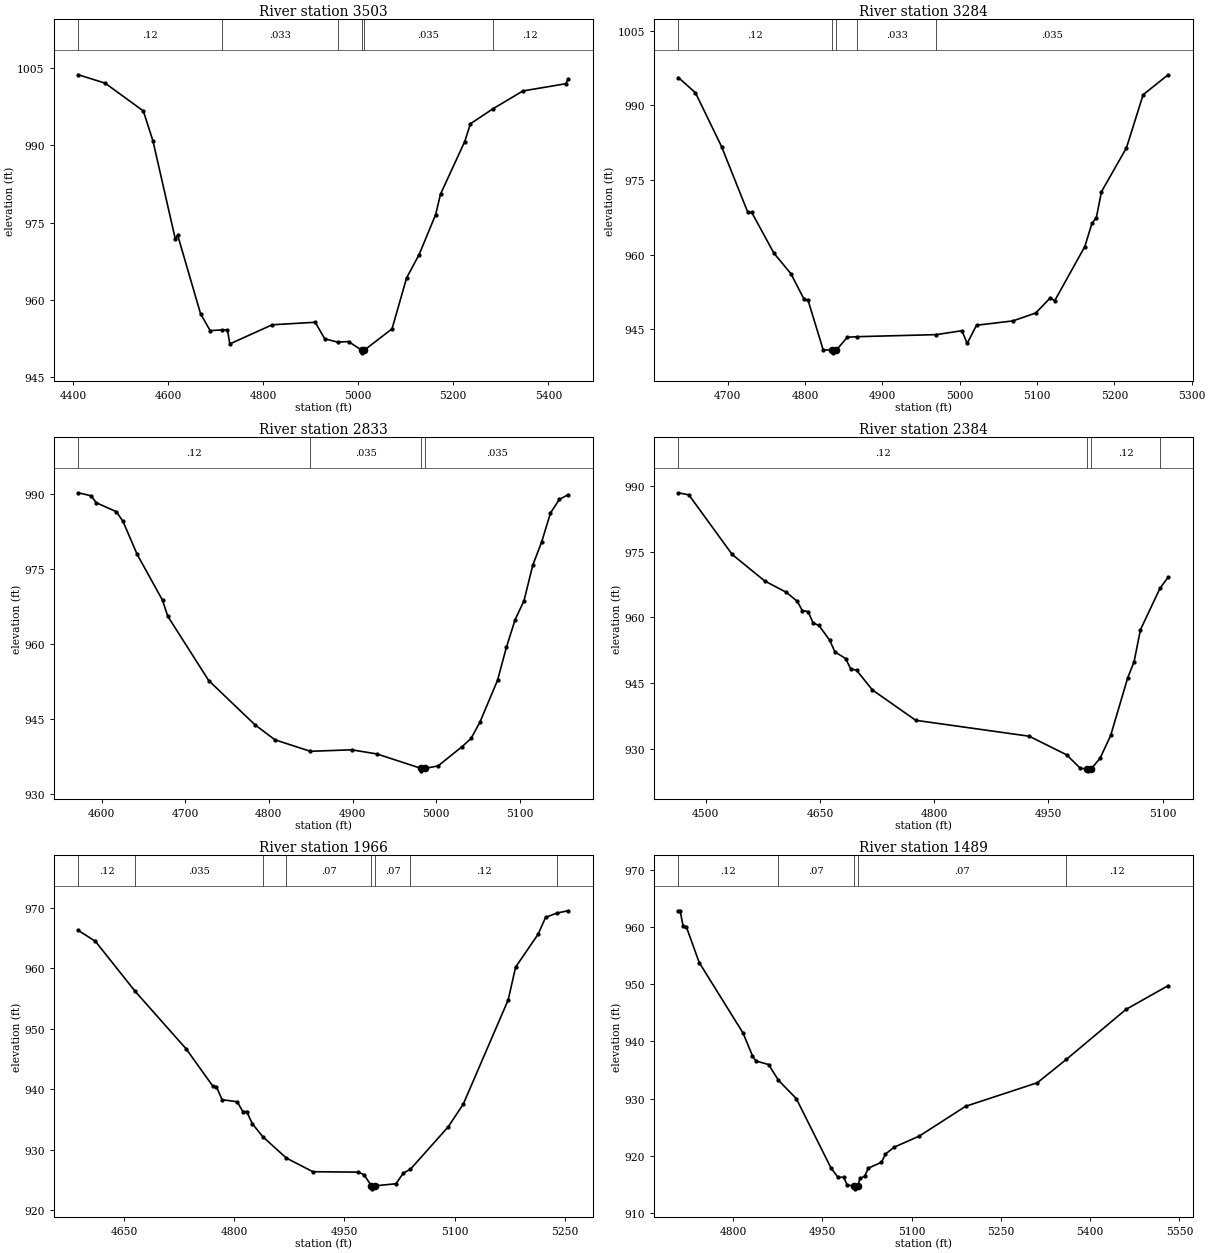
Type RM Length L Ch R = 1,3503,219,219,219
BEGIN DESCRIPTION:
Schultz Creek 7.5
END DESCRIPTION:
XS GIS Cut Line= 3
      2177511.01     13883408.88      2176924.89     13883354.90
      2176491.88     13883269.73
#Sta/Elev= 30
  4411.4 1003.73  4467.6 1002.11  4548.0  996.71  4568.1  990.96  4615.3  971.85
  4620.3  972.57  4668.5  957.30  4688.6  954.04  4714.2  954.17  4725.0  954.19
  4730.0  951.45  4819.1  955.17  4909.5  955.66  4929.6  952.45  4956.6  951.80
  4979.8  951.91  5007.5  950.22  5007.9  949.72  5012.6  950.22  5071.2  954.39
  5101.8  964.28  5128.1  968.81  5162.9  976.59  5173.1  980.55  5224.1  990.77
  5236.0  994.22  5283.0  997.10  5346.4 1000.59  5436.5 1001.99  5441.3 1002.88
#Mann=6,-1,0
  4411.4    0.12       0  4714.2   0.033       0  4956.6   0.035       0
  5007.5   0.035       0  5012.6   0.035       0  5283.0    0.12       0
Bank Sta=5007.5,5012.6
Exp/Cntr=0.3,0.1

Type RM Length L Ch R = 1,3284,451,451,451
BEGIN DESCRIPTION:
Schultz Creek 7.0
END DESCRIPTION:
XS GIS Cut Line= 3
      2177374.96     13883274.99      2177025.00     13883175.00
      2176775.02     13883075.01
#Sta/Elev= 30
  4636.3  995.59  4658.4  992.52  4692.2  981.68  4726.0  968.51  4731.2  968.45
  4759.8  960.28  4781.9  956.12  4798.8  951.00  4804.0  950.78  4823.5  940.86
  4835.2  940.73  4835.6  940.23  4840.3  940.73  4854.7  943.36  4867.9  943.48
  4969.5  943.89  5003.0  944.68  5009.7  942.12  5021.8  945.78  5068.9  946.65
  5098.5  948.25  5117.4  951.32  5122.8  950.68  5161.8  961.59  5171.2  966.33
  5176.6  967.32  5183.4  972.63  5215.7  981.46  5237.2  992.11  5269.5  996.14
#Mann=5,-1,0
  4636.3    0.12       0  4835.2   0.035       0  4840.3    0.12       0
  4867.9   0.033       0  4969.5   0.035       0
Bank Sta=4835.2,4840.3
Exp/Cntr=0.3,0.1

Type RM Length L Ch R = 1,2833,449,449,449
BEGIN DESCRIPTION:
Schultz Creek 6.0
END DESCRIPTION:
XS GIS Cut Line= 3
      2177475.02     13882925.01      2177075.00     13882775.00
      2176925.04     13882725.01
#Sta/Elev= 30
  4572.3  990.22  4587.5  989.62  4593.7  988.23  4617.7  986.44  4625.7  984.49
  4642.6  977.89  4672.9  968.72  4679.1  965.54  4728.1  952.65  4783.3  943.81
  4807.3  940.79  4849.6  938.49  4899.0  938.79  4929.2  937.96  4981.8  935.08
  4982.2  934.58  4987.0  935.08  5002.2  935.56  5031.1  939.44  5041.7  941.07
  5052.2  944.29  5073.3  952.68  5083.9  959.28  5094.4  964.85  5104.9  968.58
  5115.5  975.76  5126.0  980.35  5136.6  986.16  5147.1  988.88  5157.6  989.83
#Mann=4,-1,0
  4572.3    0.12       0  4849.6   0.035       0  4981.8   0.035       0
  4987.0   0.035       0
Bank Sta=4981.8,4987
Exp/Cntr=0.3,0.1

Type RM Length L Ch R = 1,2384,418,418,418
BEGIN DESCRIPTION:
Schultz Creek 5.0
END DESCRIPTION:
XS GIS Cut Line= 3
      2177575.02     13882775.02      2177225.00     13882375.00
      2177125.03     13882325.02
#Sta/Elev= 30
  4463.9  988.46  4477.7  987.98  4534.6  974.37  4577.3  968.32  4605.8  965.72
  4620.1  963.67  4626.7  961.56  4634.3  961.33  4640.9  958.72  4648.5  958.17
  4662.8  954.76  4669.4  952.16  4683.6  950.59  4690.3  948.24  4697.9  947.94
  4718.8  943.43  4775.7  936.50  4924.7  932.87  4974.1  928.60  4992.1  925.50
  5001.2  925.46  5001.6  924.96  5006.4  925.46  5017.8  927.81  5031.8  933.04
  5054.1  946.17  5062.5  949.85  5070.9  957.18  5096.6  966.65  5107.2  969.16
#Mann=4,-1,0
  4463.9    0.12       0  5001.2    0.05       0  5006.4    0.12       0
  5096.6   0.035       0
Bank Sta=5001.2,5006.4
Exp/Cntr=0.3,0.1

Type RM Length L Ch R = 1,1966,477,477,477
BEGIN DESCRIPTION:
Schultz Creek 4.0
END DESCRIPTION:
XS GIS Cut Line= 3
      2177825.04     13882125.01      2177425.00     13882025.00
      2177175.00     13881975.00
#Sta/Elev= 30
  4587.4  966.23  4610.6  964.44  4664.6  956.20  4734.3  946.66  4770.4  940.55
  4775.6  940.37  4783.3  938.26  4803.9  937.92  4811.6  936.29  4816.8  936.30
  4824.5  934.29  4838.7  932.15  4870.8  928.62  4907.0  926.36  4968.8  926.29
  4976.6  925.88  4986.8  924.03  4987.2  923.53  4992.1  924.03  5020.1  924.37
  5030.3  926.13  5040.0  926.78  5091.5  933.79  5111.9  937.52  5173.1  954.74
  5183.3  960.18  5213.9  965.60  5224.1  968.39  5239.8  969.11  5254.7  969.48
#Mann=8,-1,0
  4587.4    0.12       0  4664.6   0.035       0  4838.7    0.12       0
  4870.8    0.07       0  4986.8    0.05       0  4992.1    0.07       0
  5040.0    0.12       0  5239.8   0.035       0
Bank Sta=4986.8,4992.1
Exp/Cntr=0.3,0.1

Type RM Length L Ch R = 1,1489,468,468,468
BEGIN DESCRIPTION:
Schultz Creek 3.0
END DESCRIPTION:
XS GIS Cut Line= 3
      2177875.00     13881775.00      2177625.00     13881625.00
      2177274.97     13881224.96
#Sta/Elev= 30
  4707.8  962.85  4710.7  962.85  4715.6  960.24  4721.4  959.98  4742.8  953.80
  4816.6  941.45  4832.2  937.52  4838.0  936.59  4859.4  935.97  4876.0  933.21
  4906.0  930.01  4964.4  917.86  4976.0  916.27  4985.7  916.24  4991.6  914.89
  5003.7  914.73  5004.2  914.23  5009.2  914.73  5013.1  916.05  5020.7  916.42
  5027.3  917.86  5049.2  918.87  5055.8  920.30  5070.1  921.49  5112.8  923.46
  5190.6  928.66  5311.1  932.78  5360.0  936.87  5460.1  945.60  5530.9  949.75
#Mann=5,-1,0
  4707.8    0.12       0  4876.0    0.07       0  5003.7    0.05       0
  5009.2    0.07       0  5360.0    0.12       0
Bank Sta=5003.7,5009.2
Exp/Cntr=0.3,0.1

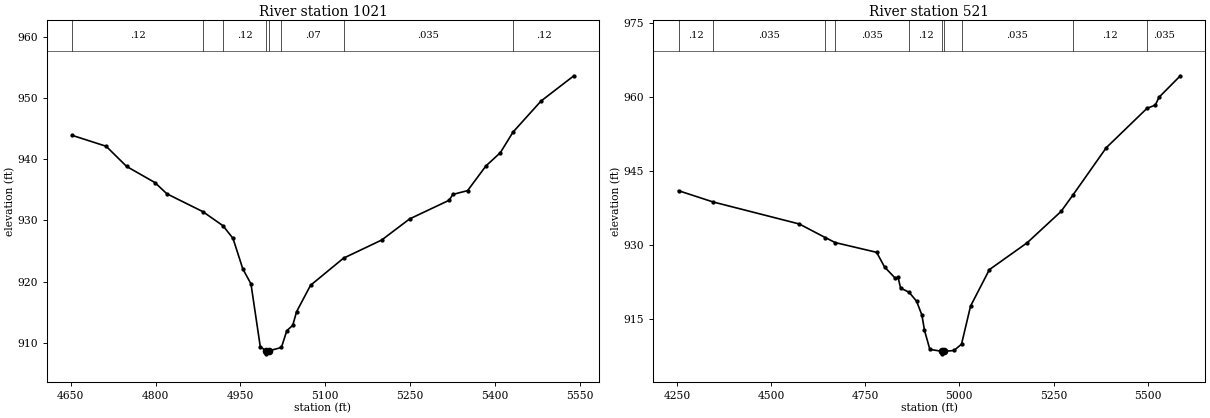
Type RM Length L Ch R = 1,1021,500,500,500
BEGIN DESCRIPTION:
Schultz Creek 2.0
END DESCRIPTION:
XS GIS Cut Line= 3
      2178152.95     13881341.51      2177825.00     13881225.00
      2177310.93     13881063.73
#Sta/Elev= 30
  4652.4  943.92  4712.6  942.13  4748.8  938.83  4798.8  936.19  4820.0  934.35
  4883.6  931.43  4919.2  929.12  4936.8  927.06  4954.1  922.08  4968.6  919.60
  4985.0  909.34  4995.0  908.67  4995.5  908.17  5000.5  908.67  5022.4  909.21
  5031.9  911.96  5042.4  912.83  5049.1  915.05  5073.8  919.38  5132.1  923.82
  5199.6  926.79  5248.9  930.24  5318.9  933.30  5325.3  934.25  5351.4  934.87
  5383.8  938.91  5409.2  941.07  5431.7  944.45  5481.1  949.52  5539.2  953.66
#Mann=8,-1,0
  4652.4    0.12       0  4883.6   0.035       0  4919.2    0.12       0
  4995.0    0.05       0  5000.5    0.12       0  5022.4    0.07       0
  5132.1   0.035       0  5431.7    0.12       0
Bank Sta=4995,5000.5
Exp/Cntr=0.3,0.1

Type RM Length L Ch R = 1,521,0,0,0
BEGIN DESCRIPTION:
Schultz Creek 1.0
END DESCRIPTION:
XS GIS Cut Line= 3
      2178326.58     13881276.42      2177825.00     13880725.00
      2177238.59     13880694.89
#Sta/Elev= 30
  4254.2  941.08  4345.3  938.81  4574.9  934.33  4643.7  931.58  4670.2  930.56
  4780.3  928.58  4801.3  925.61  4829.7  923.33  4837.1  923.54  4843.9  921.34
  4866.6  920.47  4886.4  918.66  4900.6  915.83  4907.4  912.75  4921.6  908.89
  4954.6  908.49  4955.0  907.99  4960.1  908.49  4985.8  908.67  5005.7  909.95
  5029.7  917.67  5079.7  925.07  5179.9  930.51  5270.0  936.87  5301.2  940.16
  5390.1  949.80  5498.3  957.79  5520.3  958.44  5530.3  960.04  5586.8  964.39
#Mann=10,-1,0
  4254.2    0.12       0  4345.3   0.035       0  4643.7    0.07       0
  4670.2   0.035       0  4866.6    0.12       0  4954.6    0.05       0
  4960.1    0.12       0  5005.7   0.035       0  5301.2    0.12       0
  5498.3   0.035       0
Bank Sta=4954.6,4960.1
Exp/Cntr=0.3,0.1

Chan Stop Cuts=-1