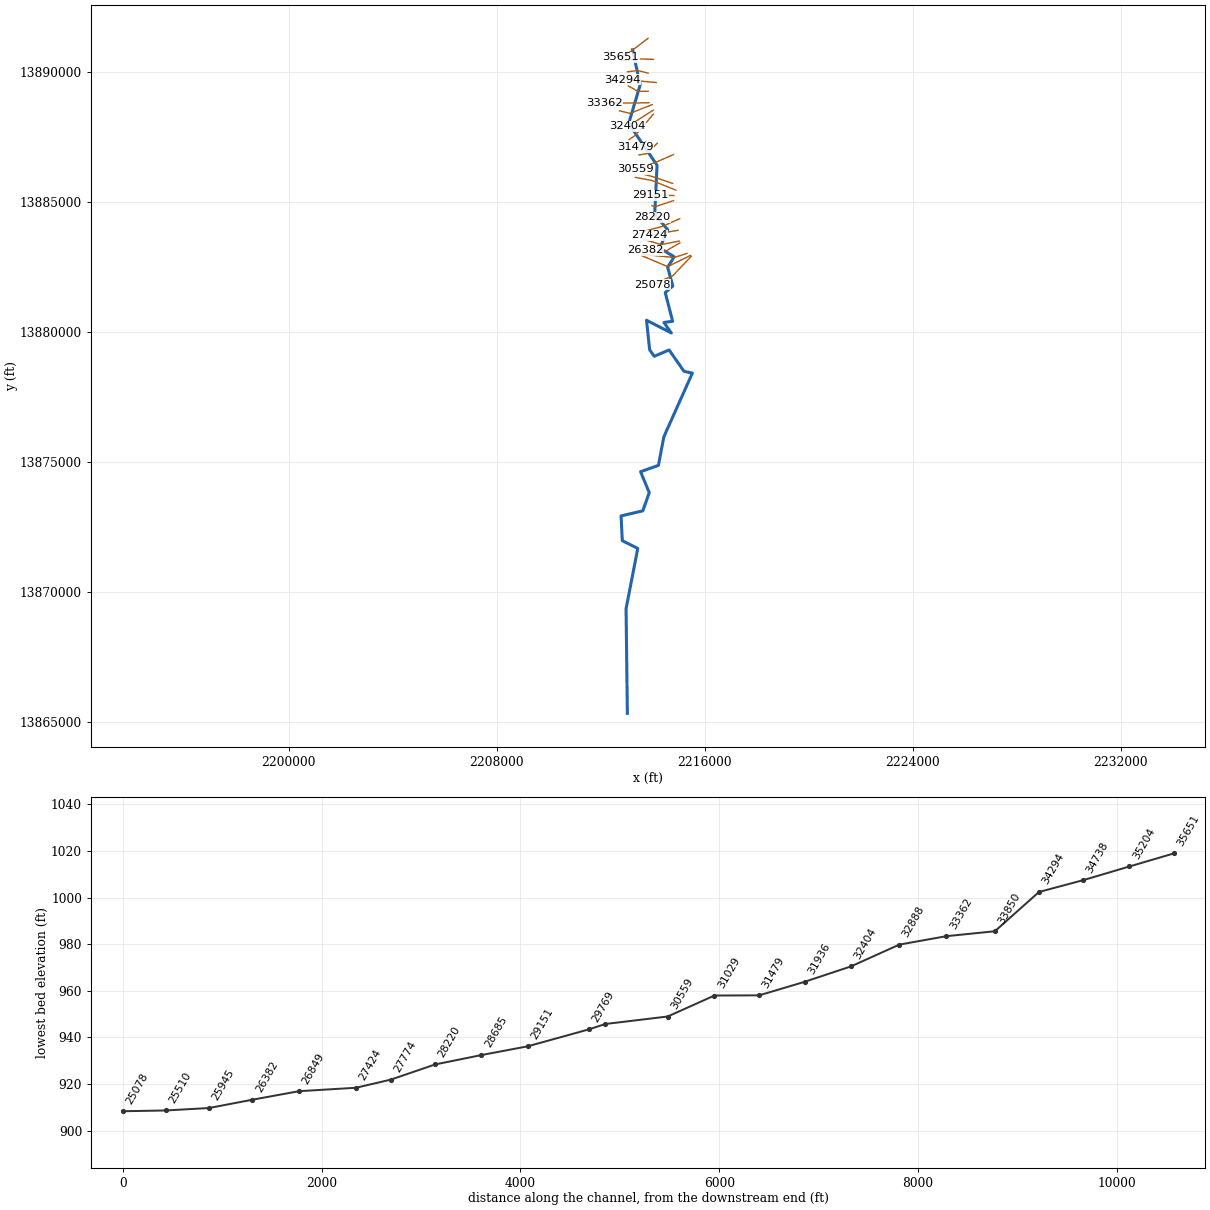
--- Sorrel Creek.prj (project) ---

Proj Title=Sorrel Creek Base Level Engineering
Current Plan=p01
Default Exp/Contr=0.3,0.1
English Units
Geom File=g01
Flow File=f01
Plan File=p01
BEGIN DESCRIPTION:
Sorrel Creek
END DESCRIPTION:

--- Sorrel Creek.p01 (plan) ---

Plan Title=Multiple Run
Short Identifier=Multiple
Geom File=g01
Flow File=f01
Subcritical Flow
K Sum by GR= 0
Std Step Tol= 0.01
Critical Tol= 0.01
Num of Std Step Trials= 20
Max Error Tol= 0.3
Flow Tol Ratio= 0.001
Split Flow NTrial= 30
Split Flow Tol= 0.02
Split Flow Ratio= 0.02
Log Output Level= 0
Friction Slope Method= 1
Unsteady Friction Slope Method= 2
Unsteady Bridges Friction Slope Method= 1
Parabolic Critical Depth
Global Vel Dist=  1 , 1 , 1
Global Log Level= 0
CheckData=True
Encroach Param= -1, 0, 0, 0
BEGIN DESCRIPTION:
Multiple Run
END DESCRIPTION:

--- Sorrel Creek.f01 (steady flow) ---

Flow Title=Multiple
Number of Profiles=7
Profile Names=10-year,25-year,50-year,1pct_min,100-year,1pct_plu,500-year
River Rch & RM= Sorrel Creek,Reach-1,35651
    1201    2050    2867    1943    3877    7737    7014
River Rch & RM= Sorrel Creek,Reach-1,35204
    2112    3691    5238    3593    7169   14305   13296
Boundary for River Rch & Prof#=Sorrel Creek,Reach-1,1
Up Type=0
Dn Type=3
Dn Slope=0.005
Boundary for River Rch & Prof#=Sorrel Creek,Reach-1,2
Up Type=0
Dn Type=3
Dn Slope=0.005
Boundary for River Rch & Prof#=Sorrel Creek,Reach-1,3
Up Type=0
Dn Type=3
Dn Slope=0.005
Boundary for River Rch & Prof#=Sorrel Creek,Reach-1,4
Up Type=0
Dn Type=3
Dn Slope=0.005
Boundary for River Rch & Prof#=Sorrel Creek,Reach-1,5
Up Type=0
Dn Type=3
Dn Slope=0.005
Boundary for River Rch & Prof#=Sorrel Creek,Reach-1,6
Up Type=0
Dn Type=3
Dn Slope=0.005
Boundary for River Rch & Prof#=Sorrel Creek,Reach-1,7
Up Type=0
Dn Type=3
Dn Slope=0.005

--- Sorrel Creek.g01 (geometry) ---

Geom Title=Existing Conditions

River Reach=Sorrel Creek,Reach-1
Reach XY= 30
      2213225.00     13890875.00      2213517.44     13889525.00
      2213076.05     13888035.44      2214167.21     13886428.42
      2214076.38     13884534.66      2214575.43     13883947.95
      2214275.86     13883235.31      2214825.37     13882904.80
      2214574.58     13882500.00      2214773.31     13881780.64
      2214481.90     13881525.00      2214767.12     13880421.37
      2214431.97     13880375.25      2214717.01     13879971.63
      2213761.20     13880461.66      2213882.87     13879321.78
      2214059.80     13879074.50      2214631.68     13879316.06
      2215200.98     13878497.63      2215525.86     13878425.04
      2214428.76     13875973.44      2214219.53     13874872.55
      2213532.89     13874628.58      2213867.78     13873824.69
      2213619.30     13873122.46      2212782.79     13872928.45
      2212830.52     13871972.00      2213425.00     13871675.00
      2212974.91     13869352.31      2213025.00     13865325.00

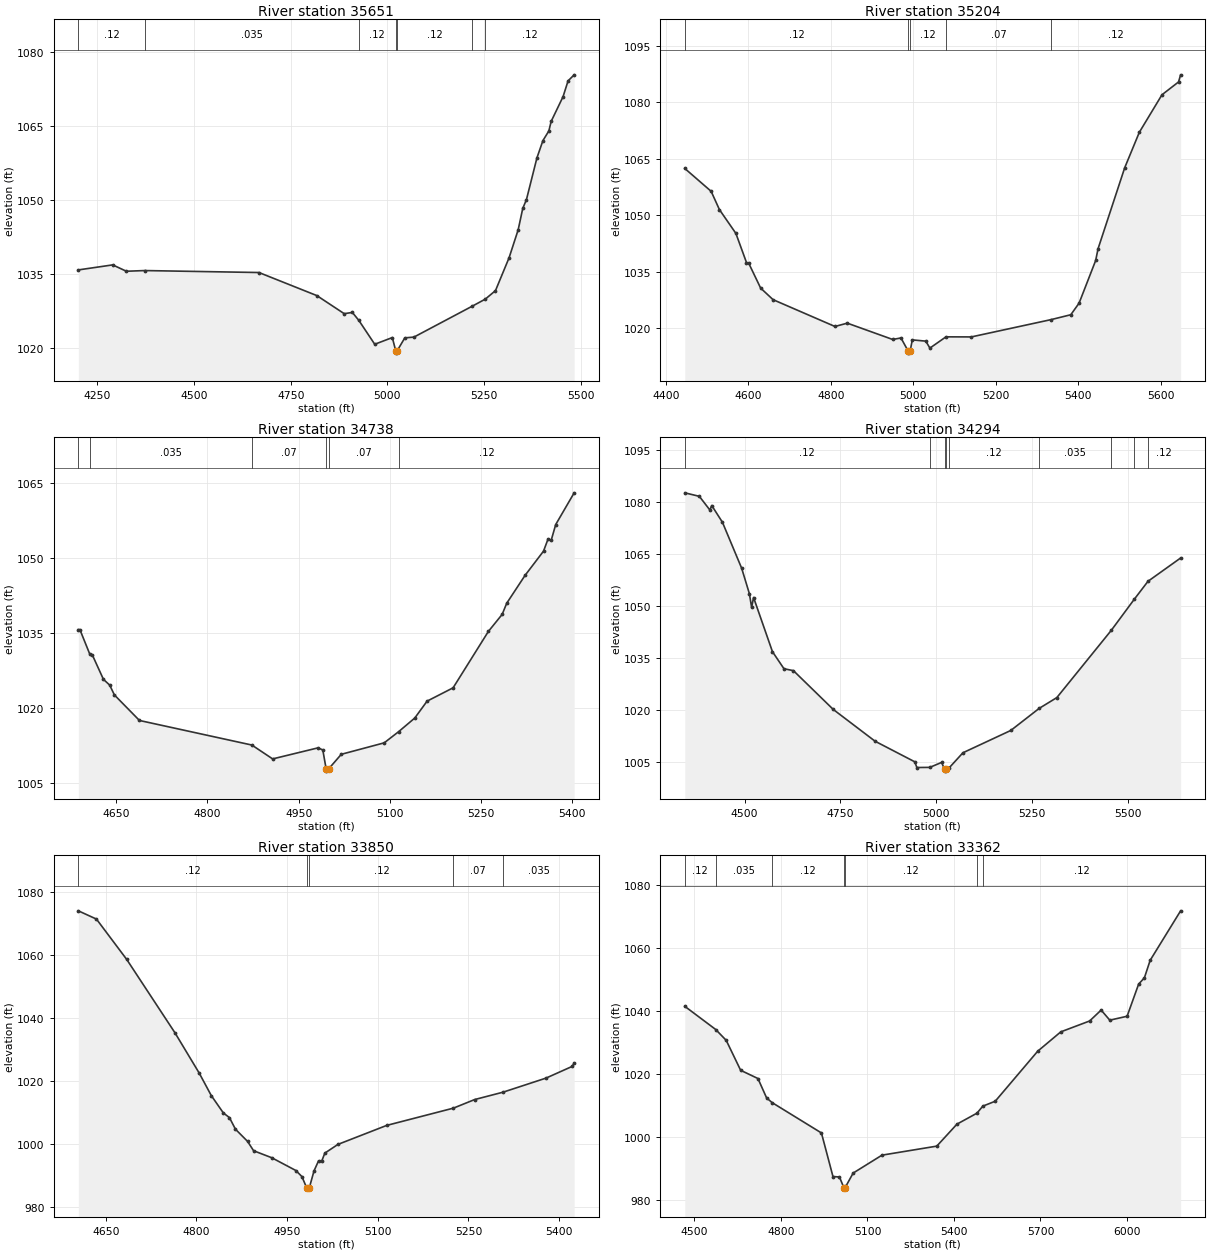
Type RM Length L Ch R = 1,35651,447,447,447
BEGIN DESCRIPTION:
Sorrel Creek 54.0
END DESCRIPTION:
XS GIS Cut Line= 3
      2213819.24     13891314.96      2213175.00     13890825.00
      2212771.60     13890577.42
#Sta/Elev= 30
  4200.6 1035.82  4289.5 1036.84  4324.9 1035.55  4372.5 1035.69  4667.9 1035.29
  4817.6 1030.61  4888.4 1026.94  4909.5 1027.19  4926.4 1025.56  4967.4 1020.73
  5012.9 1022.09  5021.6 1019.43  5021.8 1018.93  5025.6 1019.43  5045.2 1022.03
  5068.7 1022.18  5219.9 1028.47  5253.6 1029.90  5279.8 1031.62  5315.0 1038.30
  5338.5 1043.97  5350.3 1048.29  5359.9 1050.10  5387.0 1058.56  5402.5 1062.07
  5417.9 1064.04  5423.8 1065.97  5454.6 1070.99  5467.6 1074.20  5483.3 1075.42
#Mann=7,-1,0
  4200.6    0.12       0  4372.5   0.035       0  4926.4    0.12       0
  5021.6    0.05       0  5025.6    0.12       0  5219.9    0.07       0
  5253.6    0.12       0
Bank Sta=5021.6,5025.6
Exp/Cntr=0.3,0.1

Type RM Length L Ch R = 1,35204,466,466,466
BEGIN DESCRIPTION:
Sorrel Creek 53.0
END DESCRIPTION:
XS GIS Cut Line= 3
      2214028.82     13890504.42      2213475.00     13890525.00
      2212830.07     13890459.99
#Sta/Elev= 30
  4445.8 1062.44  4509.7 1056.36  4529.7 1051.51  4569.7 1045.17  4595.4 1037.42
  4600.4 1037.33  4629.7 1030.63  4659.8 1027.55  4809.9 1020.42  4839.9 1021.30
  4950.0 1016.96  4970.0 1017.37  4987.7 1013.83  4988.0 1013.33  4992.2 1013.83
  4997.5 1016.85  5030.2 1016.52  5040.2 1014.67  5079.2 1017.66  5140.7 1017.64
  5334.0 1022.24  5381.9 1023.54  5402.0 1026.63  5442.2 1037.97  5448.0 1041.10
  5512.6 1062.63  5548.1 1072.07  5603.0 1082.04  5643.1 1085.44  5648.2 1087.34
#Mann=5,-1,0
  4445.8    0.12       0  4987.7    0.05       0  4992.2    0.12       0
  5079.2    0.07       0  5334.0    0.12       0
Bank Sta=4987.7,4992.2
Exp/Cntr=0.3,0.1

Type RM Length L Ch R = 1,34738,444,444,444
BEGIN DESCRIPTION:
Sorrel Creek 52.0
END DESCRIPTION:
XS GIS Cut Line= 3
      2213825.05     13889974.99      2213425.00     13890075.00
      2213024.97     13890025.00
#Sta/Elev= 30
  4587.6 1035.71  4590.2 1035.71  4606.6 1030.77  4610.8 1030.61  4628.9 1025.78
  4639.2 1024.63  4646.9 1022.67  4688.1 1017.57  4873.0 1012.66  4907.2 1009.89
  4981.9 1012.10  4989.7 1011.68  4995.1 1007.95  4995.4 1007.45  4999.7 1007.95
  5020.1 1010.81  5090.7 1013.10  5114.4 1015.33  5141.0 1018.06  5161.2 1021.43
  5204.0 1024.09  5262.0 1035.35  5284.7 1038.76  5292.2 1040.99  5322.4 1046.56
  5352.7 1051.39  5360.2 1053.83  5365.3 1053.55  5372.8 1056.71  5403.1 1063.04
#Mann=6,-1,0
  4587.6    0.12       0  4606.6   0.035       0  4873.0    0.07       0
  4995.1    0.05       0  4999.7    0.07       0  5114.4    0.12       0
Bank Sta=4995.1,4999.7
Exp/Cntr=0.3,0.1

Type RM Length L Ch R = 1,34294,444,444,444
BEGIN DESCRIPTION:
Sorrel Creek 51.0
END DESCRIPTION:
XS GIS Cut Line= 3
      2214132.87     13889613.73      2213475.00     13889675.00
      2212842.63     13889722.97
#Sta/Elev= 30
  4343.8 1082.55  4381.8 1081.54  4409.2 1077.61  4414.2 1078.89  4442.1 1074.07
  4492.3 1060.83  4512.4 1053.53  4518.3 1049.56  4523.4 1052.40  4572.7 1036.80
  4602.8 1031.88  4627.5 1031.33  4731.6 1020.15  4840.8 1011.00  4944.3 1005.08
  4949.9 1003.43  4983.6 1003.47  5014.5 1004.90  5022.3 1002.89  5022.6 1002.39
  5026.9 1002.89  5033.0 1003.19  5070.2 1007.68  5195.1 1014.10  5269.4 1020.47
  5315.4 1023.57  5457.6 1042.94  5517.5 1051.87  5553.5 1057.07  5638.7 1063.78
#Mann=9,-1,0
  4343.8    0.12       0  4983.6    0.07       0  5022.3    0.05       0
  5026.9    0.07       0  5033.0    0.12       0  5269.4   0.035       0
  5457.6    0.12       0  5517.5    0.07       0  5553.5    0.12       0
Bank Sta=5022.3,5026.9
Exp/Cntr=0.3,0.1

Type RM Length L Ch R = 1,33850,488,488,488
BEGIN DESCRIPTION:
Sorrel Creek 50.0
END DESCRIPTION:
XS GIS Cut Line= 3
      2213824.98     13889275.00      2213425.00     13889275.00
      2213059.56     13889482.86
#Sta/Elev= 30
  4604.6 1074.00  4634.6 1071.37  4684.6 1058.57  4764.6 1035.20  4804.6 1022.43
  4824.6 1015.28  4844.6 1009.75  4854.6 1008.29  4864.6 1004.59  4884.6 1000.73
  4894.6  997.75  4924.6  995.53  4964.6  991.46  4974.6  989.52  4982.2  986.05
  4982.6  985.55  4986.6  985.55  4986.9  986.05  4994.6  991.36  5002.1  994.55
  5007.5  994.55  5012.5  997.00  5034.1  999.76  5114.8 1005.80  5225.2 1011.29
  5260.4 1014.02  5307.3 1016.36  5378.5 1020.84  5421.9 1024.57  5425.0 1025.65
#Mann=5,-1,0
  4604.6    0.12       0  4982.2    0.05       0  4986.9    0.12       0
  5225.2    0.07       0  5307.3   0.035       0
Bank Sta=4982.2,4986.9
Exp/Cntr=0.3,0.1

Type RM Length L Ch R = 1,33362,474,474,474
BEGIN DESCRIPTION:
Sorrel Creek 49.0
END DESCRIPTION:
XS GIS Cut Line= 3
      2213858.64     13888837.67      2213325.00     13888825.00
      2212139.44     13888835.96
#Sta/Elev= 30
  4466.6 1041.39  4573.8 1034.04  4610.3 1030.59  4660.3 1021.11  4720.3 1018.50
  4750.3 1012.35  4769.5 1010.86  4940.4 1001.25  4980.4  987.43  5002.9  987.29
  5018.0  983.94  5018.3  983.44  5022.7  983.94  5050.4  988.53  5150.4  994.21
  5340.4  997.07  5410.4 1004.04  5479.8 1007.52  5500.0 1009.74  5543.2 1011.31
  5690.4 1027.16  5770.4 1033.29  5870.4 1036.74  5910.4 1040.20  5940.4 1037.00
  6000.4 1038.24  6040.4 1048.43  6060.4 1050.43  6080.4 1055.98  6186.0 1071.66
#Mann=7,-1,0
  4466.6    0.12       0  4573.8   0.035       0  4769.5    0.12       0
  5018.0    0.05       0  5022.7    0.12       0  5479.8    0.07       0
  5500.0    0.12       0
Bank Sta=5018,5022.7
Exp/Cntr=0.3,0.1

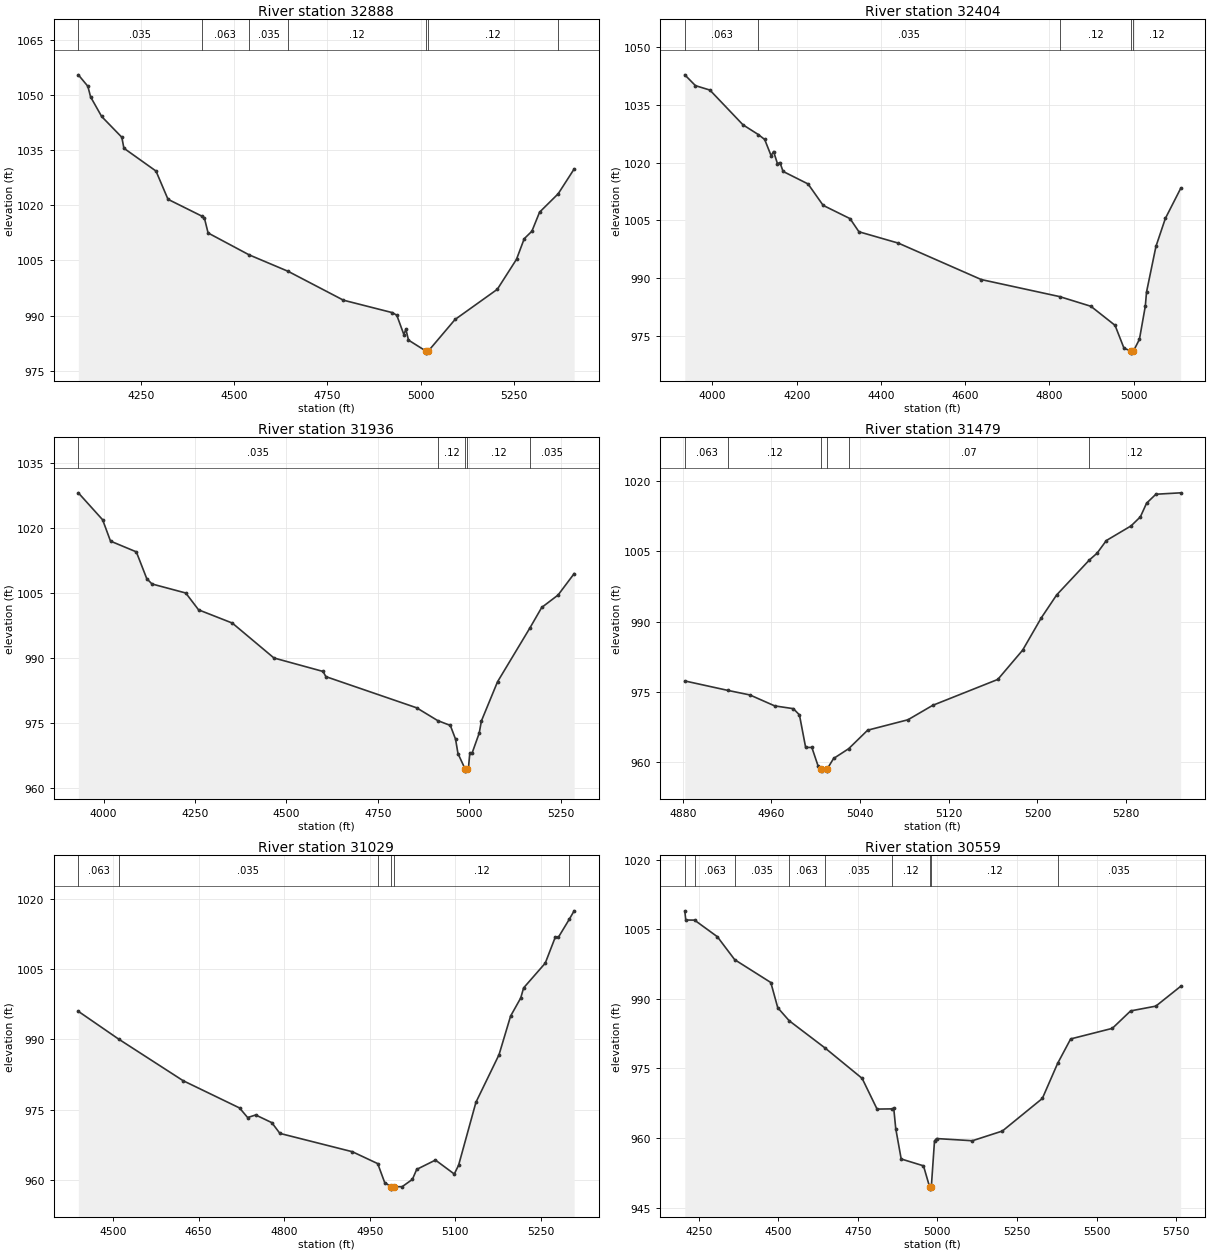
Type RM Length L Ch R = 1,32888,484,484,484
BEGIN DESCRIPTION:
Sorrel Creek 48.0
END DESCRIPTION:
XS GIS Cut Line= 3
      2213978.75     13888762.81      2213125.00     13888425.00
      2212724.96     13888525.01
#Sta/Elev= 30
  4081.8 1055.41  4107.3 1052.31  4114.7 1049.42  4144.4 1044.09  4198.5 1038.45
  4204.1 1035.47  4290.2 1029.27  4322.4 1021.60  4412.4 1017.07  4420.1 1016.50
  4430.0 1012.45  4540.0 1006.51  4644.8 1002.03  4793.2  994.19  4924.7  990.80
  4936.4  990.10  4955.4  984.83  4960.7  986.31  4967.7  983.35  5015.5  980.31
  5015.9  979.81  5020.4  980.31  5092.7  988.95  5206.1  997.15  5257.6 1005.30
  5278.3 1010.89  5298.9 1012.93  5319.5 1018.10  5369.4 1023.09  5412.3 1029.84
#Mann=7,-1,0
  4081.8   0.035       0  4412.4   0.063       0  4540.0   0.035       0
  4644.8    0.12       0  5015.5    0.05       0  5020.4    0.12       0
  5369.4   0.035       0
Bank Sta=5015.5,5020.4
Exp/Cntr=0.3,0.1

Type RM Length L Ch R = 1,32404,468,468,468
BEGIN DESCRIPTION:
Sorrel Creek 47.0
END DESCRIPTION:
XS GIS Cut Line= 3
      2214021.25     13888551.49      2213125.00     13887975.00
      2213025.04     13887925.02
#Sta/Elev= 30
  3934.3 1042.80  3959.6 1039.99  3993.9 1038.84  4072.5 1029.81  4108.8 1027.29
  4124.0 1026.01  4139.2 1021.80  4145.1 1022.88  4154.3 1019.73  4160.3 1020.02
  4167.6 1017.71  4227.0 1014.45  4262.8 1008.89  4326.7 1005.44  4347.8 1002.03
  4441.6  999.07  4638.4  989.61  4824.2  985.19  4898.6  982.67  4956.0  977.72
  4977.2  971.78  4994.5  971.00  4994.9  970.50  4999.5  971.00  5013.9  974.10
  5027.9  982.73  5030.7  986.35  5053.1  998.22  5075.4 1005.48  5111.7 1013.27
#Mann=5,-1,0
  3934.3   0.063       0  4108.8   0.035       0  4824.2    0.12       0
  4994.5    0.05       0  4999.5    0.12       0
Bank Sta=4994.5,4999.5
Exp/Cntr=0.3,0.1

Type RM Length L Ch R = 1,31936,457,457,457
BEGIN DESCRIPTION:
Sorrel Creek 46.0
END DESCRIPTION:
XS GIS Cut Line= 3
      2214021.83     13888391.95      2213325.00     13887575.00
      2213091.58     13887416.70
#Sta/Elev= 30
  3931.1 1028.02  3997.5 1021.81  4019.1 1016.89  4089.7 1014.41  4118.2 1008.24
  4132.5 1007.01  4224.8 1004.93  4259.9 1001.05  4352.1  998.00  4466.0  989.95
  4600.2  986.85  4608.0  985.65  4856.1  978.47  4913.7  975.52  4948.3  974.40
  4962.6  971.23  4969.2  967.92  4988.7  964.37  4989.0  963.87  4993.7  964.37
  4997.7  964.48  5001.6  968.05  5007.9  968.05  5027.3  972.64  5033.3  975.44
  5077.4  984.47  5165.8  996.86  5198.2 1001.60  5242.9 1004.46  5286.9 1009.40
#Mann=5,-1,0
  3931.1   0.035       0  4913.7    0.12       0  4988.7    0.05       0
  4993.7    0.12       0  5165.8   0.035       0
Bank Sta=4988.7,4993.7
Exp/Cntr=0.3,0.1

Type RM Length L Ch R = 1,31479,450,450,450
BEGIN DESCRIPTION:
Sorrel Creek 45.0
END DESCRIPTION:
XS GIS Cut Line= 3
      2213725.03     13887325.01      2213625.00     13887275.00
      2213325.04     13887125.02
#Sta/Elev= 30
  4881.9  977.33  4921.1  975.29  4940.6  974.34  4963.0  972.00  4979.8  971.41
  4985.3  970.08  4990.9  963.13  4996.5  963.13  5002.1  959.18  5005.0  958.57
  5005.4  958.07  5010.0  958.07  5010.4  958.57  5016.1  960.77  5029.7  962.86
  5046.8  966.81  5083.2  969.04  5105.5  972.12  5164.2  977.65  5186.6  983.90
  5203.4  990.79  5217.3  995.70  5246.8 1003.16  5253.7 1004.60  5262.1 1007.31
  5284.4 1010.44  5292.8 1012.37  5298.4 1015.29  5306.8 1017.20  5329.1 1017.50
#Mann=6,-1,0
  4881.9   0.063       0  4921.1    0.12       0  5005.0    0.05       0
  5010.4    0.12       0  5029.7    0.07       0  5246.8    0.12       0
Bank Sta=5005,5010.4
Exp/Cntr=0.3,0.1

Type RM Length L Ch R = 1,31029,470,470,470
BEGIN DESCRIPTION:
Sorrel Creek 44.0
END DESCRIPTION:
XS GIS Cut Line= 3
      2214175.00     13887275.00      2213775.00     13886875.00
      2213475.03     13886825.00
#Sta/Elev= 30
  4438.9  995.99  4509.7  990.05  4622.8  981.16  4721.7  975.34  4735.9  973.29
  4750.0  973.84  4778.3  972.20  4792.5  969.90  4919.7  965.98  4964.1  963.44
  4976.3  959.40  4987.7  958.49  4988.1  957.99  4993.2  958.49  5007.1  958.52
  5024.9  960.07  5032.5  962.21  5065.4  964.20  5098.4  961.22  5106.0  963.11
  5136.4  976.55  5176.9  986.72  5197.2  994.98  5215.0  998.85  5220.0 1000.99
  5258.0 1006.29  5275.8 1011.91  5280.9 1011.79  5300.2 1015.68  5308.7 1017.47
#Mann=6,-1,0
  4438.9   0.063       0  4509.7   0.035       0  4964.1    0.12       0
  4987.7    0.05       0  4993.2    0.12       0  5300.2   0.035       0
Bank Sta=4987.7,4993.2
Exp/Cntr=0.3,0.1

Type RM Length L Ch R = 1,30559,628,628,628
BEGIN DESCRIPTION:
Sorrel Creek 43.0
END DESCRIPTION:
XS GIS Cut Line= 3
      2214802.97     13886841.13      2214075.00     13886525.00
      2213351.23     13886279.57
#Sta/Elev= 30
  4206.4 1008.98  4209.4 1007.00  4237.0 1006.98  4308.7 1003.40  4363.2  998.45
  4476.7  993.53  4498.5  988.09  4534.6  985.28  4646.7  979.44  4763.6  972.87
  4810.5  966.25  4858.8  966.30  4862.9  966.43  4869.2  962.04  4886.3  955.50
  4956.4  954.02  4975.5  949.50  4975.9  949.00  4981.0  949.50  4991.0  959.40
  4997.3  959.90  5110.0  959.43  5204.2  961.52  5329.8  968.54  5377.9  976.11
  5418.8  981.37  5549.7  983.65  5607.2  987.41  5686.4  988.44  5764.3  992.70
#Mann=9,-1,0
  4206.4   0.035       0  4237.0   0.063       0  4363.2   0.035       0
  4534.6   0.063       0  4646.7   0.035       0  4858.8    0.12       0
  4975.5    0.05       0  4981.0    0.12       0  5377.9   0.035       0
Bank Sta=4975.5,4981
Exp/Cntr=0.3,0.1

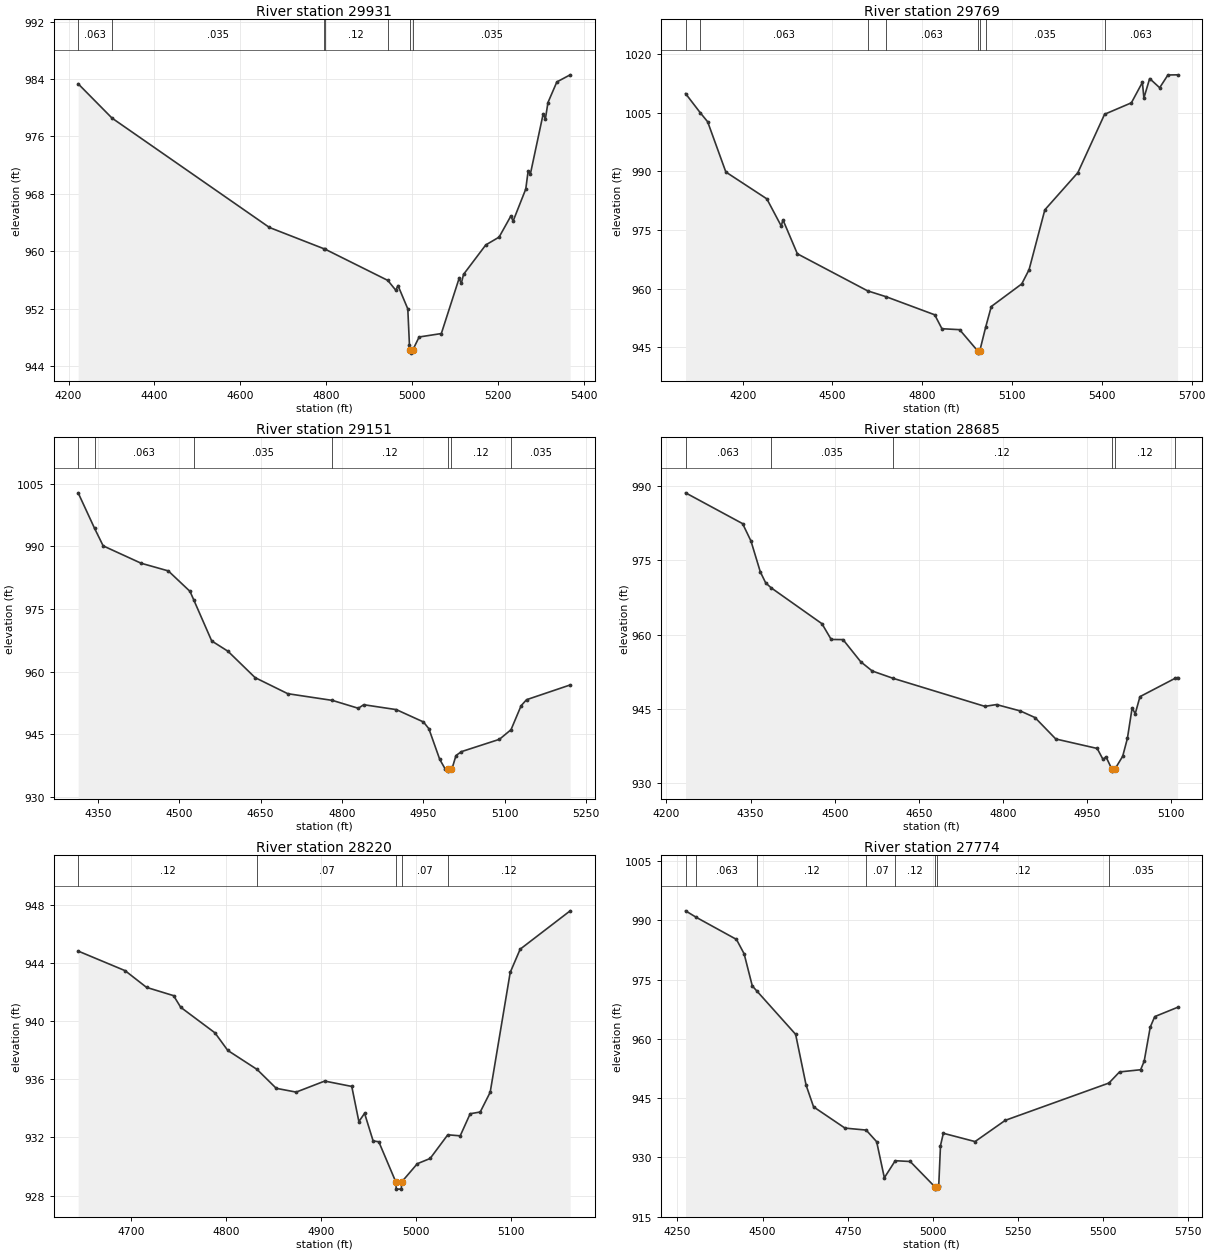
Type RM Length L Ch R = 1,29931,162,162,162
BEGIN DESCRIPTION:
Sorrel Creek 42.0
END DESCRIPTION:
XS GIS Cut Line= 3
      2214766.19     13885727.91      2214040.51     13885978.12
      2213675.03     13886074.99
#Sta/Elev= 30
  4222.4  983.34  4301.2  978.56  4667.9  963.30  4794.6  960.34  4797.0  960.29
  4943.5  955.92  4962.0  954.55  4967.2  955.20  4990.0  951.95  4993.9  946.88
  4996.1  946.28  4996.6  945.78  5002.1  946.28  5016.4  948.03  5068.1  948.51
  5109.4  956.19  5114.6  955.51  5119.8  956.76  5171.6  960.87  5202.6  961.96
  5230.0  964.90  5235.2  964.19  5264.7  968.66  5270.2  971.16  5275.4  970.75
  5305.2  979.13  5310.4  978.45  5316.4  980.73  5337.1  983.60  5368.1  984.59
#Mann=7,-1,0
  4222.4   0.063       0  4301.2   0.035       0  4794.6   0.063       0
  4797.0    0.12       0  4943.5   0.035       0  4996.1   0.035       0
  5002.1   0.035       0
Bank Sta=4996.1,5002.1
Exp/Cntr=0.3,0.1

Type RM Length L Ch R = 1,29769,618,618,618
BEGIN DESCRIPTION:
Sorrel Creek 41.0
END DESCRIPTION:
XS GIS Cut Line= 3
      2214893.48     13885469.03      2213968.24     13885842.60
      2213333.27     13885961.41
#Sta/Elev= 30
  4009.3 1009.88  4058.9 1004.93  4083.1 1002.67  4143.9  989.82  4280.8  982.96
  4329.1  975.99  4334.5  977.62  4382.8  968.91  4617.3  959.44  4679.4  957.93
  4841.7  953.31  4865.8  949.75  4924.9  949.51  4986.0  944.01  4986.5  943.51
  4992.0  944.01  5011.9  950.15  5030.7  955.43  5132.5  961.21  5157.0  964.86
  5209.6  980.15  5320.0  989.67  5409.3 1004.59  5498.7 1007.51  5535.5 1012.74
  5540.6 1008.75  5559.8 1013.72  5593.2 1011.37  5620.8 1014.63  5653.1 1014.67
#Mann=8,-1,0
  4009.3   0.035       0  4058.9   0.063       0  4617.3   0.035       0
  4679.4   0.063       0  4986.0    0.05       0  4992.0   0.063       0
  5011.9   0.035       0  5409.3   0.063       0
Bank Sta=4986,4992
Exp/Cntr=0.3,0.1

Type RM Length L Ch R = 1,29151,466,466,466
BEGIN DESCRIPTION:
Sorrel Creek 40.0
END DESCRIPTION:
XS GIS Cut Line= 3
      2214811.10     13885264.13      2214125.00     13885275.00
      2213904.59     13885273.70
#Sta/Elev= 30
  4313.9 1002.81  4344.1  994.33  4360.0  990.12  4430.0  985.96  4480.0  984.13
  4520.0  979.23  4526.8  977.23  4560.0  967.37  4590.0  964.90  4640.0  958.59
  4700.1  954.75  4782.5  953.14  4830.1  951.26  4840.1  952.11  4900.1  950.94
  4950.1  947.99  4960.1  946.38  4980.1  939.05  4990.1  936.76  4994.5  936.72
  4995.0  936.22  5000.7  936.72  5002.6  936.72  5010.1  939.95  5020.1  940.88
  5090.1  943.83  5111.5  946.13  5130.1  951.87  5140.1  953.31  5220.5  956.84
#Mann=7,-1,0
  4313.9   0.094       0  4344.1   0.063       0  4526.8   0.035       0
  4782.5    0.12       0  4994.5    0.05       0  5000.7    0.12       0
  5111.5   0.035       0
Bank Sta=4994.5,5000.7
Exp/Cntr=0.3,0.1

Type RM Length L Ch R = 1,28685,465,465,465
BEGIN DESCRIPTION:
Sorrel Creek 39.0
END DESCRIPTION:
XS GIS Cut Line= 3
      2214801.49     13885066.47      2214075.00     13884825.00
      2213974.97     13884875.01
#Sta/Elev= 30
  4234.0  988.66  4335.7  982.44  4350.6  978.94  4367.3  972.70  4376.9  970.47
  4386.5  969.49  4477.2  962.23  4493.7  959.05  4514.8  959.02  4546.4  954.54
  4566.9  952.68  4603.6  951.22  4767.7  945.54  4788.5  945.90  4831.0  944.61
  4857.1  943.28  4894.2  938.95  4968.0  937.04  4978.5  934.81  4983.7  935.36
  4993.8  932.96  4994.3  932.46  5000.1  932.96  5013.5  935.46  5021.9  939.07
  5030.3  945.21  5035.9  944.07  5044.3  947.50  5107.4  951.23  5111.4  951.36
#Mann=6,-1,0
  4234.0   0.063       0  4386.5   0.035       0  4603.6    0.12       0
  4993.8    0.05       0  5000.1    0.12       0  5107.4   0.035       0
Bank Sta=4993.8,5000.1
Exp/Cntr=0.3,0.1

Type RM Length L Ch R = 1,28220,446,446,446
BEGIN DESCRIPTION:
Sorrel Creek 38.0
END DESCRIPTION:
XS GIS Cut Line= 3
      2214424.96     13884574.97      2214125.00     13884375.00
      2213975.02     13884424.99
#Sta/Elev= 30
  4643.8  944.83  4693.3  943.48  4715.9  942.33  4744.4  941.76  4751.9  940.96
  4788.0  939.20  4801.5  937.99  4832.4  936.68  4852.6  935.38  4873.6  935.12
  4903.7  935.88  4932.2  935.51  4939.7  933.09  4945.7  933.66  4954.7  931.76
  4960.7  931.70  4978.6  928.94  4979.1  928.44  4984.4  928.44  4984.9  928.94
  5001.3  930.19  5014.8  930.55  5033.4  932.18  5046.5  932.11  5057.0  933.63
  5067.6  933.75  5078.1  935.11  5099.2  943.36  5109.7  944.96  5162.4  947.60
#Mann=5,-1,0
  4643.8    0.12       0  4832.4    0.07       0  4978.6    0.05       0
  4984.9    0.07       0  5033.4    0.12       0
Bank Sta=4978.6,4984.9
Exp/Cntr=0.3,0.1

Type RM Length L Ch R = 1,27774,350,350,350
BEGIN DESCRIPTION:
Sorrel Creek 37.0
END DESCRIPTION:
XS GIS Cut Line= 3
      2215038.62     13884369.82      2214375.00     13884075.00
      2213680.18     13883889.95
#Sta/Elev= 30
  4273.7  992.45  4305.6  990.78  4423.2  985.21  4445.7  981.57  4469.7  973.42
  4484.0  972.05  4597.0  961.16  4627.8  948.27  4649.7  942.78  4742.0  937.40
  4804.2  936.90  4835.0  933.95  4857.6  924.82  4889.6  929.14  4933.5  928.94
  5007.0  922.44  5007.5  921.94  5013.4  922.44  5017.3  922.72  5022.5  932.98
  5030.9  936.09  5124.0  933.99  5212.8  939.37  5517.3  948.82  5548.3  951.63
  5610.4  952.19  5620.8  954.37  5638.6  962.99  5651.8  965.65  5718.9  968.00
#Mann=8,-1,0
  4273.7   0.035       0  4305.6   0.063       0  4484.0    0.12       0
  4804.2    0.07       0  4889.6    0.12       0  5007.0    0.05       0
  5013.4    0.12       0  5517.3   0.035       0
Bank Sta=5007,5013.4
Exp/Cntr=0.3,0.1

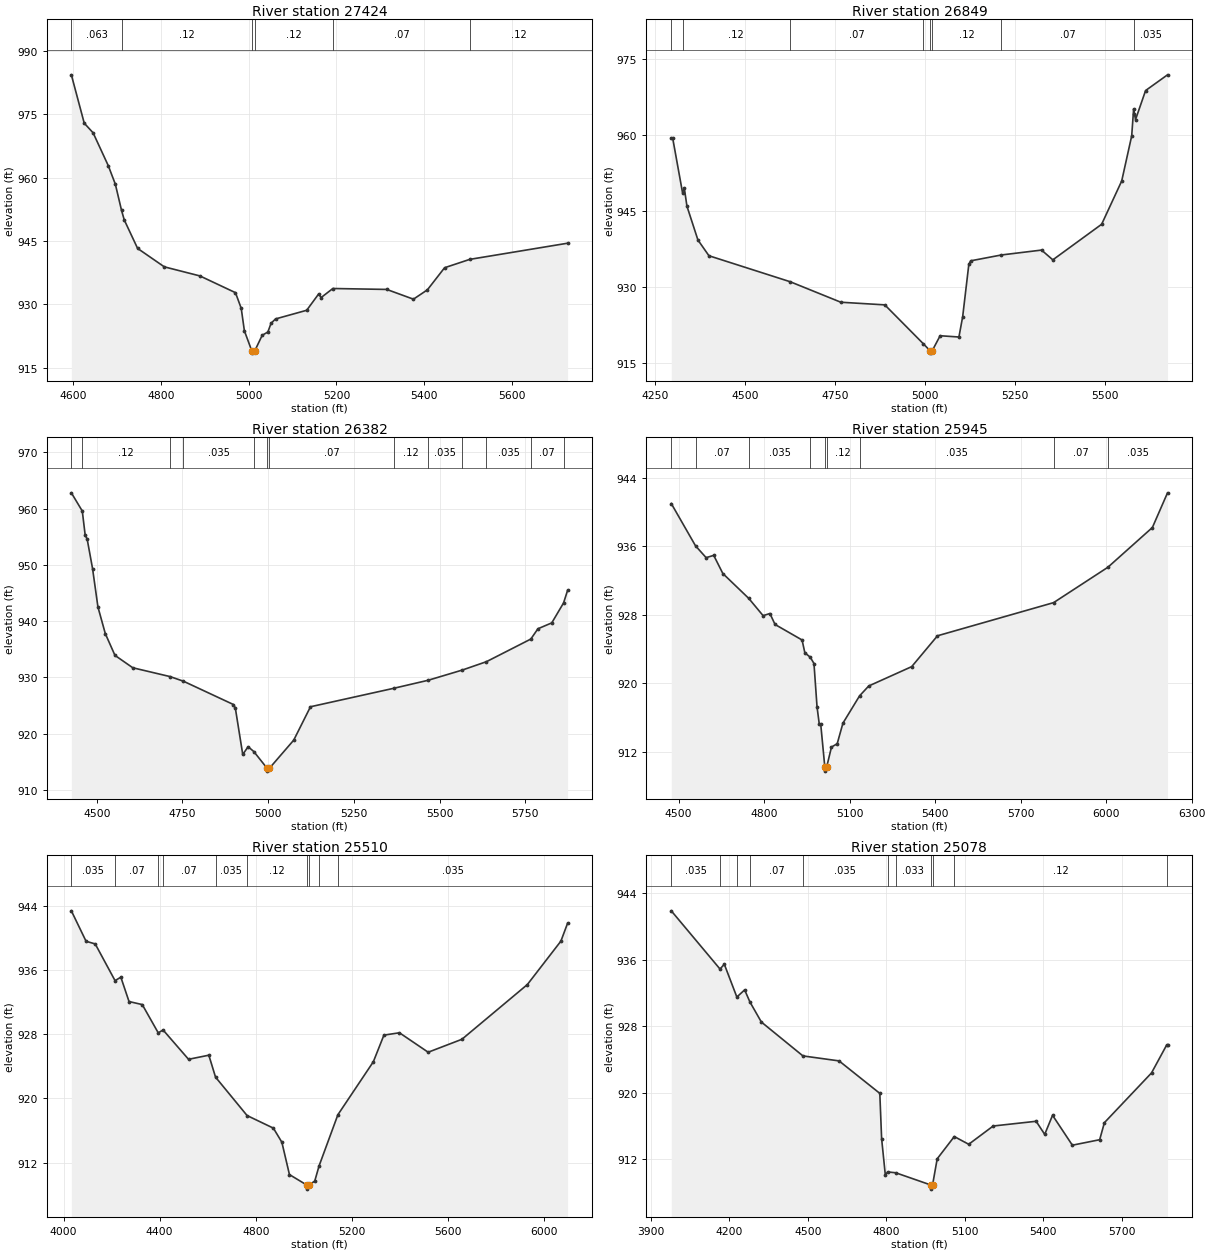
Type RM Length L Ch R = 1,27424,575,575,575
BEGIN DESCRIPTION:
Sorrel Creek 36
END DESCRIPTION:
XS GIS Cut Line= 2
      2214973.95     13883923.78      2213858.47     13883736.48
#Sta/Elev= 30
  4595.9  984.38  4625.3  972.92  4645.5  970.64  4680.1  962.85  4696.2  958.46
  4710.3  952.26  4716.5  950.00  4746.9  943.26  4807.8  938.89  4888.9  936.74
  4970.0  932.77  4983.1  929.06  4990.3  923.74  5007.3  918.95  5007.8  918.45
  5013.8  918.95  5030.9  922.68  5043.8  923.45  5051.1  925.52  5061.3  926.55
  5132.3  928.60  5159.9  932.51  5165.0  931.60  5192.0  933.76  5314.8  933.54
  5375.6  931.23  5407.4  933.44  5446.6  938.68  5504.0  940.66  5727.0  944.49
#Mann=6,-1,0
  4595.9   0.063       0  4710.3    0.12       0  5007.3    0.05       0
  5013.8    0.12       0  5192.0    0.07       0  5504.0    0.12       0
Bank Sta=5007.3,5013.8
Exp/Cntr=0.3,0.1

Type RM Length L Ch R = 1,26849,467,467,467
BEGIN DESCRIPTION:
Sorrel Creek 35.0
END DESCRIPTION:
XS GIS Cut Line= 3
      2215017.75     13883506.36      2214325.00     13883375.00
      2213679.58     13883566.76
#Sta/Elev= 30
  4294.6  959.39  4298.5  959.39  4325.8  948.65  4330.9  949.45  4338.1  945.96
  4368.6  939.29  4399.2  936.18  4625.0  931.05  4765.6  927.01  4887.7  926.49
  4994.4  918.84  5013.0  917.47  5013.5  916.97  5019.6  917.47  5041.4  920.40
  5093.6  920.15  5104.0  924.16  5121.1  934.48  5126.3  935.18  5211.3  936.33
  5323.1  937.30  5354.4  935.37  5490.0  942.39  5545.7  950.92  5573.5  959.83
  5578.9  965.17  5581.2  964.22  5584.1  963.03  5612.1  968.77  5673.0  971.87
#Mann=8,-1,0
  4294.6   0.035       0  4325.8    0.12       0  4625.0    0.07       0
  4994.4    0.12       0  5013.0    0.05       0  5019.6    0.12       0
  5211.3    0.07       0  5581.2   0.035       0
Bank Sta=5013,5019.6
Exp/Cntr=0.3,0.1

Type RM Length L Ch R = 1,26382,437,437,437
BEGIN DESCRIPTION:
Sorrel Creek 34.0
END DESCRIPTION:
XS GIS Cut Line= 3
      2215044.78     13883440.37      2214382.13     13883052.78
      2213709.32     13883147.35
#Sta/Elev= 30
  4426.1  962.79  4458.0  959.55  4466.4  955.28  4472.2  954.57  4487.9  949.34
  4503.6  942.51  4525.1  937.77  4553.3  933.90  4605.2  931.70  4714.1  930.13
  4752.9  929.31  4898.6  925.17  4904.4  924.50  4925.9  916.29  4941.6  917.67
  4958.3  916.80  4997.0  913.83  4997.5  913.33  5003.6  913.83  5074.6  918.84
  5123.4  924.77  5366.1  928.05  5466.1  929.47  5566.0  931.29  5636.5  932.78
  5765.9  936.80  5786.7  938.63  5827.1  939.68  5861.5  943.23  5873.2  945.46
#Mann=13,-1,0
  4426.1   0.094       0  4458.0    0.12       0  4714.1    0.07       0
  4752.9   0.035       0  4958.3    0.07       0  4997.0    0.05       0
  5003.6    0.07       0  5366.1    0.12       0  5466.1   0.035       0
  5566.0    0.07       0  5636.5   0.035       0  5765.9    0.07       0
  5861.5   0.035       0
Bank Sta=4997,5003.6
Exp/Cntr=0.3,0.1

Type RM Length L Ch R = 1,25945,435,435,435
BEGIN DESCRIPTION:
Sorrel Creek 33.0
END DESCRIPTION:
XS GIS Cut Line= 3
      2215321.36     13883036.04      2214825.00     13882875.00
      2213612.15     13882997.97
#Sta/Elev= 30
  4474.4  941.00  4559.5  936.06  4596.7  934.68  4623.3  934.95  4655.3  932.83
  4746.1  929.93  4796.5  927.91  4820.4  928.16  4838.5  926.88  4933.2  925.07
  4943.0  923.58  4962.2  923.05  4975.0  922.32  4985.7  917.28  4993.6  915.24
  4998.7  915.24  5013.0  910.26  5013.5  909.76  5019.7  910.26  5036.4  912.57
  5056.5  912.96  5076.6  915.36  5135.0  918.55  5167.1  919.70  5317.9  921.96
  5408.3  925.56  5815.6  929.43  6006.1  933.56  6162.2  938.20  6215.3  942.25
#Mann=9,-1,0
  4474.4   0.035       0  4559.5    0.07       0  4746.1   0.035       0
  4962.2    0.12       0  5013.0    0.05       0  5019.7    0.12       0
  5135.0   0.035       0  5815.6    0.07       0  6006.1   0.035       0
Bank Sta=5013,5019.7
Exp/Cntr=0.3,0.1

Type RM Length L Ch R = 1,25510,432,432,432
BEGIN DESCRIPTION:
Sorrel Creek 32.0
END DESCRIPTION:
XS GIS Cut Line= 3
      2215449.93     13882953.32      2214575.00     13882525.00
      2213570.68     13882949.27
#Sta/Elev= 30
  4032.6  943.35  4093.8  939.56  4131.9  939.23  4214.4  934.66  4238.5  935.09
  4272.5  932.06  4327.6  931.68  4394.1  928.16  4414.2  928.52  4520.1  924.87
  4604.5  925.38  4632.4  922.65  4763.6  917.87  4873.1  916.30  4908.3  914.55
  4939.9  910.52  5012.5  909.21  5013.0  908.71  5019.2  909.21  5045.0  909.70
  5063.1  911.60  5141.4  917.97  5289.0  924.57  5332.9  927.88  5397.5  928.17
  5517.0  925.75  5657.3  927.36  5929.5  934.17  6069.2  939.58  6097.0  941.81
#Mann=10,-1,0
  4032.6   0.035       0  4214.4    0.07       0  4394.1   0.035       0
  4414.2    0.07       0  4632.4   0.035       0  4763.6    0.12       0
  5012.5    0.05       0  5019.2    0.12       0  5063.1    0.07       0
  5141.4   0.035       0
Bank Sta=5012.5,5019.2
Exp/Cntr=0.3,0.1

Type RM Length L Ch R = 1,25078,0,0,0
BEGIN DESCRIPTION:
Sorrel Creek 31.0
END DESCRIPTION:
XS GIS Cut Line= 3
      2215477.86     13882918.80      2214775.00     13882175.00
      2213974.97     13881824.99
#Sta/Elev= 30
  3977.9  941.89  4164.2  934.88  4180.6  935.46  4228.5  931.51  4258.3  932.37
  4278.4  930.92  4322.2  928.50  4481.1  924.42  4619.2  923.82  4774.9  919.91
  4781.8  914.46  4795.9  910.10  4804.9  910.45  4835.6  910.35  4969.7  908.88
  4970.2  908.38  4976.5  908.88  4994.2  912.03  5059.5  914.71  5114.7  913.78
  5208.2  915.98  5372.4  916.55  5405.1  914.97  5435.1  917.27  5510.8  913.67
  5615.2  914.33  5633.2  916.38  5813.3  922.37  5871.5  925.75  5874.5  925.76
#Mann=11,-1,0
  3977.9   0.035       0  4164.2    0.07       0  4228.5   0.035       0
  4278.4    0.07       0  4481.1   0.035       0  4804.9    0.12       0
  4835.6   0.033       0  4969.7   0.033       0  4976.5   0.033       0
  5059.5    0.12       0  5871.5    0.07       0
Bank Sta=4969.7,4976.5
Exp/Cntr=0.3,0.1

Chan Stop Cuts=-1