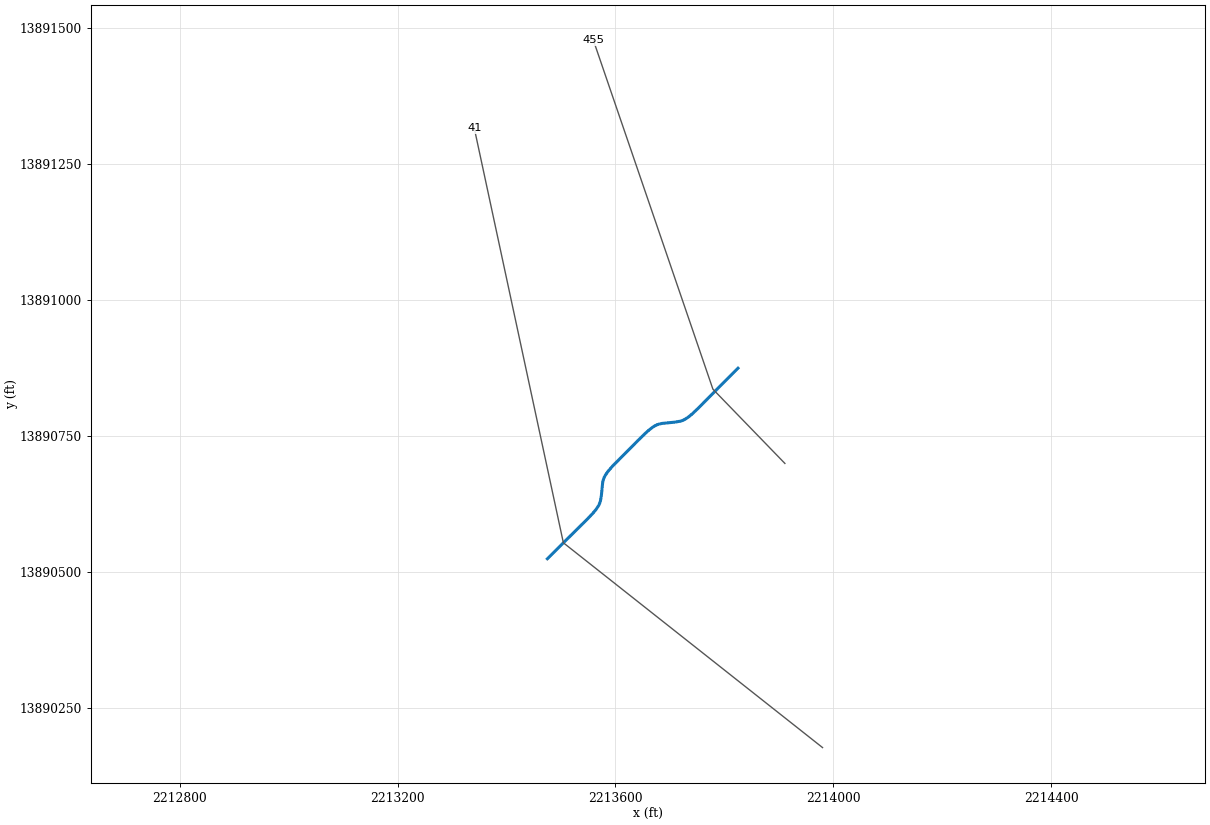
--- Sorrel Tributary 1.prj (project) ---

Proj Title=Sorrel Tributary 1 Base Level Engineering
Current Plan=p01
Default Exp/Contr=0.3,0.1
English Units
Geom File=g01
Flow File=f01
Plan File=p01
BEGIN DESCRIPTION:
Sorrel Tributary 1
END DESCRIPTION:

--- Sorrel Tributary 1.p01 (plan) ---

Plan Title=Multiple Run
Short Identifier=Multiple
Geom File=g01
Flow File=f01
Subcritical Flow
K Sum by GR= 0
Std Step Tol= 0.01
Critical Tol= 0.01
Num of Std Step Trials= 20
Max Error Tol= 0.3
Flow Tol Ratio= 0.001
Split Flow NTrial= 30
Split Flow Tol= 0.02
Split Flow Ratio= 0.02
Log Output Level= 0
Friction Slope Method= 1
Unsteady Friction Slope Method= 2
Unsteady Bridges Friction Slope Method= 1
Parabolic Critical Depth
Global Vel Dist=  1 , 1 , 1
Global Log Level= 0
CheckData=True
Encroach Param= -1, 0, 0, 0
BEGIN DESCRIPTION:
Multiple Run
END DESCRIPTION:

--- Sorrel Tributary 1.f01 (steady flow) ---

Flow Title=Multiple
Number of Profiles=7
Profile Names=10-year,25-year,50-year,1pct_min,100-year,1pct_plu,500-year
River Rch & RM= Sorrel Tributary,Reach-1,455
     638    1047    1426     945    1885    3760    3248
Boundary for River Rch & Prof#=Sorrel Tributary,Reach-1,1
Up Type=0
Dn Type=3
Dn Slope=0.005
Boundary for River Rch & Prof#=Sorrel Tributary,Reach-1,2
Up Type=0
Dn Type=3
Dn Slope=0.005
Boundary for River Rch & Prof#=Sorrel Tributary,Reach-1,3
Up Type=0
Dn Type=3
Dn Slope=0.005
Boundary for River Rch & Prof#=Sorrel Tributary,Reach-1,4
Up Type=0
Dn Type=3
Dn Slope=0.005
Boundary for River Rch & Prof#=Sorrel Tributary,Reach-1,5
Up Type=0
Dn Type=3
Dn Slope=0.005
Boundary for River Rch & Prof#=Sorrel Tributary,Reach-1,6
Up Type=0
Dn Type=3
Dn Slope=0.005
Boundary for River Rch & Prof#=Sorrel Tributary,Reach-1,7
Up Type=0
Dn Type=3
Dn Slope=0.005

--- Sorrel Tributary 1.g01 (geometry) ---

Geom Title=Existing Conditions

River Reach=Sorrel Tributary,Reach-1
Reach XY= 30
      2213825.00     13890875.00      2213751.86     13890801.20
      2213741.71     13890791.57      2213734.70     13890785.72
      2213727.30     13890780.82      2213723.36     13890778.95
      2213718.95     13890777.52      2213709.63     13890775.88
      2213685.63     13890773.47      2213681.03     13890772.48
      2213676.63     13890771.04      2213672.69     13890769.16
      2213668.93     13890766.86      2213661.76     13890761.38
      2213654.87     13890755.23      2213641.42     13890742.08
      2213594.77     13890695.13      2213585.76     13890684.70
      2213580.84     13890677.31      2213578.96     13890673.37
      2213577.52     13890668.97      2213576.53     13890664.37
      2213574.12     13890640.37      2213572.48     13890631.05
      2213571.05     13890626.64      2213569.18     13890622.70
      2213564.28     13890615.30      2213558.43     13890608.29
      2213548.80     13890598.14      2213475.00     13890525.00

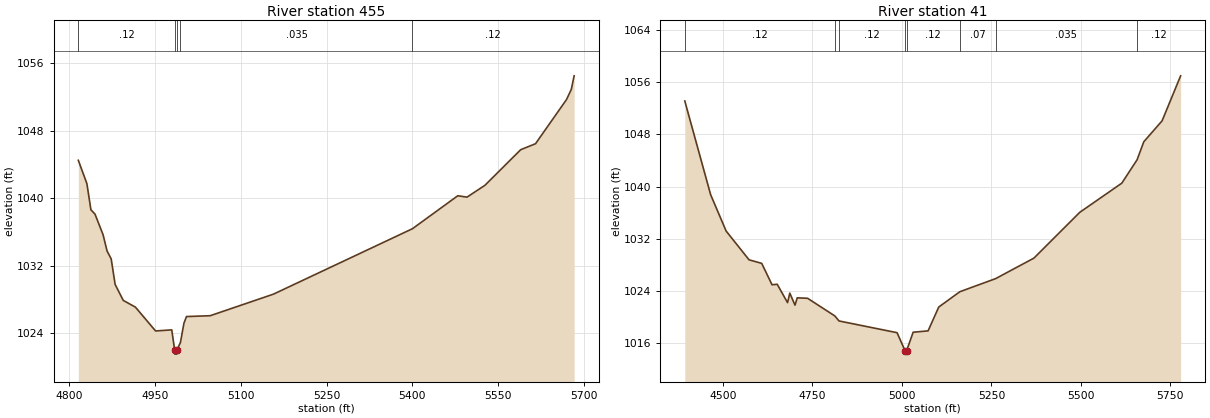
Type RM Length L Ch R = 1,455,414,414,414
BEGIN DESCRIPTION:
Sorrel Tributary 1 2.0
END DESCRIPTION:
XS GIS Cut Line= 3
      2213911.23     13890700.00      2213779.02     13890836.41
      2213559.36     13891477.67
#Sta/Elev= 30
  4815.5 1044.50  4830.5 1041.73  4837.5 1038.63  4844.7 1038.11  4858.8 1035.67
  4865.8 1033.73  4873.0 1032.80  4879.9 1029.77  4894.1 1027.87  4915.4 1027.07
  4950.7 1024.24  4979.0 1024.37  4984.1 1021.99  4984.4 1021.49  4987.9 1021.49
  4988.1 1021.99  4994.2 1022.87  5000.3 1025.15  5004.8 1025.95  5046.3 1026.05
  5157.0 1028.61  5400.3 1036.38  5479.6 1040.29  5495.8 1040.13  5527.1 1041.53
  5589.7 1045.76  5615.7 1046.47  5669.9 1051.71  5678.3 1052.92  5683.3 1054.53
#Mann=5,-1,0
  4815.5    0.12       0  4984.1   0.035       0  4988.1    0.12       0
  4994.2   0.035       0  5400.3    0.12       0
Bank Sta=4984.1,4988.1
Exp/Cntr=0.3,0.1

Type RM Length L Ch R = 1,41,0,0,0
BEGIN DESCRIPTION:
Sorrel Tributary 1 1.0
END DESCRIPTION:
XS GIS Cut Line= 3
      2213980.38     13890178.19      2213504.42     13890554.27
      2213340.82     13891315.59
#Sta/Elev= 30
  4393.4 1053.13  4465.6 1038.75  4508.9 1033.17  4573.0 1028.75  4608.3 1028.21
  4637.1 1024.93  4651.6 1025.00  4680.5 1022.18  4686.8 1023.64  4701.3 1021.80
  4707.6 1022.92  4736.5 1022.85  4812.6 1020.14  4824.3 1019.37  4986.5 1017.57
  5009.0 1014.78  5009.2 1014.28  5013.0 1014.78  5031.4 1017.64  5073.1 1017.85
  5103.0 1021.51  5162.0 1023.86  5262.0 1025.87  5369.0 1029.02  5496.9 1036.04
  5614.4 1040.52  5657.1 1044.11  5675.8 1046.87  5727.0 1050.09  5778.7 1056.99
#Mann=8,-1,0
  4393.4    0.12       0  4812.6   0.035       0  4824.3    0.12       0
  5009.0    0.05       0  5013.0    0.12       0  5162.0    0.07       0
  5262.0   0.035       0  5657.1    0.12       0
Bank Sta=5009,5013
Exp/Cntr=0.3,0.1

Chan Stop Cuts=-1