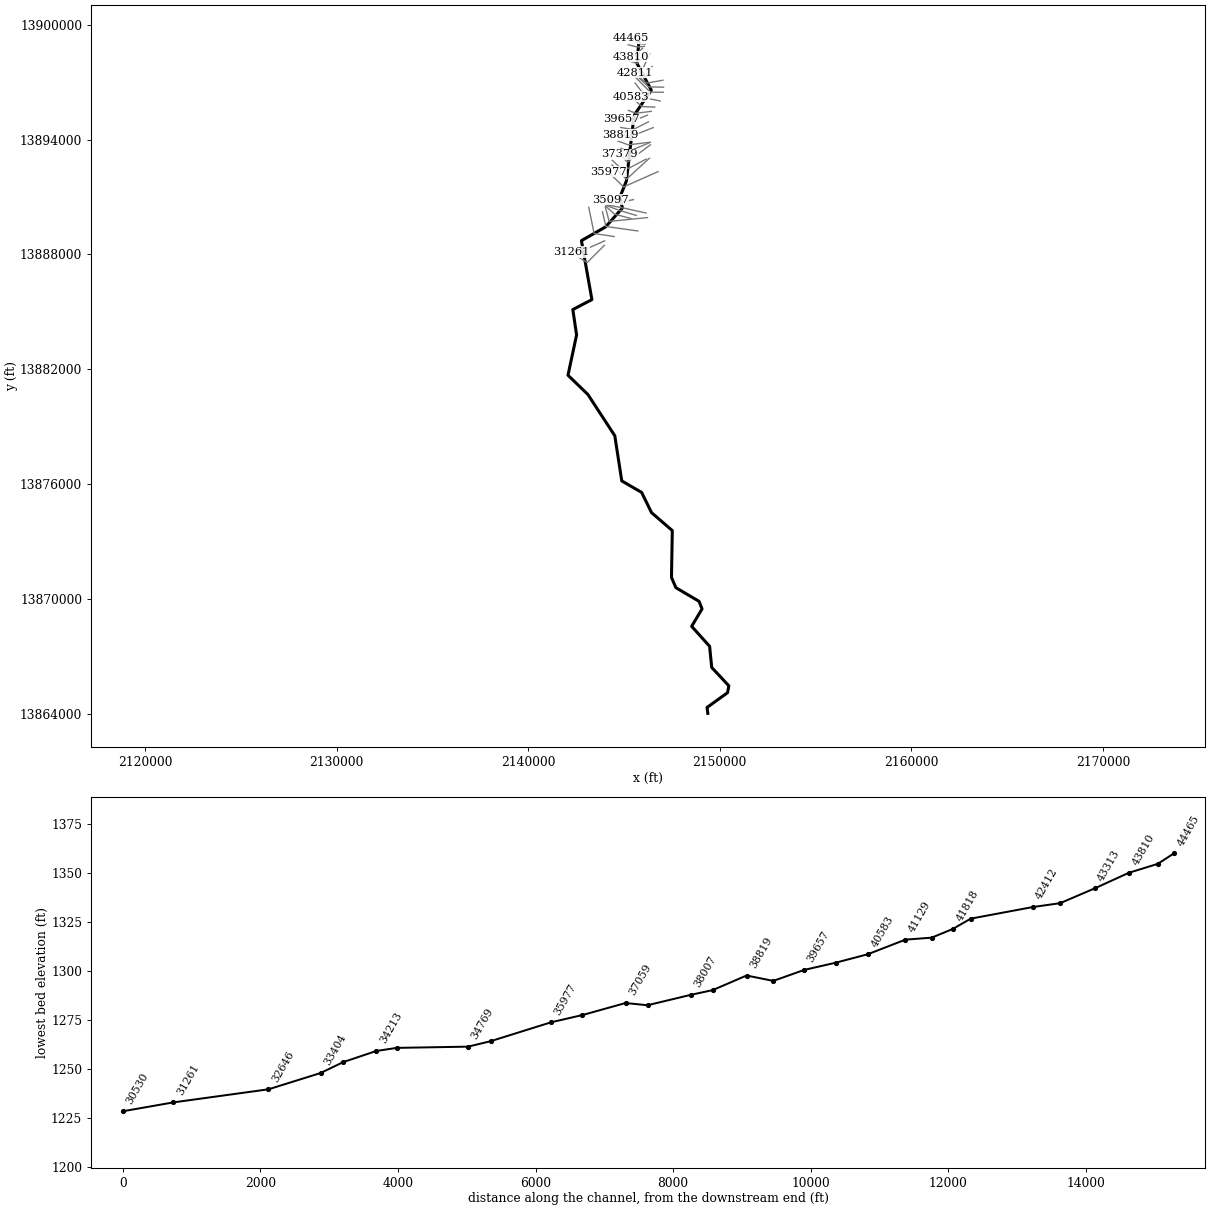
--- Spring Branch.prj (project) ---

Proj Title=Spring Branch Base Level Engineering
Current Plan=p01
Default Exp/Contr=0.3,0.1
English Units
Geom File=g01
Flow File=f01
Plan File=p01
Y Axis Title=Elevation
X Axis Title(PF)=Main Channel Distance
X Axis Title(XS)=Station
BEGIN DESCRIPTION:
Spring Branch
END DESCRIPTION:
DSS Export Rating Curves= 0
DSS Export Rating Curve Sorted= 0
DSS Export Volume Flow Curves= 0
DXF OffsetX= 0
DXF OffsetY= 0
DXF ScaleX= 1
DXF ScaleY= 10

--- Spring Branch.p01 (plan) ---

Plan Title=Multiple Run
Short Identifier=Multiple
Geom File=g01
Flow File=f01
Subcritical Flow
K Sum by GR= 0
Std Step Tol= 0.01
Critical Tol= 0.01
Num of Std Step Trials= 20
Max Error Tol= 0.3
Flow Tol Ratio= 0.001
Split Flow NTrial= 30
Split Flow Tol= 0.02
Split Flow Ratio= 0.02
Log Output Level= 0
Friction Slope Method= 1
Unsteady Friction Slope Method= 2
Unsteady Bridges Friction Slope Method= 1
Parabolic Critical Depth
Global Vel Dist=  1 , 1 , 1
Global Log Level= 0
CheckData=True
Encroach Param= -1, 0, 0, 0
BEGIN DESCRIPTION:
Multiple Run
END DESCRIPTION:

--- Spring Branch.f01 (steady flow) ---

Flow Title=Multiple
Program Version=4.10
Number of Profiles= 7
Profile Names=10-year,25-year,50-year,1pct_min,100-year,1pct_plu,500-year
River Rch & RM=Spring Branch,Reach-1         ,44465
    1325    2293    3236    2215    4419    8818    8150
River Rch & RM=Spring Branch,Reach-1         ,41511
    2018    3558    5079    3508    7000   13968   13167
River Rch & RM=Spring Branch,Reach-1         ,31261
    3738    6786    9880    6945   13858   27649   27008
River Rch & RM=Spring Branch,Reach-1         ,26309
    4406    8026   11710    8242   16445   32812   32135
River Rch & RM=Spring Branch,Reach-1         ,20415
    4757    8686   12691    8944   17845   35605   34956
River Rch & RM=Spring Branch,Reach-1         ,14615
    5404    9927   14560   10293   20537   40977   40503
River Rch & RM=Spring Branch,Reach-1         ,8119
    5748   10577   15531   10989   21927   43749   43323
River Rch & RM=Spring Branch,Reach-1         ,6102
    5808   10670   15649   11059   22066   44028   43487
Boundary for River Rch & Prof#=Spring Branch,Reach-1         , 1
Up Type= 0
Dn Type= 3
Dn Slope=0.01
Boundary for River Rch & Prof#=Spring Branch,Reach-1         , 2
Up Type= 0
Dn Type= 3
Dn Slope=0.01
Boundary for River Rch & Prof#=Spring Branch,Reach-1         , 3
Up Type= 0
Dn Type= 3
Dn Slope=0.01
Boundary for River Rch & Prof#=Spring Branch,Reach-1         , 4
Up Type= 0
Dn Type= 3
Dn Slope=0.01
Boundary for River Rch & Prof#=Spring Branch,Reach-1         , 5
Up Type= 0
Dn Type= 3
Dn Slope=0.01
Boundary for River Rch & Prof#=Spring Branch,Reach-1         , 6
Up Type= 0
Dn Type= 3
Dn Slope=0.01
Boundary for River Rch & Prof#=Spring Branch,Reach-1         , 7
Up Type= 0
Dn Type= 3
Dn Slope=0.01
DSS Import GetInterval= 0
DSS Import GetPeak= 0
DSS Import FillOption= 0

--- Spring Branch.g01 (geometry) ---

Geom Title=Existing Conditions
Program Version=4.10

River Reach=Spring Branch   ,Reach-1
Reach XY= 30
        2145775.       13899075.      2145677.06     13897980.86
      2146423.84     13896584.57      2145527.06     13895269.15
      2145123.63     13891834.67       2144775.5     13890959.78
      2144921.57     13890426.23      2144034.81     13889435.51
      2142776.94     13888719.68      2143324.76     13885640.21
      2142327.38     13885119.47      2142525.04     13883794.98
      2142075.39     13881690.16      2143114.23      13880684.7
      2144519.89     13878527.29      2144883.16     13876168.95
      2145919.42     13875569.42      2146438.48     13874511.44
      2147521.39     13873573.52      2147478.62      13871126.5
      2147707.95     13870591.49      2148919.58     13869877.67
      2149073.38     13869481.03      2148532.79     13868571.58
      2149469.61     13867527.69      2149580.13     13866422.72
      2150473.95     13865464.57      2150405.24     13865104.58
      2149335.63       13864335.        2149375.       13864025.

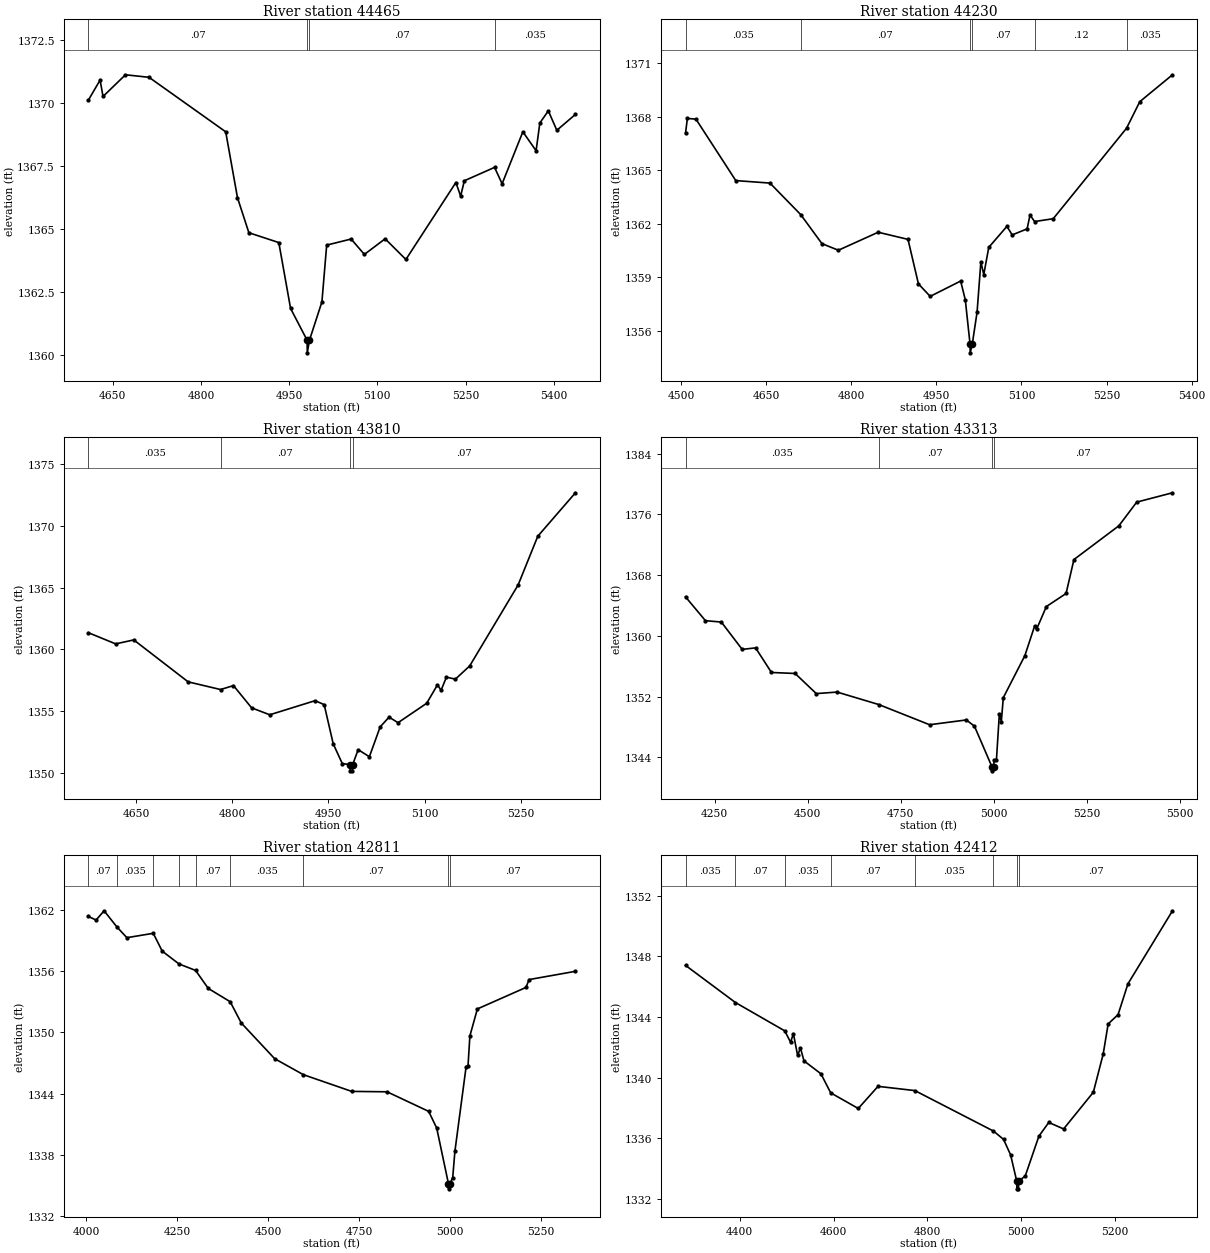
Type RM Length L Ch R = 1 ,44465   ,235,235,235
BEGIN DESCRIPTION:
Spring Branch 86.0
END DESCRIPTION:
XS GIS Cut Line= 3
      2146117.66     13898988.29      2145727.56     13899018.94
      2145383.91     13899288.57
#Sta/Elev= 30
  4608.7 1370.12  4628.5 1370.91  4633.5 1370.26  4671.6 1371.12  4711.7 1371.02
  4842.1 1368.86  4862.1 1366.25  4881.5 1364.86  4932.4 1364.47  4952.4 1361.86
  4980.5  1360.6  4980.8  1360.1  4984.5  1360.6  5005.7 1362.12  5013.8 1364.37
  5055.4 1364.61  5077.9    1364  5113.2 1364.62  5148.5  1363.8  5233.5 1366.85
  5241.6 1366.31  5247.9 1366.92  5299.3 1367.45  5312.1  1366.8  5347.4 1368.86
  5369.9 1368.11  5376.3 1369.21  5390.7 1369.69  5405.2 1368.92  5436.8 1369.55
#Mann= 4 ,-1 , 0
  4608.7     .07       0  4980.5     .05       0  4984.5     .07       0
  5299.3    .035       0
Bank Sta=4980.5,4984.5
XS Rating Curve= 0 ,0
Exp/Cntr=0.3,0.1

Type RM Length L Ch R = 1 ,44230   ,420,420,420
BEGIN DESCRIPTION:
Spring Branch 85.0
END DESCRIPTION:
XS GIS Cut Line= 3
       2146063.3     13898870.27      2145675.72     13898836.93
      2145221.48     13898953.62
#Sta/Elev= 30
  4508.1 1367.07  4511.4 1367.91  4526.5 1367.87  4596.7 1364.42  4656.9 1364.28
  4711.1 1362.51  4748.5 1360.88  4777.4 1360.51  4847.6 1361.52  4900.1 1361.12
  4918.5 1358.62  4939.2 1357.92  4992.9 1358.78  5001.1 1357.72  5009.4 1355.25
  5009.7 1354.75  5013.4 1355.25  5021.8 1357.03  5028.5 1359.86  5033.6 1359.14
  5042.4 1360.67  5074.4 1361.85  5083.7 1361.37    5110 1361.71  5115.1 1362.49
  5123.1 1362.12    5156 1362.28  5285.2 1367.36  5308.5 1368.85  5366.1 1370.36
#Mann= 6 ,-1 , 0
  4508.1    .035       0  4711.1     .07       0  5009.4     .05       0
  5013.4     .07       0  5123.1     .12       0  5285.2    .035       0
Bank Sta=5009.4,5013.4
XS Rating Curve= 0 ,0
Exp/Cntr=0.3,0.1

Type RM Length L Ch R = 1 ,43810   ,497,497,497
BEGIN DESCRIPTION:
Spring Branch 84.0
END DESCRIPTION:
XS GIS Cut Line= 3
      2145974.97     13898774.97        2145675.       13898475.
      2145375.03     13898325.02
#Sta/Elev= 30
  4575.8 1361.35  4618.2 1360.45  4646.5 1360.77  4731.3 1357.38  4781.9 1356.76
    4802 1357.08  4830.3 1355.28  4858.6 1354.72  4929.3 1355.86  4943.5 1355.54
  4957.6 1352.37  4971.7 1350.78  4983.9 1350.69  4984.1 1350.19  4987.6 1350.19
  4987.9 1350.69  4996.5  1351.9    5014 1351.33  5030.8 1353.74  5044.7 1354.53
  5058.7 1354.08  5103.4 1355.65  5120.2 1357.14  5125.8  1356.7  5134.2 1357.76
  5148.2  1357.6  5170.5 1358.67    5246 1365.21  5276.7 1369.15  5335.4 1372.66
#Mann= 4 ,-1 , 0
  4575.8    .035       0  4781.9     .07       0  4983.9     .05       0
  4987.9     .07       0
Bank Sta=4983.9,4987.9
XS Rating Curve= 0 ,0
Exp/Cntr=0.3,0.1

Type RM Length L Ch R = 1 ,43313   ,502,502,502
BEGIN DESCRIPTION:
Spring Branch 83.0
END DESCRIPTION:
XS GIS Cut Line= 3
      2146226.49     13898599.06        2145675.       13897975.
       2145223.9     13898125.93
#Sta/Elev= 30
  4171.6 1365.13  4225.2 1361.99  4267.9 1361.81  4323.9 1358.21  4359.9 1358.41
  4402.6 1355.17  4466.1 1355.04    4523 1352.39    4579 1352.59  4690.8 1350.95
  4827.5 1348.29  4926.2 1348.92    4948  1348.1  4995.3 1342.72  4995.6 1342.22
  4999.3 1342.72  5001.1 1343.68  5007.1 1343.68  5014.9 1349.74  5020.2 1348.69
  5025.5 1351.85  5083.4 1357.38  5109.7 1361.29  5114.9 1360.86  5141.2 1363.85
  5194.2 1365.57  5215.3 1370.04    5336 1374.48    5384  1377.6  5480.1 1378.83
#Mann= 4 ,-1 , 0
  4171.6    .035       0  4690.8     .07       0  4995.3     .05       0
  4999.3     .07       0
Bank Sta=4995.3,4999.3
XS Rating Curve= 0 ,0
Exp/Cntr=0.3,0.1

Type RM Length L Ch R = 1 ,42811   ,399,399,399
BEGIN DESCRIPTION:
Spring Branch 82.0
END DESCRIPTION:
XS GIS Cut Line= 3
      2146345.16     13898484.03      2145927.78     13897581.47
      2145592.82     13897500.95
#Sta/Elev= 30
  4005.6 1361.38  4026.6 1361.03  4048.6 1361.94  4083.7 1360.36  4111.2  1359.3
  4183.8 1359.73  4208.4 1357.98  4254.7 1356.72  4300.1 1356.09  4335.1 1354.32
  4395.2 1353.02  4425.8 1350.93  4517.5 1347.43  4596.5 1345.86  4729.4 1344.22
  4826.6 1344.18    4941 1342.26  4963.1 1340.62  4995.4 1335.16  4995.6 1334.66
  4999.4 1335.16  5007.1 1335.76  5013.1 1338.34    5044 1346.66  5049.1 1346.69
  5054.3 1349.66  5074.9 1352.31  5208.6 1354.42    5217 1355.19  5344.5    1356
#Mann= 9 ,-1 , 0
  4005.6     .07       0  4083.7    .035       0  4183.8     .07       0
  4254.7    .035       0  4300.1     .07       0  4395.2    .035       0
  4596.5     .07       0  4995.4     .05       0  4999.4     .07       0
Bank Sta=4995.4,4999.4
XS Rating Curve= 0 ,0
Exp/Cntr=0.3,0.1

Type RM Length L Ch R = 1 ,42412   ,901,901,901
BEGIN DESCRIPTION:
Spring Branch 81.0
END DESCRIPTION:
XS GIS Cut Line= 3
      2146474.98     13897824.98        2146075.       13897225.
      2145775.01       13897325.
#Sta/Elev= 30
  4284.6 1347.41  4390.9 1344.96    4496 1343.09  4508.4 1342.34  4514.4 1342.91
  4523.4 1341.47  4529.4 1341.96    4537 1341.11    4573 1340.26  4593.9    1339
  4652.6 1337.97  4694.7 1339.43  4773.2 1339.15  4940.6 1336.48  4962.1 1335.93
  4977.1 1334.91  4990.2 1333.17  4990.4 1332.67  4993.9 1332.67  4994.2 1333.17
  5008.3 1333.52  5037.3 1336.14  5058.4 1337.05    5090 1336.62  5153.3 1339.04
  5174.3 1341.56  5184.9 1343.55    5206 1344.16    5227 1346.19  5321.9 1351.01
#Mann= 8 ,-1 , 0
  4284.6    .035       0  4390.9     .07       0    4496    .035       0
  4593.9     .07       0  4773.2    .035       0  4940.6     .07       0
  4990.2     .05       0  4994.2     .07       0
Bank Sta=4990.2,4994.2
XS Rating Curve= 0 ,0
Exp/Cntr=0.3,0.1

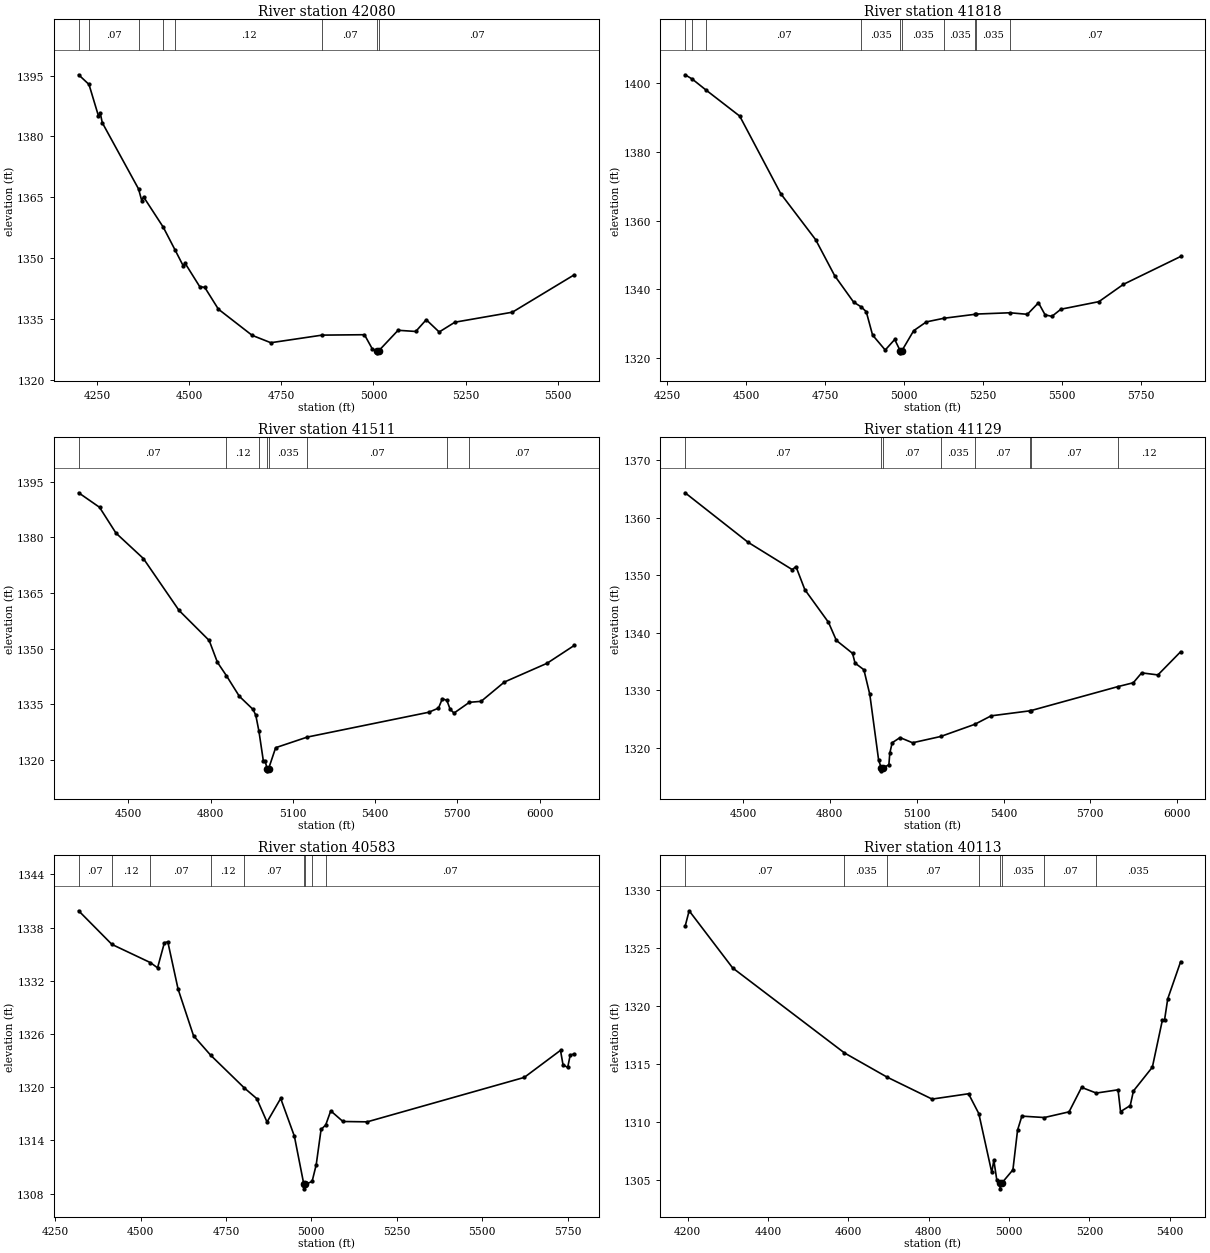
Type RM Length L Ch R = 1 ,42080   ,262,262,262
BEGIN DESCRIPTION:
Spring Branch 80.4
END DESCRIPTION:
XS GIS Cut Line= 4
      2147028.14     13897100.33      2146238.16      13896958.3
      2146134.06      13896975.2      2145804.37      13897260.8
#Sta/Elev= 30
  4200.4 1395.18  4228.5  1392.8    4254  1385.1  4259.1 1385.75  4264.5 1383.39
  4362.9 1367.09  4371.5 1364.24  4376.6 1365.12    4430 1357.67  4462.5 1351.98
  4483.9  1348.2    4489 1348.83  4528.7 1343.07  4542.7 1342.84  4579.5  1337.5
    4671 1331.06  4721.8 1329.24  4860.9 1331.11  4975.8 1331.21  4997.3 1327.68
  5010.5 1327.25  5010.7 1326.75  5014.5 1327.25    5067  1332.3  5114.9 1332.01
  5143.4  1334.9  5178.5 1331.88  5221.2 1334.29    5377 1336.75  5544.7 1345.94
#Mann= 8 ,-1 , 0
  4200.4     .12       0  4228.5     .07       0  4362.9     .12       0
    4430     .07       0  4462.5     .12       0  4860.9     .07       0
  5010.5     .05       0  5014.5     .07       0
Bank Sta=5010.5,5014.5
XS Rating Curve= 0 ,0
Exp/Cntr=0.3,0.1

Type RM Length L Ch R = 1 ,41818   ,307,307,307
BEGIN DESCRIPTION:
Spring Branch 80.2
END DESCRIPTION:
XS GIS Cut Line= 5
      2147067.78     13896736.41      2146375.01       13896750.
      2146280.63      13896753.9      2146151.82     13896874.72
       2145709.9     13897285.32
#Sta/Elev= 30
  4307.1 1402.44  4329.6  1401.2    4374 1397.94  4479.9  1390.4  4609.9 1367.77
    4720 1354.41    4780 1343.95    4840 1336.24    4864 1334.84    4880 1333.45
    4900 1326.64    4940 1322.28    4970 1325.35    4988 1321.96  4988.3 1321.46
    4992 1321.96    5030 1327.91  5070.1 1330.47  5125.5 1331.53  5224.5 1332.69
  5226.9 1332.75  5334.5 1333.13  5389.6 1332.68  5424.7 1336.04  5445.7 1332.51
  5467.2 1332.09  5495.6 1334.16  5615.8 1336.37  5693.4 1341.41  5874.3 1349.52
#Mann= 10 ,-1 , 0
  4307.1     .07       0  4329.6     .12       0    4374     .07       0
    4864    .035       0    4988     .05       0    4992    .035       0
  5125.5    .035       0  5224.5     .07       0  5226.9    .035       0
  5334.5     .07       0
Bank Sta=4988,4992
XS Rating Curve= 0 ,0
Exp/Cntr=0.3,0.1

Type RM Length L Ch R = 1 ,41511   ,382,382,382
BEGIN DESCRIPTION:
Spring Branch 80.0
END DESCRIPTION:
XS GIS Cut Line= 3
      2147051.16     13896472.29        2146375.       13896475.
      2145575.02     13897274.98
#Sta/Elev= 30
  4318.8    1392    4395 1388.09    4455 1381.13    4555 1374.27    4685 1360.28
    4795 1352.17    4825 1346.29  4858.1 1342.65    4905 1337.12    4955 1333.58
    4965 1332.01  4976.4 1327.73  4992.5 1319.72  4998.5 1319.72  5006.9 1317.52
  5007.2 1317.02  5011.4 1317.52  5037.4 1323.26  5153.1 1326.13    5596 1332.82
  5631.4 1333.94  5645.5 1336.47  5661.9 1336.03  5673.8 1333.64  5687.9 1332.59
  5744.1  1335.5  5786.9 1335.76  5871.8 1340.97  6027.3 1346.02  6126.3 1350.82
#Mann= 8 ,-1 , 0
  4318.8     .07       0  4858.1     .12       0  4976.4    .035       0
  5006.9    .035       0  5011.4    .035       0  5153.1     .07       0
  5661.9     .12       0  5744.1     .07       0
Bank Sta=5006.9,5011.4
XS Rating Curve= 0 ,0
Exp/Cntr=0.3,0.1

Type RM Length L Ch R = 1 ,41129   ,546,546,546
BEGIN DESCRIPTION:
Spring Branch 79.0
END DESCRIPTION:
XS GIS Cut Line= 3
       2146890.5     13896016.57      2146200.42     13896155.45
       2145579.9     13896949.54
#Sta/Elev= 30
  4300.1 1364.34  4517.5 1355.74  4670.1 1350.99  4683.1 1351.51  4713.7  1347.5
  4795.3 1341.83  4822.6 1338.68  4878.5 1336.43  4887.1 1334.74  4917.7 1333.58
  4938.1 1329.29  4968.7 1317.83    4978 1316.51  4978.3 1316.01  4982.5 1316.51
    5004 1317.06  5007.2 1319.09  5015.4 1320.89  5042.5 1321.79  5085.9 1320.89
  5182.9 1321.98  5300.4 1324.09  5357.2 1325.57  5492.6 1326.45  5493.3 1326.46
  5794.4 1330.64  5848.3 1331.32  5877.2 1333.04  5933.3 1332.68  6011.8 1336.71
#Mann= 8 ,-1 , 0
  4300.1     .07       0    4978     .05       0  4982.5     .07       0
  5182.9    .035       0  5300.4     .07       0  5492.6    .035       0
  5493.3     .07       0  5794.4     .12       0
Bank Sta=4978,4982.5
XS Rating Curve= 0 ,0
Exp/Cntr=0.3,0.1

Type RM Length L Ch R = 1 ,40583   ,470,470,470
BEGIN DESCRIPTION:
Spring Branch 78.0
END DESCRIPTION:
XS GIS Cut Line= 3
      2146605.76     13895695.39        2145925.       13895725.
      2145361.02     13896247.46
#Sta/Elev= 30
  4318.9 1339.89  4416.3  1336.1  4528.8 1334.05  4549.9 1333.46  4569.9 1336.29
  4579.9 1336.39  4609.9 1331.07  4655.1 1325.81  4705.3 1323.61  4804.1 1319.91
  4840.2 1318.72  4870.2 1316.08  4910.2 1318.74  4950.3 1314.48    4978 1309.05
  4978.3 1308.55  4982.5 1309.05  5002.2 1309.39  5014.2 1311.27  5028.4 1315.24
    5042 1315.75  5056.7 1317.34  5092.4 1316.14  5163.3  1316.1  5623.1 1321.11
  5729.1 1324.16  5736.4 1322.54  5750.1 1322.23  5757.5 1323.62  5769.1 1323.76
#Mann= 9 ,-1 , 0
  4318.9     .07       0  4416.3     .12       0  4528.8     .07       0
  4705.3     .12       0  4804.1     .07       0    4978     .05       0
  4982.5     .07       0  5002.2    .035       0    5042     .07       0
Bank Sta=4978,4982.5
XS Rating Curve= 0 ,0
Exp/Cntr=0.3,0.1

Type RM Length L Ch R = 1 ,40113   ,456,456,456
BEGIN DESCRIPTION:
Spring Branch 77.0
END DESCRIPTION:
XS GIS Cut Line= 3
      2146425.03       13895475.        2145625.       13895375.
      2145224.96     13895525.02
#Sta/Elev= 30
  4193.7 1326.83  4203.8 1328.18  4312.1 1323.25  4590.4 1315.92  4696.2 1313.84
  4808.5 1311.94  4899.2  1312.4  4924.8 1310.69  4957.1 1305.61  4962.2 1306.67
  4969.7 1304.93  4977.5  1304.7  4977.8  1304.2  4982.1  1304.7  5009.7 1305.84
  5021.3 1309.27    5032 1310.47    5088 1310.35  5149.5 1310.84  5180.6 1312.95
  5217.2 1312.46  5271.4 1312.74  5277.6 1310.86  5301.7 1311.38  5309.7 1312.64
  5356.8 1314.69  5381.8 1318.76  5387.1 1318.75  5395.1 1320.59  5427.2 1323.79
#Mann= 8 ,-1 , 0
  4193.7     .07       0  4590.4    .035       0  4696.2     .07       0
  4924.8    .035       0  4977.5    .035       0  4982.1    .035       0
    5088     .07       0  5217.2    .035       0
Bank Sta=4977.5,4982.1
XS Rating Curve= 0 ,0
Exp/Cntr=0.3,0.1

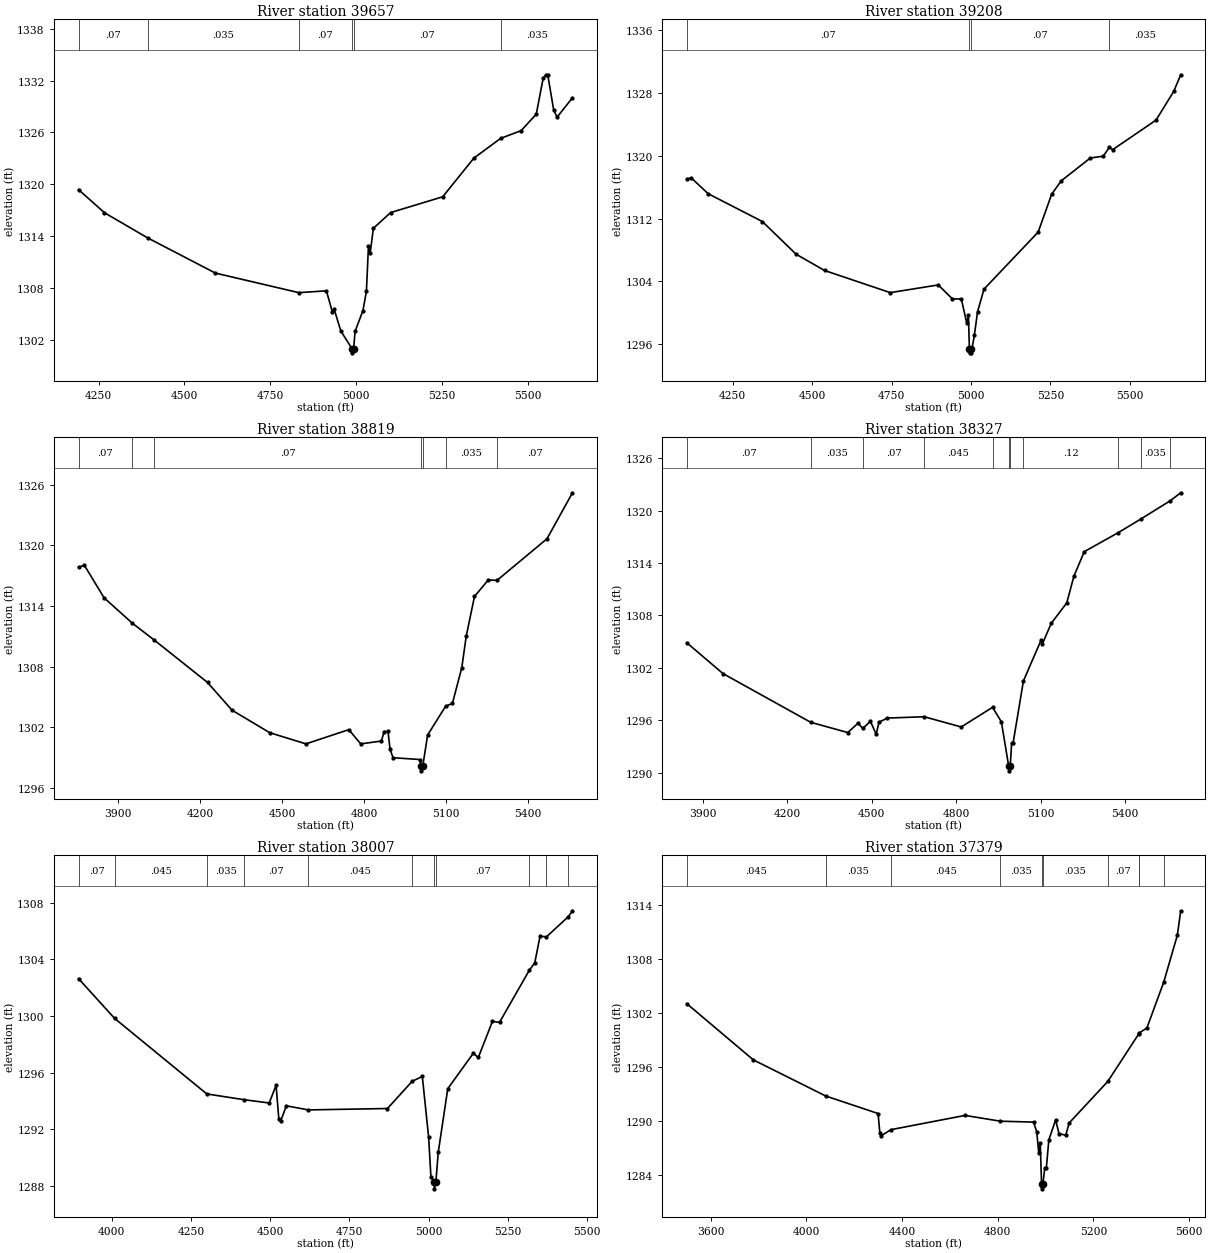
Type RM Length L Ch R = 1 ,39657   ,449,449,449
BEGIN DESCRIPTION:
Spring Branch 76.0
END DESCRIPTION:
XS GIS Cut Line= 3
      2146225.03     13895275.01        2145475.       13894975.
      2144850.57     13895059.97
#Sta/Elev= 30
  4191.8 1319.39  4267.2 1316.72    4393 1313.81  4590.3 1309.74  4833.1 1307.48
  4913.4 1307.69    4931  1305.2  4936.3 1305.54  4955.2 1303.06  4987.6 1301.02
    4988 1300.52  4992.7 1301.02  4996.9    1303  5019.8 1305.41  5029.9 1307.64
  5035.8 1312.83  5040.9 1312.05  5050.1 1314.92  5100.5 1316.74  5251.9 1318.56
  5342.7 1323.03  5420.7 1325.32  5480.3 1326.21  5524.4 1328.11  5544.6  1332.3
  5552.7 1332.67  5557.8 1332.67  5574.9 1328.64    5585 1327.77  5629.8 1330.01
#Mann= 6 ,-1 , 0
  4191.8     .07       0    4393    .035       0  4833.1     .07       0
  4987.6     .05       0  4992.7     .07       0  5420.7    .035       0
Bank Sta=4987.6,4992.7
XS Rating Curve= 0 ,0
Exp/Cntr=0.3,0.1

Type RM Length L Ch R = 1 ,39208   ,389,389,389
BEGIN DESCRIPTION:
Spring Branch 75.0
END DESCRIPTION:
XS GIS Cut Line= 3
        2146275.       13894925.        2145475.       13894525.
      2144824.51     13894632.89
#Sta/Elev= 30
    4106 1317.03    4120 1317.18  4173.1 1315.17  4343.6 1311.63  4449.8 1307.47
  4539.2  1305.4  4746.1 1302.58    4897 1303.56  4941.7 1301.78  4969.7 1301.78
  4986.4 1298.74    4992 1299.71    4995 1295.42  4995.4 1294.92  4999.8 1294.92
  5000.3 1295.42    5003 1295.42  5010.6 1297.15  5020.7 1300.16    5041 1303.03
  5211.3 1310.28  5253.8  1315.1  5284.2 1316.82  5375.5 1319.71    5416 1319.94
  5434.9 1321.05  5446.4 1320.79  5582.1 1324.53    5638  1328.2  5659.8  1330.3
#Mann= 4 ,-1 , 0
    4106     .07       0    4995     .05       0  5000.3     .07       0
  5434.9    .035       0
Bank Sta=4995,5000.3
XS Rating Curve= 0 ,0
Exp/Cntr=0.3,0.1

Type RM Length L Ch R = 1 ,38819   ,492,492,492
BEGIN DESCRIPTION:
Spring Branch 74.0
END DESCRIPTION:
XS GIS Cut Line= 3
      2146525.02     13894625.01      2145371.43     13894169.34
      2144809.45     13894242.19
#Sta/Elev= 30
  3755.6 1317.85  3777.1 1318.02  3848.9 1314.81  3952.1  1312.3  4032.7 1310.62
  4227.6 1306.42  4316.9 1303.68  4454.8 1301.45  4587.4 1300.34  4744.3 1301.75
  4787.8 1300.34  4863.2 1300.62  4873.8 1301.55  4887.6 1301.58  4895.3 1299.81
  4906.1 1298.97  5004.2 1298.79  5009.8 1298.17  5010.2 1297.67  5015.1 1298.17
  5032.7 1301.22  5098.6 1304.07  5123.4 1304.35  5157.7 1307.89  5173.8 1310.99
  5204.1 1314.94  5254.5 1316.57  5286.8 1316.54  5469.5 1320.66  5562.6 1325.21
#Mann= 7 ,-1 , 0
  3755.6     .07       0  3952.1    .035       0  4032.7     .07       0
  5009.8     .05       0  5015.1     .07       0  5098.6    .035       0
  5286.8     .07       0
Bank Sta=5009.8,5015.1
XS Rating Curve= 0 ,0
Exp/Cntr=0.3,0.1

Type RM Length L Ch R = 1 ,38327   ,320,320,320
BEGIN DESCRIPTION:
Spring Branch 73.0
END DESCRIPTION:
XS GIS Cut Line= 3
      2146372.59     13893862.45        2145225.       13893725.
      2144663.13     13893929.75
#Sta/Elev= 30
  3843.8 1304.87  3972.3 1301.34  4283.5 1295.77  4415.4 1294.59  4451.8 1295.66
  4468.5 1295.07    4496 1295.87  4516.2 1294.39  4526.2 1295.78  4556.4 1296.25
  4686.7  1296.4  4818.3 1295.23  4929.5 1297.48  4960.9 1295.81  4986.9 1290.71
  4987.3 1290.21  4992.2 1290.71  4997.1 1293.35  5002.2 1293.35    5039 1300.49
  5101.3 1305.13  5106.6 1304.75  5137.9 1307.09    5193 1309.43  5218.2 1312.47
    5255 1315.29  5374.3 1317.44  5454.8    1319  5560.9 1321.13  5597.6 1322.03
#Mann= 11 ,-1 , 0
  3843.8     .07       0  4283.5    .035       0  4468.5     .07       0
  4686.7    .045       0  4929.5     .07       0  4986.9     .05       0
  4992.2     .07       0    5039     .12       0  5374.3     .07       0
  5454.8    .035       0  5560.9     .07       0
Bank Sta=4986.9,4992.2
XS Rating Curve= 0 ,0
Exp/Cntr=0.3,0.1

Type RM Length L Ch R = 1 ,38007   ,628,628,628
BEGIN DESCRIPTION:
Spring Branch 72.0
END DESCRIPTION:
XS GIS Cut Line= 4
      2146300.86     13893823.52       2145346.5     13893427.61
      2145125.62     13893406.77      2144854.72      13893544.3
#Sta/Elev= 30
  3895.4 1302.64  4009.3 1299.83  4300.1 1294.49  4418.5 1294.08  4497.2 1293.85
  4518.8  1295.1  4527.6  1292.7    4533 1292.55  4551.3 1293.65  4620.7 1293.36
  4870.4 1293.46  4948.2 1295.38  4980.4 1295.73  5000.4 1291.41  5007.5 1288.64
  5017.8 1288.28  5018.2 1287.78  5023.2 1288.28  5030.6 1290.35  5060.7 1294.86
  5141.1 1297.36  5157.2 1297.07  5201.7 1299.62    5224 1299.55  5318.5 1303.25
  5335.3 1303.76  5351.9 1305.64  5372.3  1305.6  5440.6 1307.01  5454.3 1307.44
#Mann= 11 ,-1 , 0
  3895.4     .07       0  4009.3    .045       0  4300.1    .035       0
  4418.5     .07       0  4620.7    .045       0  4948.2     .07       0
  5017.8     .05       0  5023.2     .07       0  5318.5     .12       0
  5372.3     .07       0  5440.6     .12       0
Bank Sta=5017.8,5023.2
XS Rating Curve= 0 ,0
Exp/Cntr=0.3,0.1

Type RM Length L Ch R = 1 ,37379   ,320,320,320
BEGIN DESCRIPTION:
Spring Branch 71.0
END DESCRIPTION:
XS GIS Cut Line= 3
      2146375.02     13893725.02        2145175.       13892825.
      2144775.01     13893224.99
#Sta/Elev= 30
  3499.5 1303.01  3777.7 1296.78  4080.9 1292.77  4299.5 1290.83  4306.8 1288.69
  4313.1 1288.37  4353.1 1289.04  4663.1 1290.62  4810.8 1289.98  4949.5 1289.88
  4963.1 1288.81  4971.4 1286.44  4977.7 1287.55  4983.3 1282.98  4983.7 1282.48
  4988.7 1282.98  4996.4 1284.77  5003.1 1284.77  5013.7 1287.92    5042 1290.12
  5056.1 1288.61  5084.4 1288.42  5098.5 1289.78  5260.3 1294.39    5389 1299.63
  5390.4 1299.74  5423.8 1300.32  5493.8 1305.37  5551.1  1310.6  5565.2 1313.31
#Mann= 10 ,-1 , 0
  3499.5    .045       0  4080.9    .035       0  4353.1    .045       0
  4810.8    .035       0  4983.3    .035       0  4988.7    .035       0
  5260.3     .07       0    5389    .035       0  5390.4     .07       0
  5493.8     .12       0
Bank Sta=4983.3,4988.7
XS Rating Curve= 0 ,0
Exp/Cntr=0.3,0.1

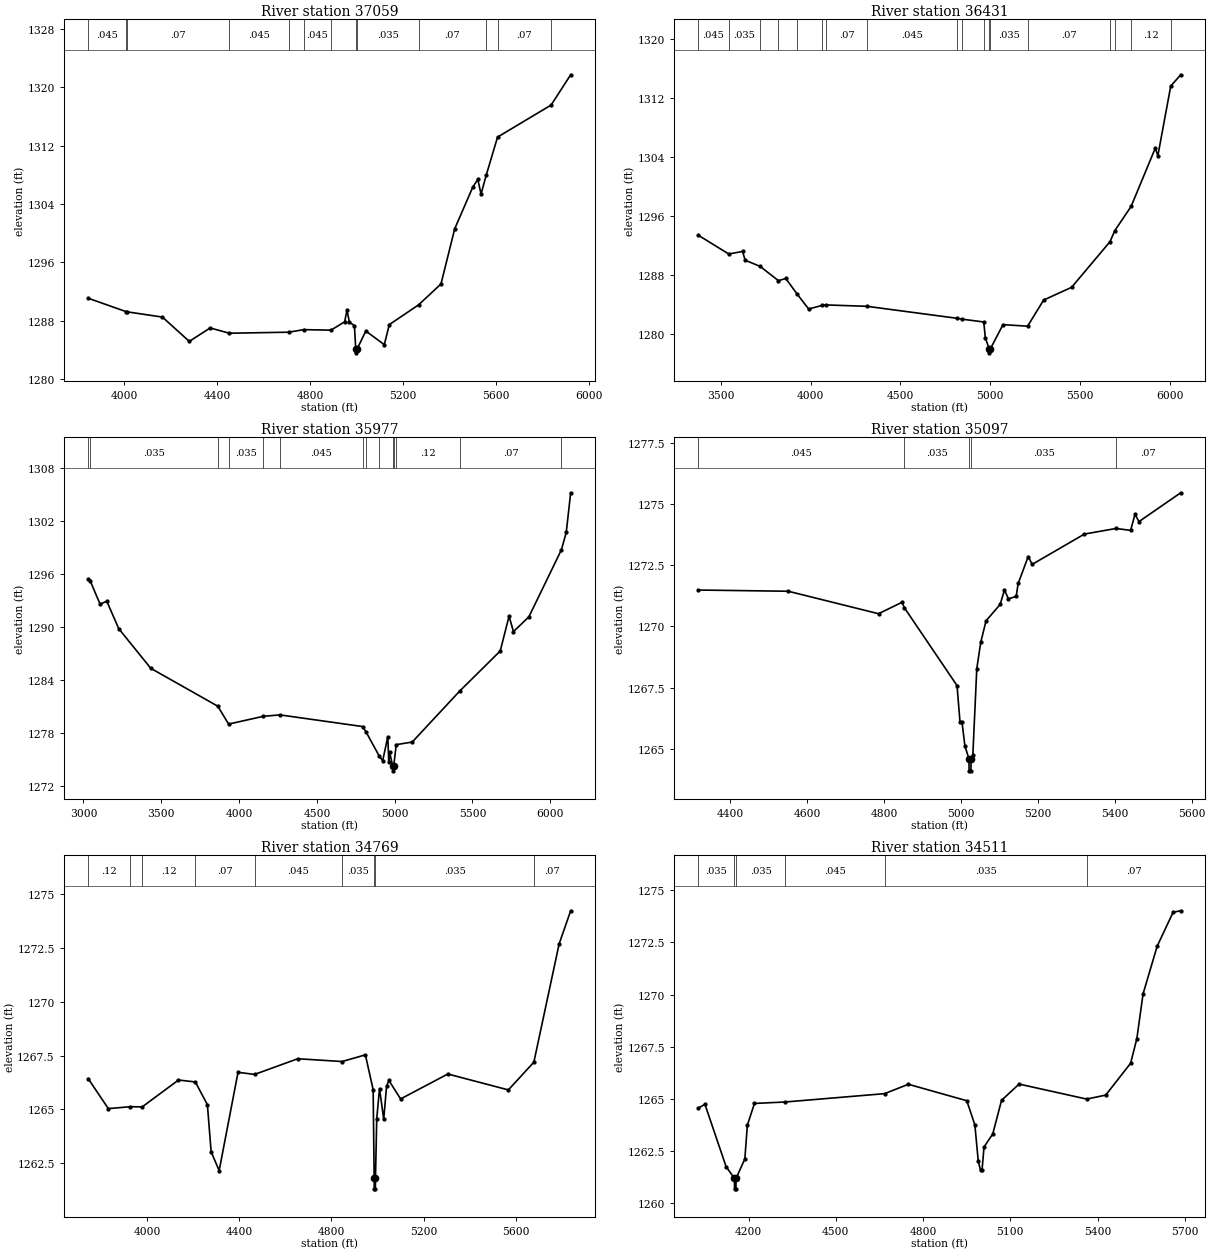
Type RM Length L Ch R = 1 ,37059   ,628,628,628
BEGIN DESCRIPTION:
Spring Branch 70.0
END DESCRIPTION:
XS GIS Cut Line= 4
      2146159.11     13892981.67      2145254.81     13892502.43
      2144750.55     13892577.45      2144355.96     13892951.27
#Sta/Elev= 30
  3845.4 1291.09  4010.6 1289.23  4013.6 1289.22  4165.3  1288.5  4280.9 1285.17
  4370.7 1287.01  4453.4 1286.29  4708.3 1286.43  4773.9 1286.78  4890.4 1286.71
  4949.5 1287.85  4959.6 1289.48  4969.8  1287.8  4991.6 1287.33  4997.3  1284.1
  4997.8  1283.6  5002.8  1284.1  5040.5 1286.59  5120.2 1284.72  5141.6 1287.47
  5267.8 1290.18    5364 1293.04  5423.4 1300.63    5501 1306.32  5522.5 1307.37
  5536.6 1305.36  5558.4 1307.92  5607.6 1313.18  5838.1 1317.57  5922.2 1321.72
#Mann= 13 ,-1 , 0
  3845.4    .045       0  4010.6    .035       0  4013.6     .07       0
  4453.4    .045       0  4708.3    .035       0  4773.9    .045       0
  4890.4    .035       0  4997.3    .035       0  5002.8    .035       0
  5267.8     .07       0  5558.4     .12       0  5607.6     .07       0
  5838.1     .12       0
Bank Sta=4997.3,5002.8
XS Rating Curve= 0 ,0
Exp/Cntr=0.3,0.1

Type RM Length L Ch R = 1 ,36431   ,454,454,454
BEGIN DESCRIPTION:
Spring Branch 69.0
END DESCRIPTION:
XS GIS Cut Line= 3
      2146325.02     13893025.01        2145125.       13891925.
      2144374.97     13892675.03
#Sta/Elev= 30
  3372.7 1293.39    3543 1290.84  3620.3 1291.18  3634.5    1290  3718.3 1289.15
  3819.8 1287.23  3861.1 1287.52  3923.6 1285.43  3988.4 1283.39  4064.4 1283.88
  4085.1 1283.94  4313.8 1283.75  4814.9 1282.13  4843.6 1282.01  4964.1 1281.63
  4972.5 1279.52  4994.5 1277.95  4994.9 1277.45    5000 1277.95  5071.3 1281.27
  5208.3 1281.06  5297.6  1284.6  5453.2 1286.32  5667.3  1292.5  5694.2    1294
    5785 1297.28  5919.8 1305.18    5934 1304.14  6005.8 1313.58  6061.3 1315.11
#Mann= 18 ,-1 , 0
  3372.7    .045       0    3543    .035       0  3718.3     .07       0
  3819.8    .035       0  3923.6     .07       0  4064.4    .035       0
  4085.1     .07       0  4313.8    .045       0  4814.9    .035       0
  4843.6    .045       0  4964.1    .035       0  4994.5    .035       0
    5000    .035       0  5208.3     .07       0  5667.3    .035       0
  5694.2     .07       0    5785     .12       0  6005.8     .07       0
Bank Sta=4994.5,5000
XS Rating Curve= 0 ,0
Exp/Cntr=0.3,0.1

Type RM Length L Ch R = 1 ,35977   ,880,880,880
BEGIN DESCRIPTION:
Spring Branch 68.0
END DESCRIPTION:
XS GIS Cut Line= 3
      2146774.97     13892324.99        2144975.       13891525.
      2144175.01     13892324.99
#Sta/Elev= 30
  3029.8  1295.4  3042.4 1295.26  3106.4  1292.6  3150.1 1292.91  3226.7 1289.82
  3432.6 1285.34  3863.4 1281.06  3932.6 1279.04  4156.1 1279.92  4262.5 1280.08
  4794.6 1278.76  4817.3 1278.11    4901 1275.42  4922.9  1274.9  4955.8 1277.62
  4961.9 1274.79  4967.4 1275.87  4987.8 1274.26  4988.3 1273.76  4993.4 1274.26
  5010.1 1276.72  5112.7 1277.01  5417.6 1282.77  5678.4  1287.3  5734.9 1291.23
  5763.2 1289.49  5862.2 1291.15  6071.7 1298.74  6102.6 1300.71  6130.9 1305.17
#Mann= 14 ,-1 , 0
  3029.8     .07       0  3042.4    .035       0  3863.4     .07       0
  3932.6    .035       0  4156.1     .07       0  4262.5    .045       0
  4794.6    .035       0  4817.3    .045       0    4901     .07       0
  4987.8     .05       0  4993.4     .07       0  5010.1     .12       0
  5417.6     .07       0  6071.7    .035       0
Bank Sta=4987.8,4993.4
XS Rating Curve= 0 ,0
Exp/Cntr=0.3,0.1

Type RM Length L Ch R = 1 ,35097   ,328,328,328
BEGIN DESCRIPTION:
Spring Branch 67.0
END DESCRIPTION:
XS GIS Cut Line= 3
       2145494.6     13890863.36        2144825.       13890725.
      2144269.46     13890859.75
#Sta/Elev= 30
  4316.2 1271.49  4550.7 1271.44  4785.5 1270.52  4846.8 1270.99  4852.5 1270.77
  4989.7 1267.58  4997.4  1266.1  5002.5  1266.1  5010.2 1265.11  5020.6 1264.59
  5021.1 1264.09  5025.8 1264.09  5026.3 1264.59  5030.8 1264.73  5041.1 1268.27
  5051.4 1269.35  5065.2 1270.23  5101.9  1270.9  5113.1 1271.49  5123.4 1271.13
  5143.6 1271.23  5148.8 1271.76  5174.9 1272.86  5185.2 1272.54  5321.1 1273.78
  5403.7 1274.01  5441.3 1273.93  5452.7 1274.59    5463 1274.29  5571.6 1275.47
#Mann= 5 ,-1 , 0
  4316.2    .045       0  4852.5    .035       0  5020.6    .035       0
  5026.3    .035       0  5403.7     .07       0
Bank Sta=5020.6,5026.3
XS Rating Curve= 0 ,0
Exp/Cntr=0.3,0.1

Type RM Length L Ch R = 1 ,34769   ,1038,1038,1038
BEGIN DESCRIPTION:
Spring Branch 66.0
END DESCRIPTION:
XS GIS Cut Line= 3
      2146150.85     13890165.44      2144923.88     13890434.42
      2144099.34     13890588.95
#Sta/Elev= 30
  3743.9 1266.43  3831.8 1265.03  3927.3 1265.12  3978.7 1265.11  4136.3 1266.36
  4209.5 1266.27  4261.8 1265.21    4278 1263.02  4312.9 1262.15  4394.8 1266.72
  4466.6 1266.62  4654.2 1267.35  4846.3 1267.22  4947.7 1267.53  4981.4 1265.91
  4985.8  1261.8  4986.2  1261.3    4991  1261.3  4991.5  1261.8  4996.9 1264.55
    5009 1265.96  5027.3 1264.54  5039.6 1266.07  5049.7 1266.34  5100.6 1265.48
  5305.5 1266.64  5568.4  1265.9  5679.1 1267.19  5788.8 1272.69  5838.9 1274.23
#Mann= 9 ,-1 , 0
  3743.9     .12       0  3927.3     .07       0  3978.7     .12       0
  4209.5     .07       0  4466.6    .045       0  4846.3    .035       0
  4985.8    .035       0  4991.5    .035       0  5679.1     .07       0
Bank Sta=4985.8,4991.5
XS Rating Curve= 0 ,0
Exp/Cntr=0.3,0.1

Type RM Length L Ch R = 1 ,34511   ,298,298,298
BEGIN DESCRIPTION:
Spring Branch 65.4
END DESCRIPTION:
XS GIS Cut Line= 3
      2145646.96      13890034.7      2144714.94     13890315.14
      2144074.01     13890558.58
#Sta/Elev= 30
  4026.7 1264.54    4050 1264.73  4122.7 1261.74  4151.4 1261.17  4151.8 1260.67
  4156.6 1260.67  4157.1 1261.17  4187.3 1262.11  4195.8 1263.72  4220.3 1264.77
  4326.4 1264.84  4667.7 1265.24  4749.3 1265.69  4950.2  1264.9    4978 1263.74
  4989.5 1262.02  4997.4 1261.56  5002.6 1261.56  5009.5 1262.68  5039.6 1263.31
  5069.7 1264.92    5130  1265.7  5362.2 1264.98  5427.8 1265.17  5513.4  1266.7
  5534.8 1267.88  5556.2 1270.03  5604.7 1272.32  5659.6 1273.95  5685.6 1274.02
#Mann= 6 ,-1 , 0
  4026.7    .035       0  4151.4    .035       0  4157.1    .035       0
  4326.4    .045       0  4667.7    .035       0  5362.2     .07       0
Bank Sta=4151.4,4157.1
XS Rating Curve= 0 ,0
Exp/Cntr=0.3,0.1

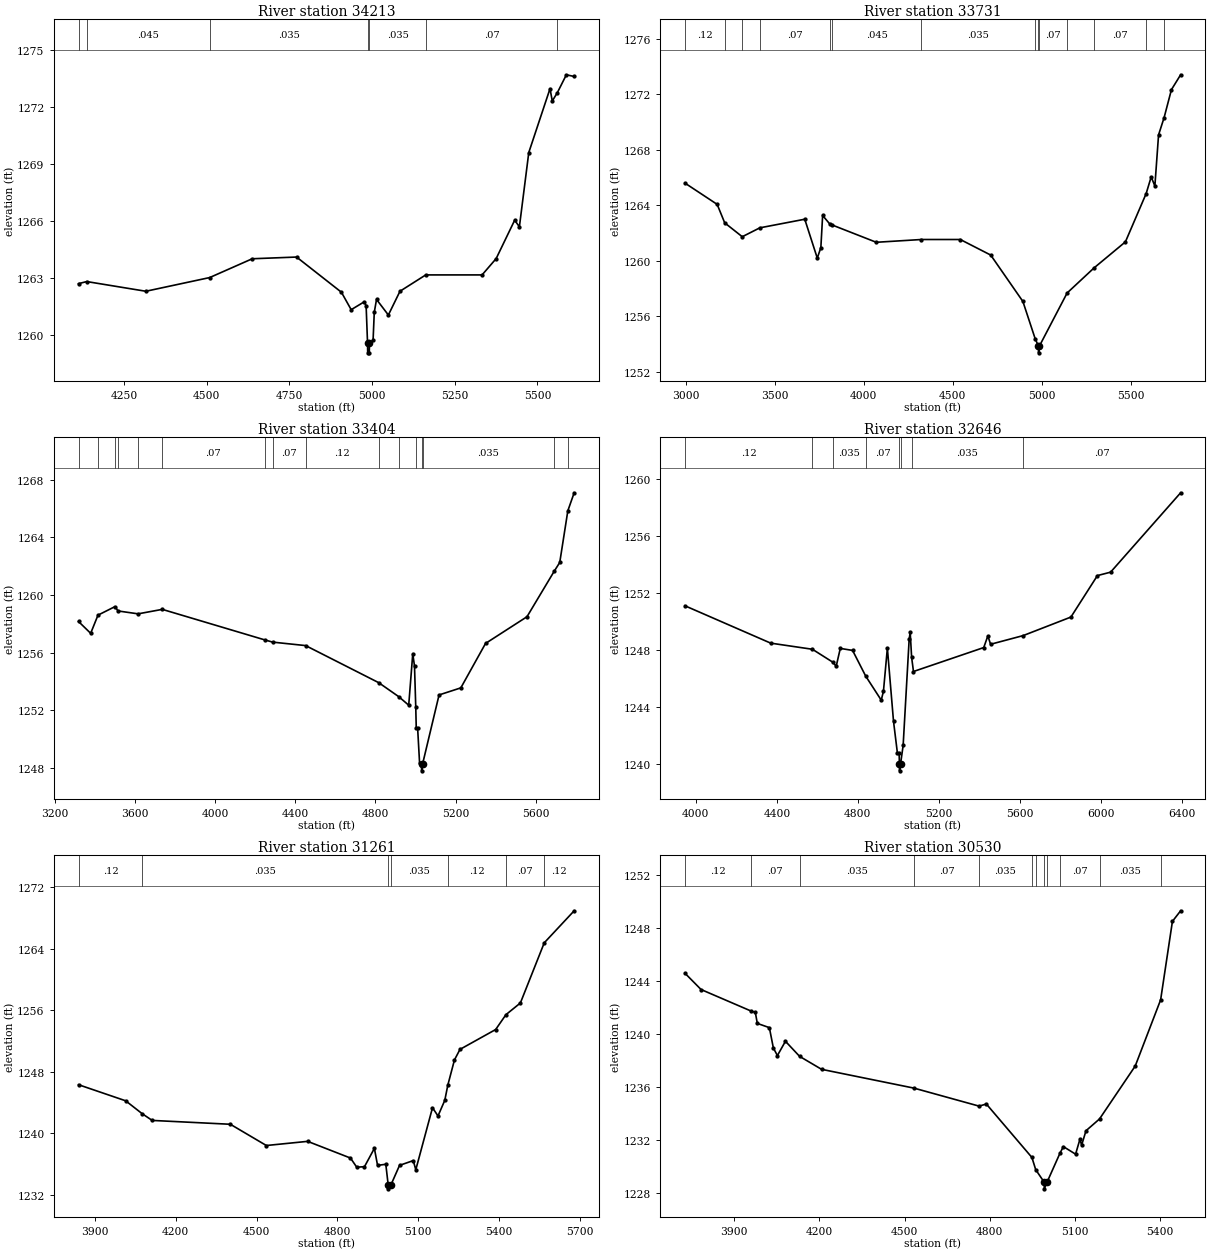
Type RM Length L Ch R = 1 ,34213   ,482,482,482
BEGIN DESCRIPTION:
Spring Branch 65.2
END DESCRIPTION:
XS GIS Cut Line= 3
      2145361.61     13889874.86      2144504.62     13890105.16
       2144050.8     13890514.28
#Sta/Elev= 30
  4112.6 1262.71  4137.5 1262.82  4316.2 1262.31    4509 1263.03  4637.8 1264.02
  4771.8 1264.11  4907.3 1262.26  4936.9 1261.34  4976.9 1261.76  4982.1 1261.53
  4986.4 1259.57  4986.8 1259.07  4991.6 1259.07  4992.1 1259.57  5003.1 1259.73
  5006.7  1261.2  5013.5 1261.88  5049.3 1261.06  5084.4 1262.31  5162.3 1263.17
  5332.6 1263.17  5375.2 1264.03  5431.2 1266.05  5445.4  1265.7  5473.8 1269.61
    5538 1272.97  5544.8 1272.32  5560.2 1272.76  5587.4  1273.7    5611 1273.61
#Mann= 7 ,-1 , 0
  4112.6    .035       0  4137.5    .045       0    4509    .035       0
  4986.4    .035       0  4992.1    .035       0  5162.3     .07       0
  5560.2     .12       0
Bank Sta=4986.4,4992.1
XS Rating Curve= 0 ,0
Exp/Cntr=0.3,0.1

Type RM Length L Ch R = 1 ,33731   ,327,327,327
BEGIN DESCRIPTION:
Spring Branch 65.0
END DESCRIPTION:
XS GIS Cut Line= 3
      2146224.97       13889925.        2144225.       13889725.
      2144025.01     13890474.95
#Sta/Elev= 30
  2995.1 1265.59    3176 1264.06  3218.4 1262.73  3317.1 1261.73  3415.8 1262.37
  3668.4 1262.99  3738.8 1260.19  3758.9 1260.95  3768.9 1263.26  3809.4 1262.64
  3823.4 1262.57  4070.4 1261.33  4324.4 1261.53  4542.7 1261.53  4713.6 1260.41
  4894.5 1257.07  4964.7 1254.34  4982.1 1253.87  4982.5 1253.37  4987.8 1253.87
  5143.2 1257.68    5295 1259.49  5470.8 1261.36  5587.5 1264.84  5615.7 1266.04
  5636.4 1265.38  5657.1 1269.06  5688.4 1270.31  5729.5 1272.32  5781.2 1273.39
#Mann= 14 ,-1 , 0
  2995.1     .12       0  3218.4     .07       0  3317.1    .035       0
  3415.8     .07       0  3809.4    .035       0  3823.4    .045       0
  4324.4    .035       0  4964.7     .07       0  4982.1     .05       0
  4987.8     .07       0  5143.2    .035       0    5295     .07       0
  5587.5    .035       0  5688.4     .12       0
Bank Sta=4982.1,4987.8
XS Rating Curve= 0 ,0
Exp/Cntr=0.3,0.1

Type RM Length L Ch R = 1 ,33404   ,758,758,758
BEGIN DESCRIPTION:
Spring Branch 64.0
END DESCRIPTION:
XS GIS Cut Line= 3
      2145725.05     13889224.99      2144055.46     13889461.01
        2143875.       13890225.
#Sta/Elev= 30
  3319.4 1258.16    3380 1257.34  3416.5  1258.6  3501.1 1259.19  3516.5 1258.89
  3616.5 1258.69  3737.1    1259  4246.8 1256.89  4287.3 1256.73  4451.8 1256.49
  4816.1 1253.92    4916 1252.95  4965.7 1252.36  4985.9 1255.93  4994.6 1255.06
  5000.8 1252.24  5003.3 1250.76  5010.2 1250.76    5020 1248.32  5029.5 1248.31
    5030 1247.81  5035.3 1248.31    5117 1253.07  5225.5 1253.56  5348.8 1256.64
  5555.4 1258.49    5691 1261.64  5718.7 1262.25    5759 1265.83  5790.6 1267.08
#Mann= 16 ,-1 , 0
  3319.4    .035       0  3416.5     .07       0  3501.1    .035       0
  3516.5     .07       0  3616.5    .035       0  3737.1     .07       0
  4246.8    .035       0  4287.3     .07       0  4451.8     .12       0
  4816.1    .035       0    4916     .07       0  5000.8    .035       0
  5029.5     .05       0  5035.3    .035       0    5691     .07       0
    5759     .12       0
Bank Sta=5029.5,5035.3
XS Rating Curve= 0 ,0
Exp/Cntr=0.3,0.1

Type RM Length L Ch R = 1 ,32646   ,1385,1385,1385
BEGIN DESCRIPTION:
Spring Branch 63.1
END DESCRIPTION:
XS GIS Cut Line= 3
      2144483.82     13888935.11      2143441.69     13889091.53
      2143159.85     13890457.66
#Sta/Elev= 30
  3946.2 1251.07  4369.7 1248.45  4575.7 1248.02  4675.8 1247.12  4693.3 1246.83
  4713.5 1248.08  4774.2 1247.94  4839.3 1246.13  4915.8 1244.45  4926.6 1245.06
  4946.1  1248.1  4976.4 1242.97  4995.8 1240.72  5004.2 1240.72  5005.6 1239.99
  5006.1 1239.49  5011.4 1239.99    5024 1241.27  5053.7 1248.71  5058.8 1249.22
  5065.9 1247.46    5075 1246.46  5422.2 1248.14  5442.6 1248.96  5455.9 1248.37
  5617.1 1248.98  5852.9 1250.28  5983.8 1253.19  6048.9 1253.43  6394.9    1259
#Mann= 8 ,-1 , 0
  3946.2     .12       0  4575.7     .07       0  4675.8    .035       0
  4839.3     .07       0  5005.6     .05       0  5011.4     .07       0
  5065.9    .035       0  5617.1     .07       0
Bank Sta=5005.6,5011.4
XS Rating Curve= 0 ,0
Exp/Cntr=0.3,0.1

Type RM Length L Ch R = 1 ,31261   ,731,731,731
BEGIN DESCRIPTION:
Spring Branch 63.0
END DESCRIPTION:
XS GIS Cut Line= 3
      2143992.11     13888710.08       2143016.9     13888276.66
      2142259.17     13888126.78
#Sta/Elev= 30
    3839 1246.32    4014 1244.23  4076.2 1242.53  4112.5 1241.68  4402.5 1241.18
  4536.2 1238.42  4689.4 1238.96  4848.4 1236.79  4871.7  1235.6  4900.4 1235.67
  4937.1 1238.05  4948.9 1235.84  4979.5 1235.98  4988.4 1233.29  4988.9 1232.79
  4998.4 1233.29  5030.5 1235.84  5081.4 1236.46  5090.8 1235.27  5152.8 1243.33
  5173.2 1242.26  5198.4 1244.29  5209.7 1246.27  5234.3 1249.54  5254.8 1250.91
  5387.2 1253.49  5425.4 1255.42    5479 1256.94  5567.6 1264.76  5678.6 1268.92
#Mann= 7 ,-1 , 0
    3839     .12       0  4076.2    .035       0  4988.4    .035       0
  4998.4    .035       0  5209.7     .12       0  5425.4     .07       0
  5567.6     .12       0
Bank Sta=4988.4,4998.4
XS Rating Curve= 0 ,0
Exp/Cntr=0.3,0.1

Type RM Length L Ch R = 1 ,30530   ,467,467,467
BEGIN DESCRIPTION:
Spring Branch 62.0
END DESCRIPTION:
XS GIS Cut Line= 3
        2143975.       13888475.        2143075.       13887575.
        2142675.       13887825.
#Sta/Elev= 30
  3727.2 1244.57  3783.8 1243.34  3959.2 1241.72  3974.7 1241.62  3981.8 1240.78
  4024.2 1240.46  4038.3 1238.92  4052.5 1238.35  4080.8 1239.43  4130.6 1238.29
    4208 1237.31  4533.2 1235.89  4762.3 1234.53  4787.9 1234.69  4948.3 1230.65
  4961.6 1229.73  4991.5 1228.78    4992 1228.28  5001.5 1228.78  5047.4 1230.99
    5059 1231.47    5102  1230.9  5117.3 1232.03  5123.2 1231.58  5138.6 1232.67
  5186.2 1233.56  5311.9 1237.56  5401.3 1242.56  5442.8 1248.49  5471.7 1249.29
#Mann= 12 ,-1 , 0
  3727.2     .12       0  3959.2     .07       0  4130.6    .035       0
  4533.2     .07       0  4762.3    .035       0  4948.3     .07       0
  4961.6    .035       0  4991.5    .035       0  5001.5    .035       0
  5047.4     .07       0  5186.2    .035       0  5401.3     .12       0
Bank Sta=4991.5,5001.5
XS Rating Curve= 0 ,0
Exp/Cntr=0.3,0.1