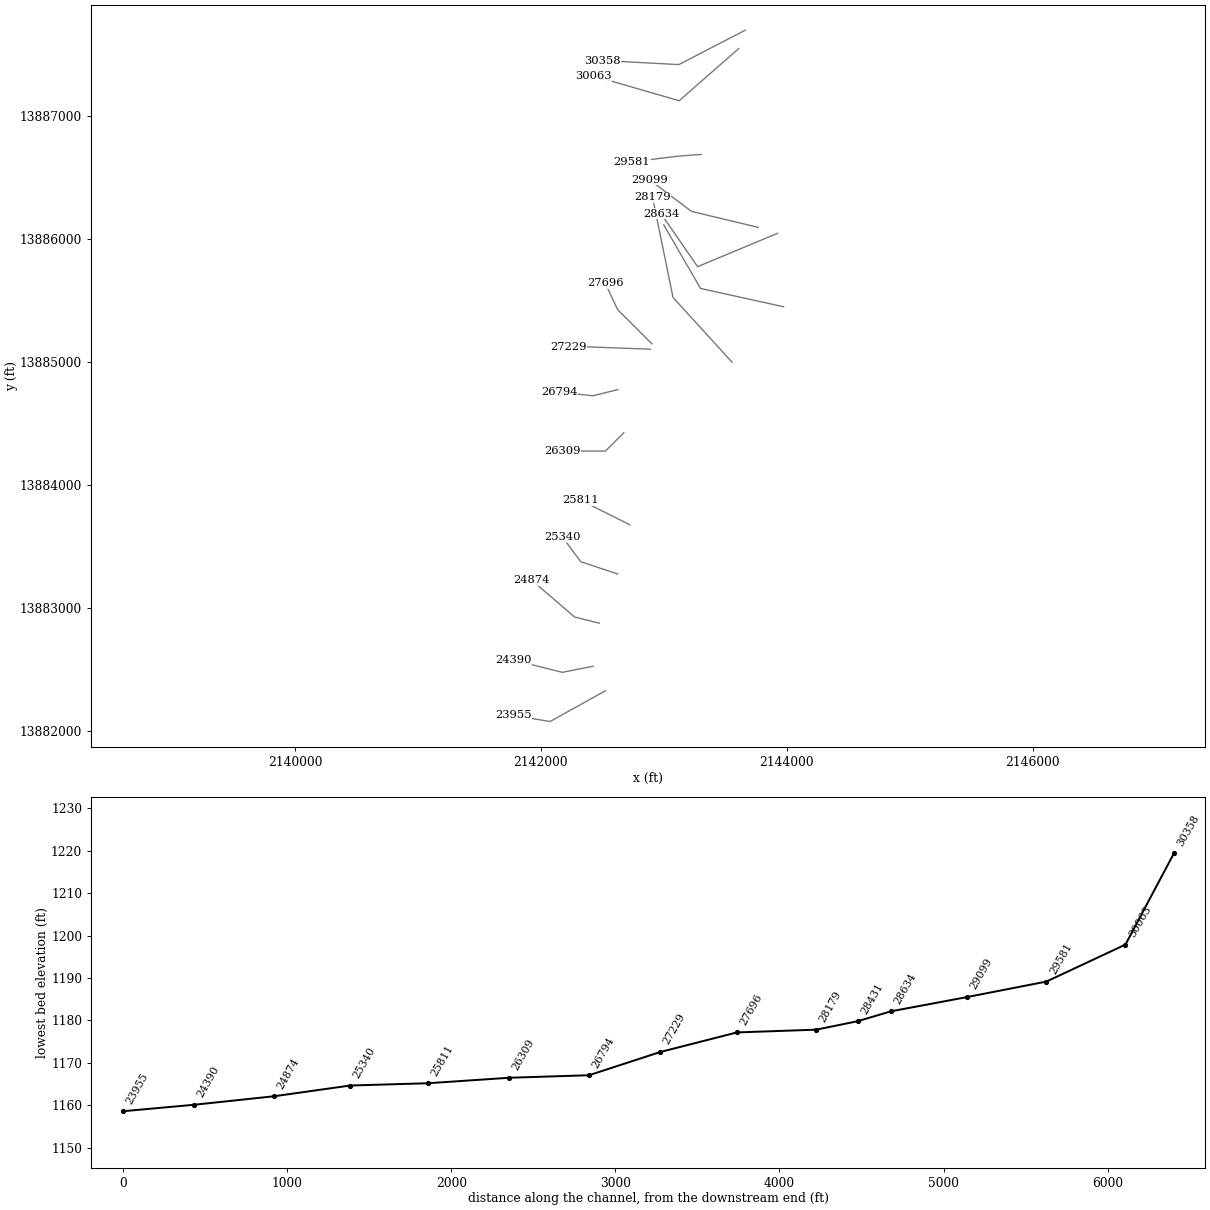
HEC-RAS study Spring Branch.prj: Spring Branch Base Level Engineering

--- Spring Branch.g01 (geometry) --- (continued)

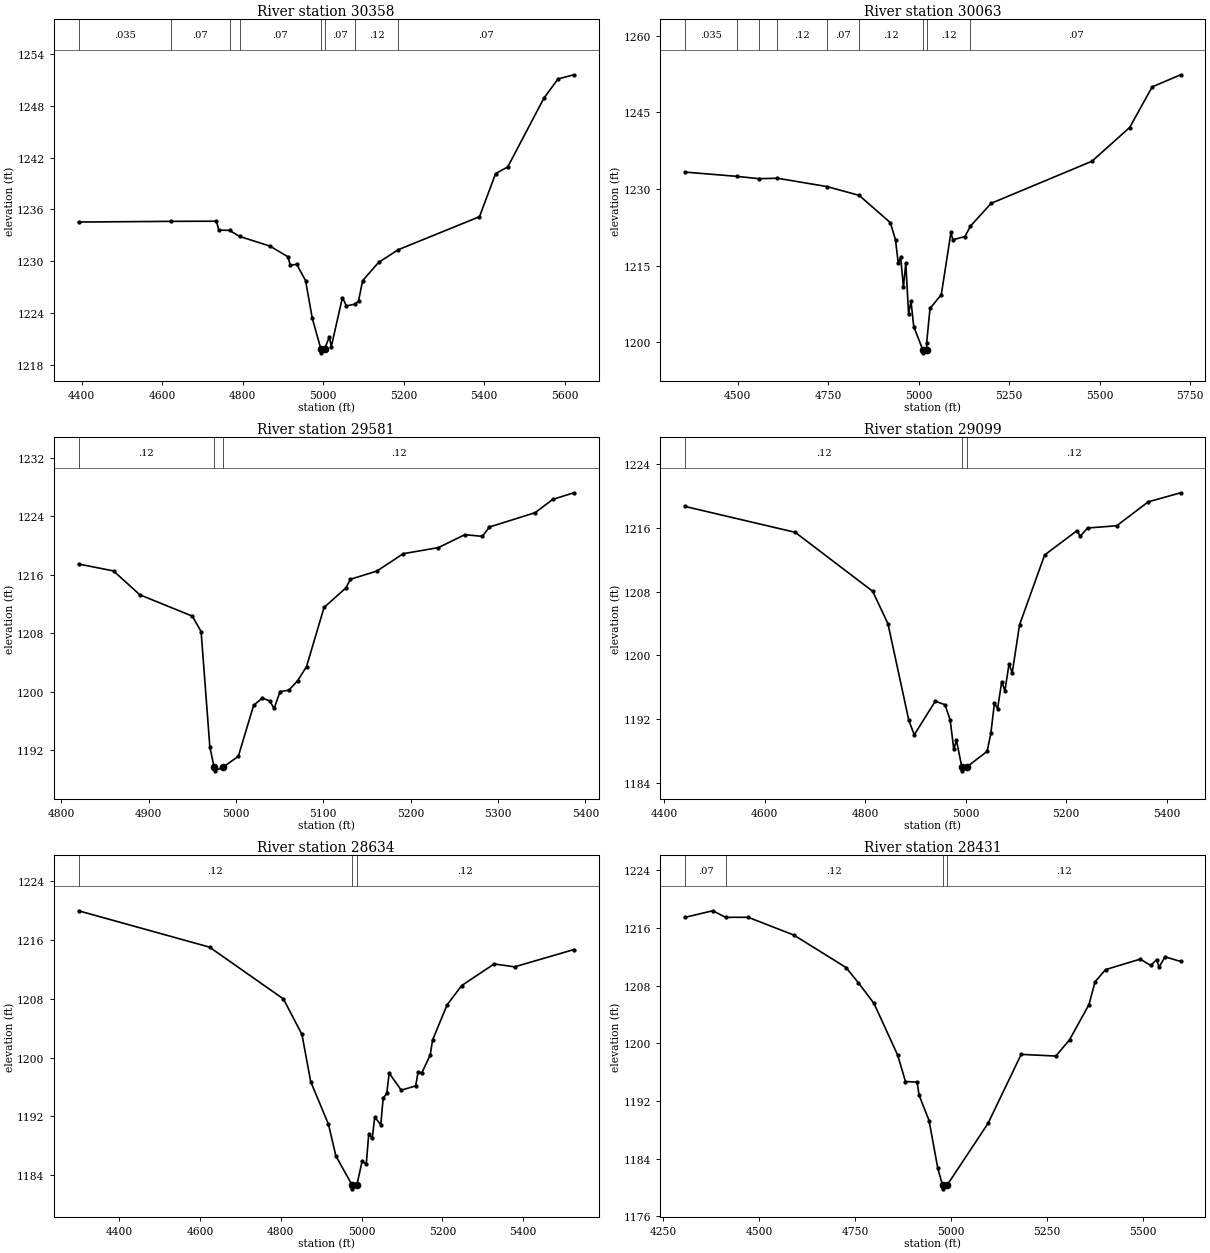
Type RM Length L Ch R = 1 ,30358   ,295,295,295
BEGIN DESCRIPTION:
Spring Branch 61.5
END DESCRIPTION:
XS GIS Cut Line= 3
      2143662.21     13887698.84      2143122.74     13887419.06
      2142500.81      13887452.1
#Sta/Elev= 30
  4392.3 1234.53  4622.7 1234.61    4735 1234.63  4740.7  1233.6  4767.5 1233.56
  4792.5 1232.86  4867.8 1231.74    4912 1230.52  4918.6  1229.5  4934.1 1229.64
  4956.3 1227.74  4972.8  1223.4    4994 1219.86  4994.5 1219.36    5004 1219.86
  5015.2 1221.21  5020.2 1220.08  5047.8 1225.77  5057.8  1224.8  5079.3 1225.01
  5087.9 1225.38  5097.9 1227.73  5137.9 1229.86    5187 1231.33  5388.3 1235.15
  5428.3 1240.15  5458.4 1240.92  5548.5 1248.92  5583.4 1251.13  5622.8 1251.61
#Mann= 8 ,-1 , 0
  4392.3    .035       0  4622.7     .07       0  4767.5    .035       0
  4792.5     .07       0    4994     .05       0    5004     .07       0
  5079.3     .12       0    5187     .07       0
Bank Sta=4994,5004
XS Rating Curve= 0 ,0
Exp/Cntr=0.3,0.1

Type RM Length L Ch R = 1 ,30063   ,482,482,482
BEGIN DESCRIPTION:
Spring Branch 61.0
END DESCRIPTION:
XS GIS Cut Line= 3
      2143610.46     13887550.16        2143125.       13887125.
      2142429.53     13887326.55
#Sta/Elev= 30
  4354.8 1233.31  4497.2 1232.48  4558.1 1232.02  4609.6 1232.11  4746.2 1230.48
  4835.3 1228.76  4921.8  1223.4  4936.1    1220  4943.6 1215.45  4950.3 1216.64
  4957.9 1210.73  4964.5 1215.53  4972.1 1205.51  4978.8 1208.02  4986.4 1203.04
  5011.9 1198.38  5012.4 1197.88    5022 1198.38  5022.1 1199.81  5031.4 1206.58
  5062.6 1209.29  5089.3 1221.49  5094.5 1220.04  5128.1 1220.68  5142.9  1222.7
  5200.4 1227.19    5479 1235.44  5583.2 1242.05  5645.6 1250.02  5724.2 1252.39
#Mann= 9 ,-1 , 0
  4354.8    .035       0  4497.2     .07       0  4558.1    .035       0
  4609.6     .12       0  4746.2     .07       0  4835.3     .12       0
  5011.9     .05       0    5022     .12       0  5142.9     .07       0
Bank Sta=5011.9,5022
XS Rating Curve= 0 ,0
Exp/Cntr=0.3,0.1

Type RM Length L Ch R = 1 ,29581   ,482,482,482
BEGIN DESCRIPTION:
Spring Branch 60.0
END DESCRIPTION:
XS GIS Cut Line= 3
      2143304.98     13886688.34        2143125.       13886675.
      2142740.95     13886628.75
#Sta/Elev= 30
  4819.6 1217.45  4859.7  1216.5  4889.8 1213.24  4949.9 1210.32    4960 1208.21
    4970 1192.44  4974.9 1189.66  4975.4 1189.16  4985.1 1189.66  5002.6 1191.14
  5020.2 1198.14  5030.3 1199.12  5038.6 1198.71  5043.6 1197.69  5050.4    1200
  5060.5 1200.19  5070.6 1201.49  5080.7 1203.42  5100.8  1211.5  5125.8 1214.18
    5131 1215.36  5161.2 1216.48  5191.5 1218.86  5231.7 1219.69    5262 1221.46
  5282.1 1221.23    5290  1222.5  5342.5 1224.47  5362.7 1226.29  5386.9 1227.19
#Mann= 3 ,-1 , 0
  4819.6     .12       0  4974.9     .05       0  4985.1     .12       0
Bank Sta=4974.9,4985.1
XS Rating Curve= 0 ,0
Exp/Cntr=0.3,0.1

Type RM Length L Ch R = 1 ,29099   ,465,465,465
BEGIN DESCRIPTION:
Spring Branch 59.0
END DESCRIPTION:
XS GIS Cut Line= 3
       2143767.8     13886094.79        2143225.       13886225.
      2142883.32     13886482.59
#Sta/Elev= 30
  4441.8 1218.69  4660.6 1215.45  4814.9 1208.05  4845.3 1203.98  4886.9 1191.84
  4897.6 1190.04  4939.6 1194.26  4958.9 1193.81  4969.1  1191.9  4976.4 1188.21
  4981.6 1189.37  4992.3 1186.02  4992.8 1185.52  5002.5 1186.02  5042.7 1187.96
  5050.1 1190.21  5057.2    1194  5063.5 1193.34  5071.8  1196.7  5078.1 1195.56
  5086.4 1198.96  5092.6 1197.78  5107.2 1203.83  5157.2 1212.61  5221.7 1215.66
    5228 1214.94  5242.5 1215.99  5300.6 1216.27  5363.3 1219.27  5427.9 1220.41
#Mann= 3 ,-1 , 0
  4441.8     .12       0  4992.3     .05       0  5002.5     .12       0
Bank Sta=4992.3,5002.5
XS Rating Curve= 0 ,0
Exp/Cntr=0.3,0.1

Type RM Length L Ch R = 1 ,28634   ,203,203,203
BEGIN DESCRIPTION:
Spring Branch 58.0
END DESCRIPTION:
XS GIS Cut Line= 3
      2143925.35     13886046.62        2143275.       13885775.
      2142979.04     13886204.27
#Sta/Elev= 30
  4299.3    1220  4623.6 1215.05  4806.5    1208  4852.4 1203.16    4874 1196.74
    4918 1190.94  4936.4 1186.62  4976.6 1182.65  4977.1 1182.15  4988.2 1182.65
  5001.4 1185.94  5011.5 1185.47  5017.6 1189.58  5026.4 1189.03  5032.5 1191.92
  5047.4 1190.87  5053.4 1194.47  5062.3 1195.16  5068.3  1197.9  5098.1 1195.58
  5133.9 1196.17    5140 1198.11  5148.8 1197.91  5169.8 1200.36  5175.8 1202.43
  5211.7 1207.19  5247.5 1209.81    5328 1212.76  5378.7 1212.37  5525.5 1214.72
#Mann= 3 ,-1 , 0
  4299.3     .12       0  4976.6     .05       0  4988.2     .12       0
Bank Sta=4976.6,4988.2
XS Rating Curve= 0 ,0
Exp/Cntr=0.3,0.1

Type RM Length L Ch R = 1 ,28431   ,252,252,252
BEGIN DESCRIPTION:
Spring Branch 57.5
END DESCRIPTION:
XS GIS Cut Line= 3
      2143974.92     13885448.92      2143298.88     13885598.06
      2142999.74     13886115.29
#Sta/Elev= 30
  4307.7 1217.47  4379.3 1218.37    4413 1217.46  4471.5 1217.47  4590.2 1215.01
  4726.4  1210.5  4758.2 1208.41  4799.2 1205.52  4860.6 1198.38  4881.1  1194.7
  4911.4 1194.62  4916.5 1192.81  4942.5 1189.28  4965.3 1182.65  4977.6 1180.32
  4978.1 1179.82  4989.3 1180.32  5096.1  1188.9  5182.3 1198.46  5272.7 1198.23
  5308.4  1200.5  5358.8 1205.36  5374.6 1208.52  5401.9 1210.21  5492.3 1211.67
  5519.6 1210.79  5535.3 1211.61  5541.1 1210.55  5556.9 1211.99  5597.5 1211.34
#Mann= 4 ,-1 , 0
  4307.7     .07       0    4413     .12       0  4977.6     .05       0
  4989.3     .12       0
Bank Sta=4977.6,4989.3
XS Rating Curve= 0 ,0
Exp/Cntr=0.3,0.1

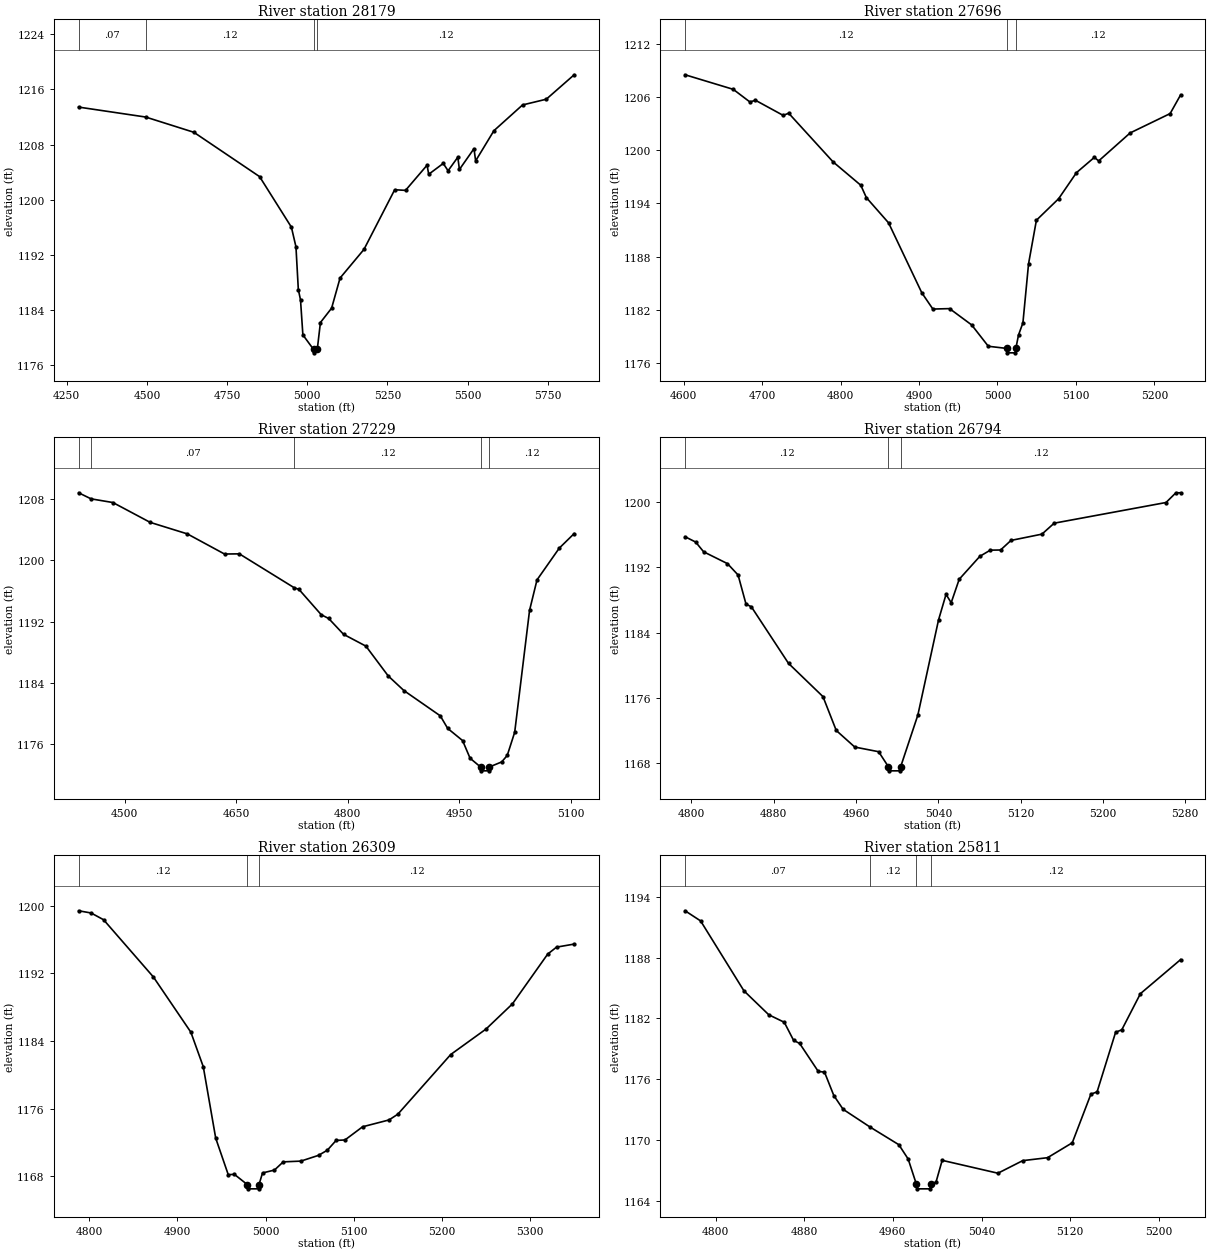
Type RM Length L Ch R = 1 ,28179   ,483,483,483
BEGIN DESCRIPTION:
Spring Branch 57.0
END DESCRIPTION:
XS GIS Cut Line= 3
      2143555.37      13884997.9        2143075.       13885525.
      2142908.26     13886340.27
#Sta/Elev= 30
  4286.9 1213.42  4495.9 1211.98  4646.3 1209.77  4851.2 1203.35  4950.4 1196.03
  4964.6 1193.19    4972 1186.99  4978.8 1185.51  4986.2 1180.43  5019.4 1178.33
  5019.9 1177.83  5031.1 1178.33  5040.9 1182.22  5075.8  1184.3  5102.1 1188.66
  5176.7 1192.81  5272.5 1201.45  5306.3 1201.36  5373.5 1205.01  5378.6 1203.69
  5423.9 1205.26    5439  1204.2  5469.3 1206.16  5474.4 1204.39  5519.8  1207.4
  5524.9 1205.63  5581.9    1210  5671.2 1213.73  5745.2 1214.56  5832.2  1218.1
#Mann= 4 ,-1 , 0
  4286.9     .07       0  4495.9     .12       0  5019.4     .05       0
  5031.1     .12       0
Bank Sta=5019.4,5031.1
XS Rating Curve= 0 ,0
Exp/Cntr=0.3,0.1

Type RM Length L Ch R = 1 ,27696   ,467,467,467
BEGIN DESCRIPTION:
Spring Branch 56.0
END DESCRIPTION:
XS GIS Cut Line= 3
      2142903.87     13885147.07        2142625.       13885425.
       2142523.5     13885640.36
#Sta/Elev= 30
  4601.7 1208.49  4663.1 1206.85  4684.3 1205.43  4691.4 1205.62  4726.7 1203.92
  4733.8 1204.16  4790.4 1198.68  4825.7 1196.05  4832.8 1194.66  4861.1 1191.82
  4903.5 1183.94  4917.6 1182.11  4938.9 1182.16  4967.1 1180.32  4988.3 1177.92
  5011.6 1177.68  5012.1 1177.18  5022.9 1177.18  5023.4 1177.68  5026.8 1179.19
  5032.4 1180.55  5039.6 1187.21  5049.6 1192.11  5077.9 1194.53  5100.7 1197.47
  5123.5 1199.19    5129 1198.79  5169.1 1201.94  5220.1 1204.12  5233.5 1206.23
#Mann= 3 ,-1 , 0
  4601.7     .12       0  5011.6     .05       0  5023.4     .12       0
Bank Sta=5011.6,5023.4
XS Rating Curve= 0 ,0
Exp/Cntr=0.3,0.1

Type RM Length L Ch R = 1 ,27229   ,435,435,435
BEGIN DESCRIPTION:
Spring Branch 55.0
END DESCRIPTION:
XS GIS Cut Line= 3
      2142891.08     13885103.67        2142325.       13885125.
      2142224.98       13885125.
#Sta/Elev= 30
    4438 1208.76  4454.7 1207.97  4484.1 1207.49  4534.2 1204.91  4584.2 1203.41
  4634.2 1200.79  4654.2 1200.81  4728.3 1196.38  4734.3 1196.19  4764.3 1192.89
  4774.3  1192.4  4794.3 1190.34  4824.4  1188.8  4854.4 1184.92  4875.6 1183.01
  4924.4 1179.73  4934.4 1178.09  4954.4 1176.51  4964.5 1174.21  4978.6 1173.07
  4979.1 1172.57  4989.9 1172.57  4990.4 1173.07    5007 1173.73  5014.5 1174.58
  5024.5 1177.59  5044.5 1193.46  5054.5 1197.42  5084.5 1201.56  5104.5 1203.45
#Mann= 5 ,-1 , 0
    4438     .12       0  4454.7     .07       0  4728.3     .12       0
  4978.6     .05       0  4990.4     .12       0
Bank Sta=4978.6,4990.4
XS Rating Curve= 0 ,0
Exp/Cntr=0.3,0.1

Type RM Length L Ch R = 1 ,26794   ,485,485,485
BEGIN DESCRIPTION:
Spring Branch 54.0
END DESCRIPTION:
XS GIS Cut Line= 3
      2142624.97     13884774.99        2142425.       13884725.
      2142150.92     13884752.68
#Sta/Elev= 30
  4793.9 1195.73  4804.2 1195.08  4811.9 1193.89  4835.1 1192.44  4845.4 1191.05
  4853.1 1187.49  4858.3 1187.16  4894.4 1180.24  4927.9 1176.17  4940.8 1172.03
  4958.8    1170    4982 1169.43  4991.5 1167.59    4992 1167.09  5002.9 1167.09
  5003.4 1167.59  5020.1 1173.91  5040.2 1185.55  5047.5 1188.68  5052.5 1187.66
  5060.3 1190.53  5080.4 1193.34  5090.5 1194.09  5100.5 1194.11  5110.6 1195.28
  5140.7 1196.05  5152.6 1197.39  5261.3 1199.92  5270.9 1201.11  5275.5 1201.11
#Mann= 3 ,-1 , 0
  4793.9     .12       0  4991.5     .05       0  5003.4     .12       0
Bank Sta=4991.5,5003.4
XS Rating Curve= 0 ,0
Exp/Cntr=0.3,0.1

Type RM Length L Ch R = 1 ,26309   ,498,498,498
BEGIN DESCRIPTION:
Spring Branch 53.0
END DESCRIPTION:
XS GIS Cut Line= 3
      2142674.98     13884424.98        2142525.       13884275.
        2142175.       13884275.
#Sta/Elev= 30
  4787.9 1199.39    4802 1199.13  4816.2 1198.33  4872.7 1191.56  4915.2 1185.03
  4929.3 1180.94  4943.4 1172.49  4957.6 1168.18  4964.6 1168.21  4979.3    1167
  4979.8  1166.5    4992  1166.5  4992.5    1167  4996.5 1168.38    5010 1168.72
    5020 1169.69    5040 1169.78    5060 1170.46    5070 1171.07    5080 1172.23
    5090 1172.28    5110 1173.84    5140 1174.65    5150 1175.33    5210 1182.39
    5250  1185.4    5280 1188.38    5320 1194.27    5330 1195.09    5350 1195.45
#Mann= 3 ,-1 , 0
  4787.9     .12       0  4979.3     .05       0  4992.5     .12       0
Bank Sta=4979.3,4992.5
XS Rating Curve= 0 ,0
Exp/Cntr=0.3,0.1

Type RM Length L Ch R = 1 ,25811   ,471,471,471
BEGIN DESCRIPTION:
Spring Branch 52.0
END DESCRIPTION:
XS GIS Cut Line= 3
      2142725.02     13883674.99        2142525.       13883775.
      2142325.03     13883874.98
#Sta/Elev= 30
  4772.5 1192.61  4786.5 1191.61  4825.6 1184.72    4848 1182.36    4862 1181.62
  4870.4 1179.84  4875.9 1179.53  4892.7 1176.77  4898.3 1176.71  4906.7  1174.4
  4915.1 1173.04  4939.3  1171.3  4965.4 1169.55  4973.8 1168.14  4981.1  1165.7
  4981.6  1165.2  4993.8  1165.2  4994.3  1165.7  4998.9 1165.85  5004.5 1168.01
  5054.8 1166.74  5077.2 1167.98  5099.6 1168.27  5121.9 1169.74  5138.7 1174.53
  5144.3 1174.76    5161 1180.63  5166.6 1180.88  5183.4 1184.44  5219.7  1187.8
#Mann= 4 ,-1 , 0
  4772.5     .07       0  4939.3     .12       0  4981.1     .05       0
  4994.3     .12       0
Bank Sta=4981.1,4994.3
XS Rating Curve= 0 ,0
Exp/Cntr=0.3,0.1

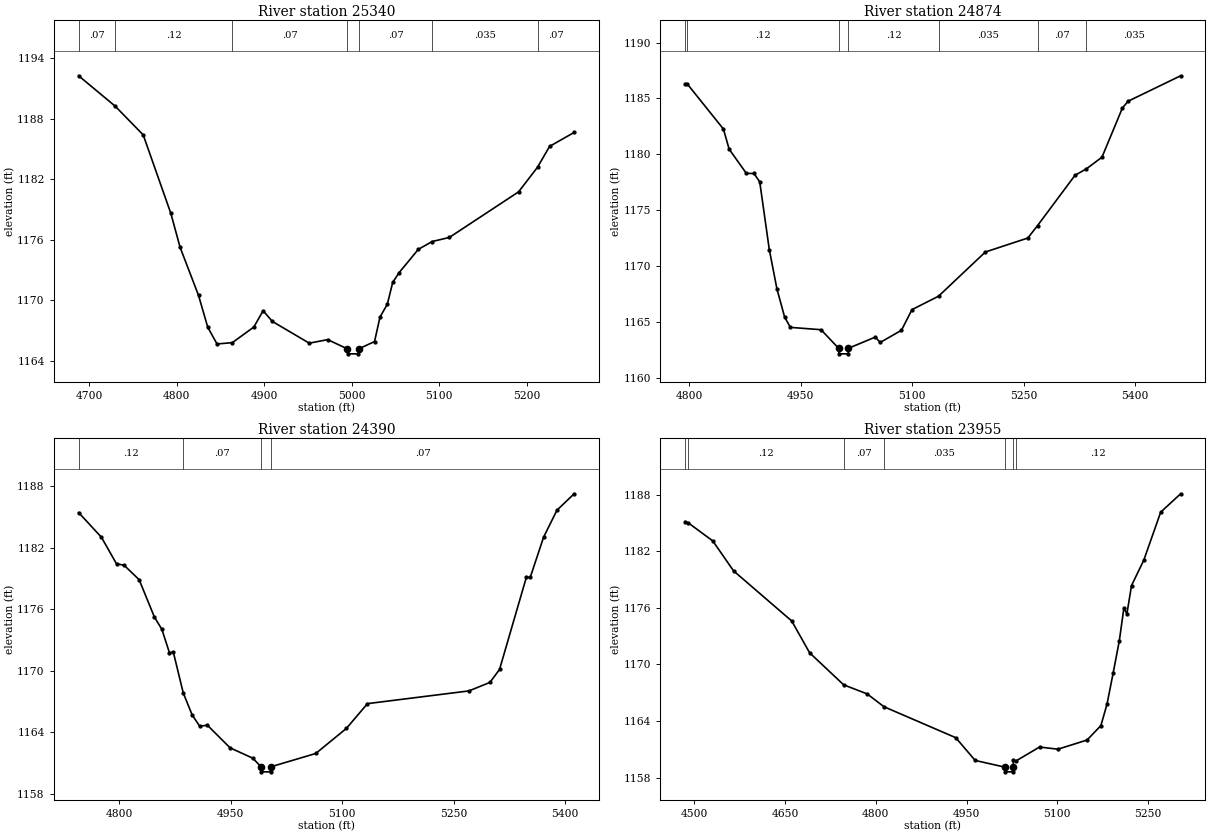
Type RM Length L Ch R = 1 ,25340   ,466,466,466
BEGIN DESCRIPTION:
Spring Branch 51.0
END DESCRIPTION:
XS GIS Cut Line= 3
      2142624.97     13883275.01        2142325.       13883375.
        2142175.       13883575.
#Sta/Elev= 30
  4687.9 1192.27  4729.7 1189.25  4761.7  1186.4  4793.3  1178.6  4803.8 1175.25
  4824.9 1170.47  4835.4 1167.32    4846 1165.65  4863.5 1165.78  4888.1 1167.33
  4898.7 1168.95  4909.2 1167.89  4951.4 1165.73  4972.5 1166.08  4994.8 1165.17
  4995.3 1164.67  5007.6 1164.67  5008.1 1165.17    5026 1165.89  5032.2 1168.31
  5040.6 1169.59  5046.8 1171.77  5054.1 1172.73    5076 1175.04  5091.9 1175.82
  5111.4 1176.22  5190.6 1180.75  5212.2 1183.19    5226 1185.26  5254.1 1186.65
#Mann= 7 ,-1 , 0
  4687.9     .07       0  4729.7     .12       0  4863.5     .07       0
  4994.8     .05       0  5008.1     .07       0  5091.9    .035       0
  5212.2     .07       0
Bank Sta=4994.8,5008.1
XS Rating Curve= 0 ,0
Exp/Cntr=0.3,0.1

Type RM Length L Ch R = 1 ,24874   ,484,484,484
BEGIN DESCRIPTION:
Spring Branch 50.0
END DESCRIPTION:
XS GIS Cut Line= 3
      2142475.04     13882874.99        2142275.       13882925.
      2141924.98     13883225.02
#Sta/Elev= 30
  4794.2 1186.32    4797 1186.31  4845.8 1182.26  4853.5 1180.46  4876.7 1178.29
    4887 1178.28  4894.7 1177.53  4907.6 1171.45  4917.9 1167.93  4928.2 1165.42
    4936  1164.5  4977.2 1164.29  5000.9 1162.63  5001.4 1162.13  5013.7 1162.13
  5014.2 1162.63  5050.3 1163.63  5056.9 1163.15  5085.5 1164.24  5099.7 1166.09
  5135.4 1167.29  5198.5 1171.25  5255.6  1172.5  5268.7 1173.61  5319.2 1178.12
  5334.6  1178.7  5355.5 1179.74  5382.9 1184.13  5390.6 1184.75  5461.4 1187.03
#Mann= 7 ,-1 , 0
  4794.2     .07       0    4797     .12       0  5000.9     .05       0
  5014.2     .12       0  5135.4    .035       0  5268.7     .07       0
  5334.6    .035       0
Bank Sta=5000.9,5014.2
XS Rating Curve= 0 ,0
Exp/Cntr=0.3,0.1

Type RM Length L Ch R = 1 ,24390   ,435,435,435
BEGIN DESCRIPTION:
Spring Branch 49.0
END DESCRIPTION:
XS GIS Cut Line= 3
      2142424.96     13882524.99        2142175.       13882475.
      2141775.02     13882574.99
#Sta/Elev= 30
  4745.1 1185.42  4775.7 1183.02  4796.1 1180.42  4806.2 1180.29  4826.6 1178.87
    4847 1175.25  4857.2 1174.03  4867.4 1171.74  4872.5 1171.84    4886 1167.82
    4898 1165.68  4908.2 1164.58  4918.4 1164.69    4949 1162.48  4979.6 1161.47
  4990.6 1160.64  4991.1 1160.14  5003.8 1160.14  5004.3 1160.64  5064.4 1161.93
  5105.7 1164.38    5134 1166.79  5270.6 1168.03  5298.9 1168.86  5311.8 1170.12
  5347.9  1179.1  5353.1 1179.09  5371.1 1183.01  5389.1 1185.65  5412.3 1187.25
#Mann= 4 ,-1 , 0
  4745.1     .12       0    4886     .07       0  4990.6     .05       0
  5004.3     .07       0
Bank Sta=4990.6,5004.3
XS Rating Curve= 0 ,0
Exp/Cntr=0.3,0.1

Type RM Length L Ch R = 1 ,23955   ,300,300,300
BEGIN DESCRIPTION:
Spring Branch 48.0
END DESCRIPTION:
XS GIS Cut Line= 3
      2142525.03     13882325.02        2142075.       13882075.
      2141774.95     13882125.01
#Sta/Elev= 30
  4484.8 1185.13  4490.4 1184.98  4530.6 1183.08  4564.9 1179.91    4661  1174.6
  4690.7 1171.22  4746.9 1167.83  4785.7 1166.87  4813.5 1165.51  4932.1 1162.23
  4964.2 1159.82    5013 1159.11  5013.5 1158.61  5026.3 1158.61  5026.8 1159.11
  5027.5 1159.83  5031.8 1159.77  5070.6 1161.24    5101 1161.01  5149.1 1161.98
    5172 1163.51  5182.1 1165.78  5192.2 1169.06  5202.4 1172.48    5210 1175.97
    5215 1175.36  5222.6 1178.35  5242.9 1181.04  5270.8 1186.13  5303.8 1188.08
#Mann= 7 ,-1 , 0
  4484.8     .07       0  4490.4     .12       0  4746.9     .07       0
  4813.5    .035       0    5013    .035       0  5026.8    .035       0
  5031.8     .12       0
Bank Sta=5013,5026.8
XS Rating Curve= 0 ,0
Exp/Cntr=0.3,0.1