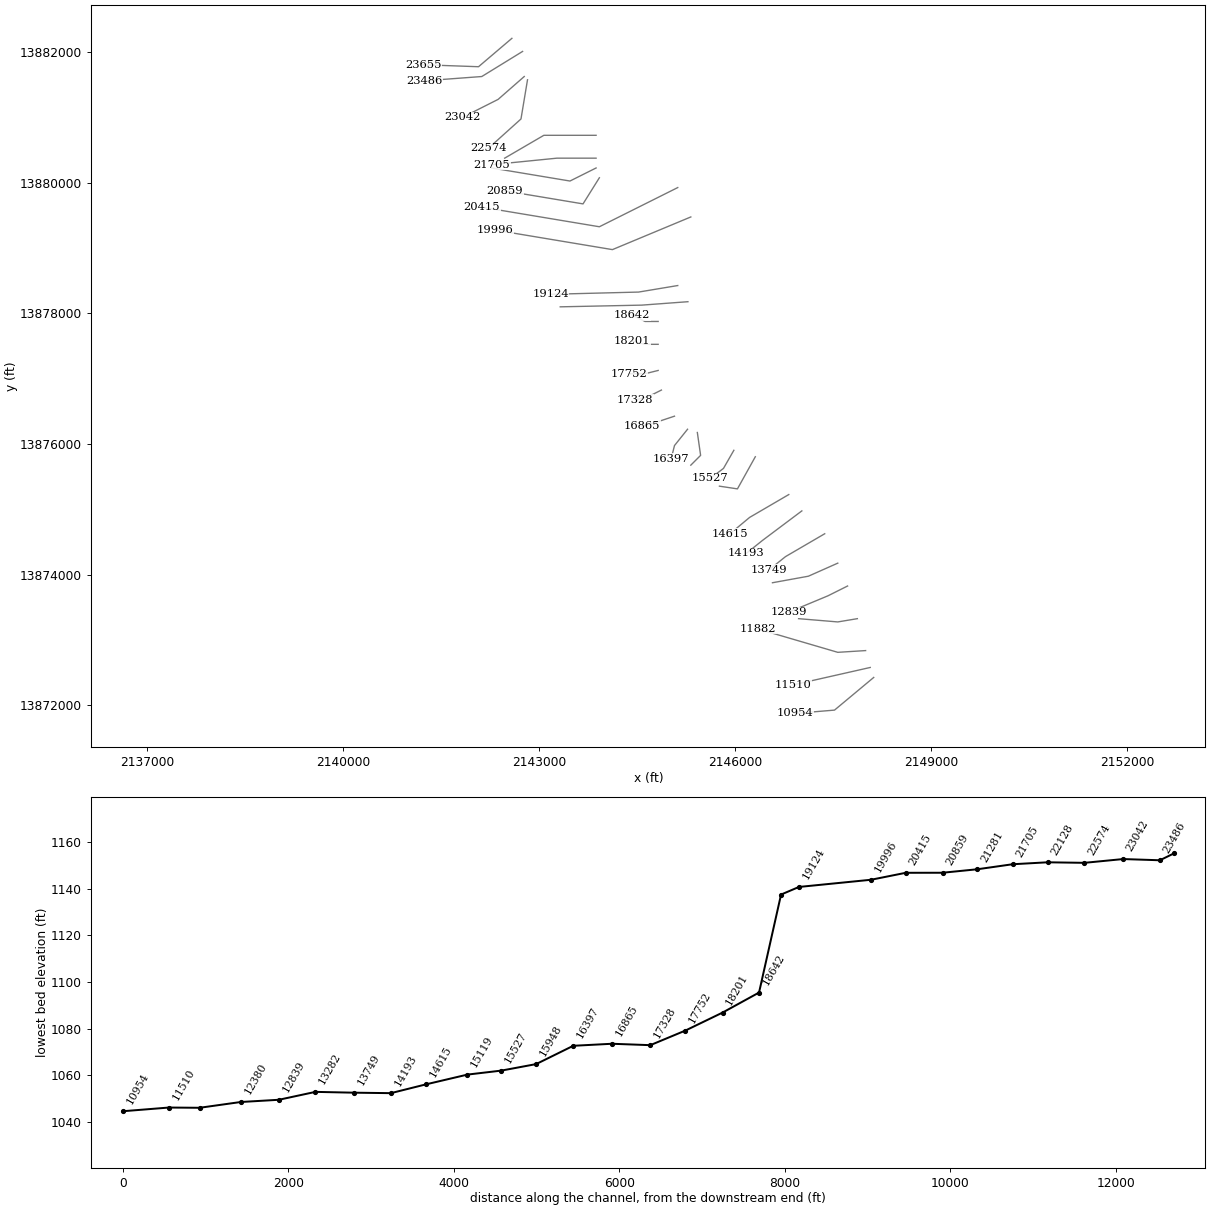
HEC-RAS study Spring Branch.prj: Spring Branch Base Level Engineering

--- Spring Branch.g01 (geometry) --- (continued)

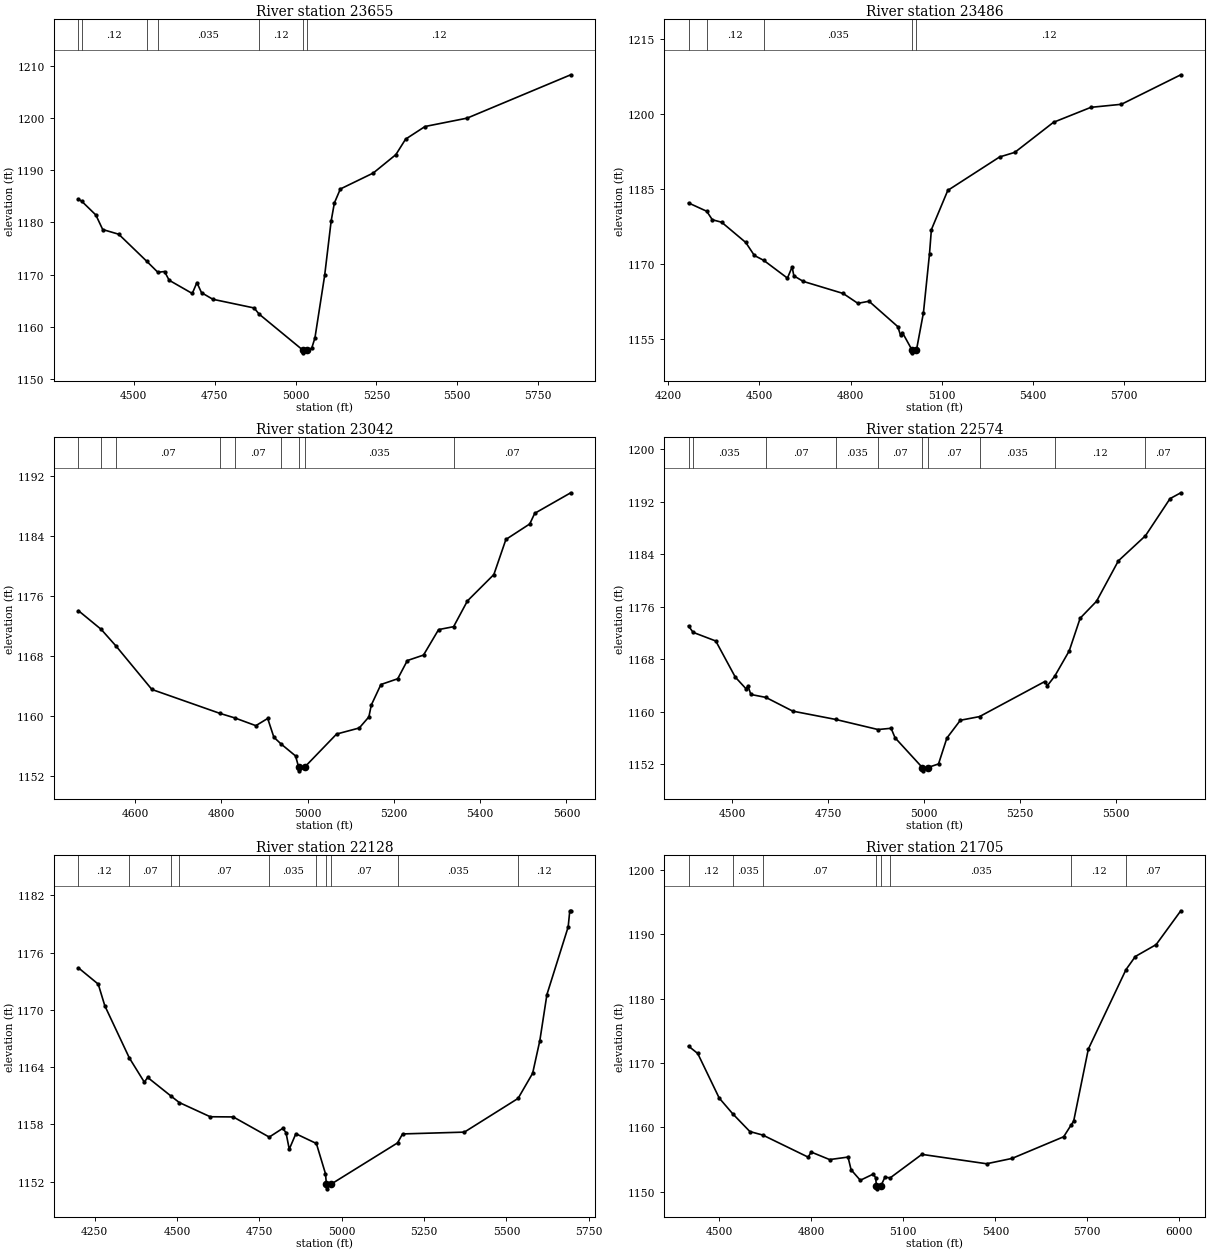
Type RM Length L Ch R = 1 ,23655   ,169,169,169
BEGIN DESCRIPTION:
Spring Branch 47.5
END DESCRIPTION:
XS GIS Cut Line= 3
      2142585.87     13882209.59      2142074.92     13881774.97
      2141224.95     13881805.09
#Sta/Elev= 30
  4329.2 1184.43  4339.6 1184.04  4382.9 1181.43  4404.1 1178.65  4453.6 1177.75
  4540.5 1172.56  4574.6 1170.47  4595.2 1170.62  4609.5 1168.95  4680.9 1166.42
  4695.2  1168.5  4709.5 1166.57  4744.6 1165.31    4872 1163.65  4887.4 1162.48
    5023 1155.57  5023.5 1155.07  5036.8 1155.57    5050 1155.95    5060 1157.93
    5090 1169.86    5110 1180.24    5120 1183.72  5138.5  1186.4  5240.1 1189.45
  5310.1 1192.97  5340.1 1195.93  5400.2 1198.35  5530.3 1199.95  5850.5 1208.24
#Mann= 7 ,-1 , 0
  4329.2     .07       0  4339.6     .12       0  4540.5     .07       0
  4574.6    .035       0  4887.4     .12       0    5023     .05       0
  5036.8     .12       0
Bank Sta=5023,5036.8
XS Rating Curve= 0 ,0
Exp/Cntr=0.3,0.1

Type RM Length L Ch R = 1 ,23486   ,444,444,444
BEGIN DESCRIPTION:
Spring Branch 47.0
END DESCRIPTION:
XS GIS Cut Line= 3
      2142749.68     13882009.18        2142125.       13881625.
      2141239.92     13881558.98
#Sta/Elev= 30
  4266.6  1182.2  4326.5 1180.53  4344.9 1178.83  4375.7 1178.33    4455 1174.27
  4483.4 1171.66  4514.3 1170.68  4592.2 1167.12  4607.7 1169.35  4613.5 1167.57
  4644.4 1166.46  4775.7 1164.04  4824.2 1162.06  4860.9 1162.48  4955.6 1157.39
  4964.7 1155.64    4971 1156.18  5003.1 1152.63  5003.6 1152.13  5016.9 1152.63
  5040.1 1160.18  5060.1 1172.03  5066.2 1176.84  5120.3 1184.72  5290.8 1191.42
    5341 1192.35  5468.4 1198.38  5591.6 1201.38  5691.9 1201.99  5887.5 1207.91
#Mann= 5 ,-1 , 0
  4266.6     .07       0  4326.5     .12       0  4514.3    .035       0
  5003.1    .035       0  5016.9     .12       0
Bank Sta=5003.1,5016.9
XS Rating Curve= 0 ,0
Exp/Cntr=0.3,0.1

Type RM Length L Ch R = 1 ,23042   ,468,468,468
BEGIN DESCRIPTION:
Spring Branch 46.0
END DESCRIPTION:
XS GIS Cut Line= 3
      2142774.96     13881624.97        2142375.       13881275.
      2141830.13     13880999.98
#Sta/Elev= 30
  4468.3 1174.02    4521 1171.53  4555.5  1169.3  4638.6 1163.51  4796.3 1160.32
  4830.5 1159.72  4879.7 1158.68  4907.2 1159.64  4921.5 1157.14  4938.1 1156.24
  4971.8 1154.64    4979 1153.15  4979.5 1152.65    4993 1153.15    5067 1157.56
  5119.6 1158.37  5141.9 1159.85  5147.5 1161.43  5169.8 1164.17  5208.8 1164.94
  5231.1 1167.37  5268.6  1168.1  5303.6  1171.5  5338.4 1171.89  5370.5 1175.33
  5431.8 1178.85  5459.7 1183.53    5515  1185.6  5526.6 1187.02  5610.1 1189.76
#Mann= 9 ,-1 , 0
  4468.3     .07       0    4521    .035       0  4555.5     .07       0
  4796.3    .035       0  4830.5     .07       0  4938.1    .035       0
    4979     .05       0    4993    .035       0  5338.4     .07       0
Bank Sta=4979,4993
XS Rating Curve= 0 ,0
Exp/Cntr=0.3,0.1

Type RM Length L Ch R = 1 ,22574   ,446,446,446
BEGIN DESCRIPTION:
Spring Branch 45.0
END DESCRIPTION:
XS GIS Cut Line= 3
        2142825.     13881574.98        2142725.       13880975.
      2142225.02     13880525.02
#Sta/Elev= 30
  4386.8 1173.09  4398.6 1172.12  4457.7  1170.8  4508.4 1165.31  4536.3 1163.53
  4541.4 1163.95    4549 1162.66  4588.1 1162.21    4658 1160.12  4769.4 1158.86
  4879.8 1157.32  4913.9 1157.51  4924.1 1156.07  4995.2 1151.53  4995.7 1151.03
  5009.2 1151.53  5037.3 1152.08    5059 1156.02  5094.1 1158.73    5144 1159.29
  5313.8 1164.63  5320.6 1164.01  5339.5 1165.43  5377.4  1169.3  5405.8 1174.27
  5448.4 1176.85  5505.2    1183  5575.8 1186.83  5639.7 1192.48  5667.7 1193.37
#Mann= 10 ,-1 , 0
  4386.8     .12       0  4398.6    .035       0  4588.1     .07       0
  4769.4    .035       0  4879.8     .07       0  4995.2     .05       0
  5009.2     .07       0    5144    .035       0  5339.5     .12       0
  5575.8     .07       0
Bank Sta=4995.2,5009.2
XS Rating Curve= 0 ,0
Exp/Cntr=0.3,0.1

Type RM Length L Ch R = 1 ,22128   ,423,423,423
BEGIN DESCRIPTION:
Spring Branch 44.0
END DESCRIPTION:
XS GIS Cut Line= 3
      2143875.01       13880725.        2143075.       13880725.
      2142475.03     13880375.02
#Sta/Elev= 30
  4200.6  1174.4  4260.6  1172.7  4280.6 1170.43    4355 1164.97  4400.6 1162.43
  4410.6 1162.93  4481.4 1160.98  4506.6  1160.3  4600.6 1158.81  4670.6 1158.79
  4779.8 1156.68  4820.6 1157.59  4830.6 1157.16  4840.6 1155.41  4860.6 1157.03
  4922.9 1156.01  4950.6 1152.84  4953.3 1151.76  4953.8 1151.26    4968 1151.76
  5169.3 1156.07  5184.6 1157.01  5372.3  1157.2  5535.3 1160.73  5579.5 1163.36
  5601.4 1166.79  5622.9 1171.61  5687.4 1178.69  5692.3 1180.38  5695.2 1180.38
#Mann= 10 ,-1 , 0
  4200.6     .12       0    4355     .07       0  4481.4    .035       0
  4506.6     .07       0  4779.8    .035       0  4922.9     .07       0
  4953.3     .05       0    4968     .07       0  5169.3    .035       0
  5535.3     .12       0
Bank Sta=4953.3,4968
XS Rating Curve= 0 ,0
Exp/Cntr=0.3,0.1

Type RM Length L Ch R = 1 ,21705   ,424,424,424
BEGIN DESCRIPTION:
Spring Branch 43.0
END DESCRIPTION:
XS GIS Cut Line= 3
      2143874.97       13880375.        2143275.       13880375.
      2142274.96       13880275.
#Sta/Elev= 30
  4399.7 1172.61  4429.7 1171.47  4499.7 1164.54  4543.4 1162.11  4599.7 1159.33
  4641.9 1158.78  4789.7 1155.35  4799.7 1156.14  4859.7 1154.97  4919.7 1155.36
  4929.7 1153.39  4959.7 1151.75  5002.2 1152.72  5009.7 1152.15  5012.4 1150.92
  5012.9 1150.42  5027.1 1150.92  5039.9 1152.21  5057.6 1152.14  5160.5 1155.78
  5371.5 1154.32  5454.4 1155.15  5622.8 1158.52    5647 1160.34  5655.4 1160.95
  5703.2 1172.15  5826.1 1184.52  5856.4 1186.55  5924.3  1188.4  6004.7 1193.66
#Mann= 8 ,-1 , 0
  4399.7     .12       0  4543.4    .035       0  4641.9     .07       0
  5012.4     .05       0  5027.1     .07       0  5057.6    .035       0
    5647     .12       0  5826.1     .07       0
Bank Sta=5012.4,5027.1
XS Rating Curve= 0 ,0
Exp/Cntr=0.3,0.1

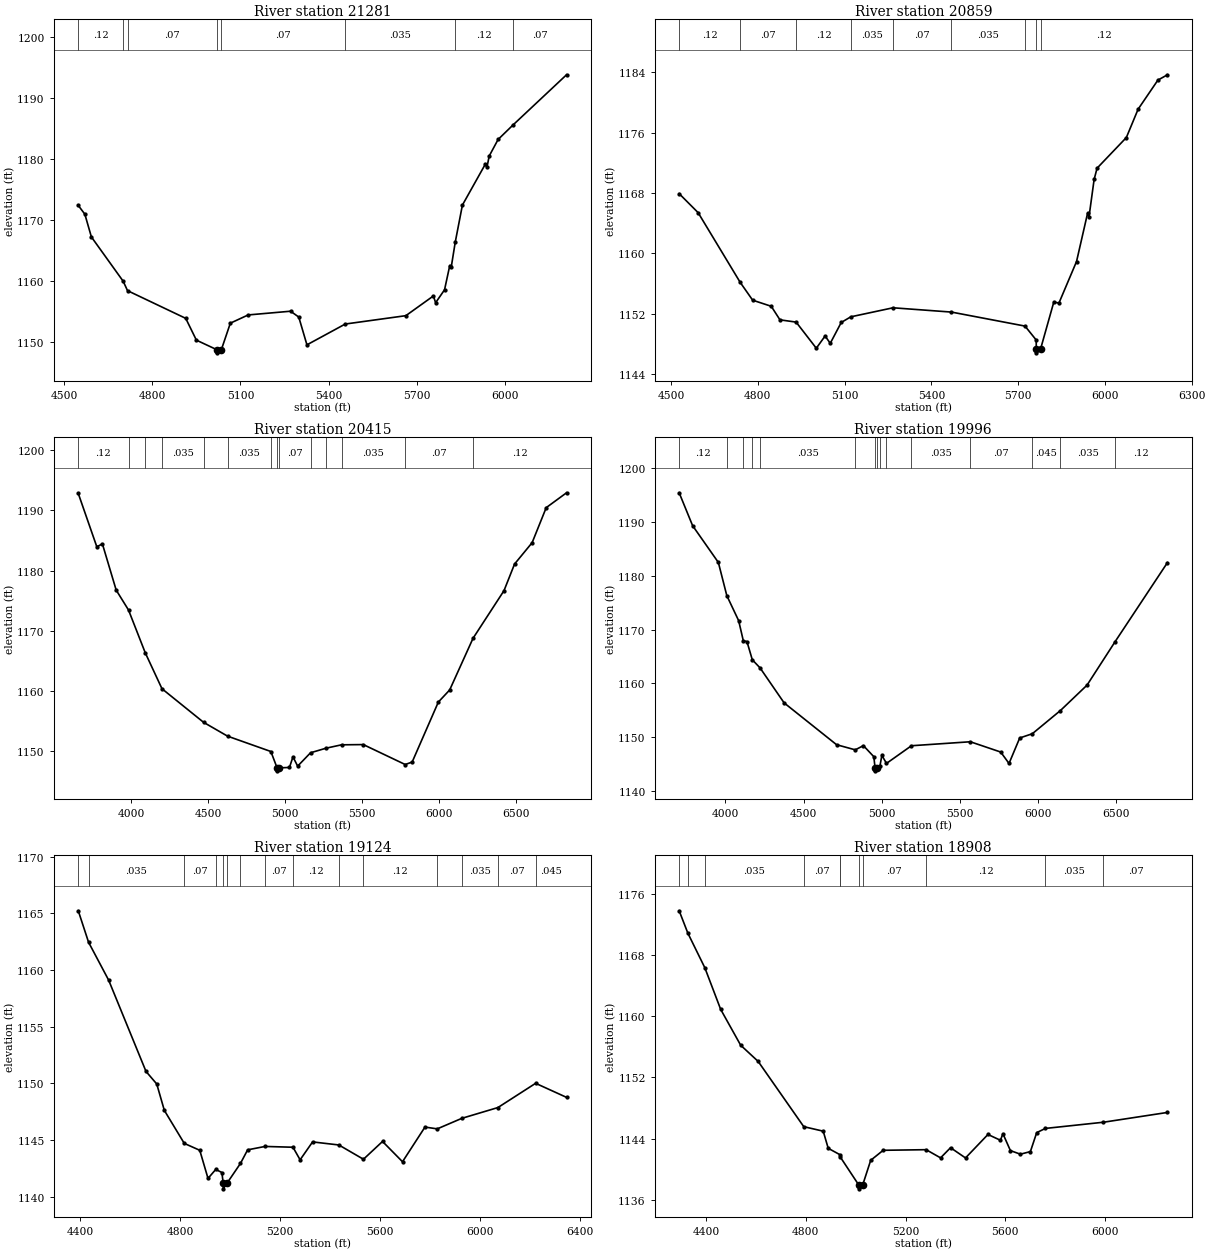
Type RM Length L Ch R = 1 ,21281   ,422,422,422
BEGIN DESCRIPTION:
Spring Branch 42.0
END DESCRIPTION:
XS GIS Cut Line= 3
      2143875.01     13880225.01        2143475.       13880025.
      2142274.98       13880225.
#Sta/Elev= 30
  4547.2 1172.43  4569.6    1171  4591.9 1167.27  4700.4    1160    4715 1158.47
  4913.4 1153.93  4949.7 1150.36    5020 1148.78  5020.5 1148.28  5034.7 1148.78
  5065.4 1153.14  5126.2 1154.49  5270.7  1155.1  5298.6 1154.14  5326.4 1149.59
    5457    1153  5663.5 1154.37  5757.3  1157.6  5764.9 1156.49  5795.3 1158.61
  5813.1 1162.58  5818.1 1162.32  5831.8 1166.42  5856.2 1172.49  5934.7 1179.23
  5939.8 1178.66  5947.4 1180.52  5977.8 1183.24  6027.9 1185.58    6211 1193.84
#Mann= 8 ,-1 , 0
  4547.2     .12       0  4700.4    .035       0    4715     .07       0
    5020     .05       0  5034.7     .07       0    5457    .035       0
  5831.8     .12       0  6027.9     .07       0
Bank Sta=5020,5034.7
XS Rating Curve= 0 ,0
Exp/Cntr=0.3,0.1

Type RM Length L Ch R = 1 ,20859   ,444,444,444
BEGIN DESCRIPTION:
Spring Branch 41.0
END DESCRIPTION:
XS GIS Cut Line= 3
      2143925.01     13880075.01        2143675.       13879675.
      2142474.97     13879875.01
#Sta/Elev= 30
  4527.9 1167.91  4593.4 1165.39    4739 1156.13    4782 1153.77  4846.3 1152.96
  4876.4 1151.16  4932.3 1150.86  5002.1 1147.39  5032.6 1149.02  5050.3 1148.04
  5088.3 1150.81  5121.3 1151.56  5267.4 1152.76  5469.5 1152.19  5723.8 1150.33
  5762.5 1148.48  5762.7 1147.28  5763.2 1146.78  5777.5 1147.28  5823.3 1153.52
  5841.1 1153.39  5901.9  1158.9  5939.9 1165.28    5945 1164.82  5962.7 1169.79
  5972.9 1171.29  6074.2 1175.36  6114.8 1179.12  6183.2 1182.98  6216.2 1183.69
#Mann= 9 ,-1 , 0
  4527.9     .12       0    4739     .07       0  4932.3     .12       0
  5121.3    .035       0  5267.4     .07       0  5469.5    .035       0
  5723.8     .12       0  5762.7     .05       0  5777.5     .12       0
Bank Sta=5762.7,5777.5
XS Rating Curve= 0 ,0
Exp/Cntr=0.3,0.1

Type RM Length L Ch R = 1 ,20415   ,419,419,419
BEGIN DESCRIPTION:
Spring Branch 40.0
END DESCRIPTION:
XS GIS Cut Line= 3
      2145124.98     13879924.99        2143925.       13879325.
      2142125.04     13879624.99
#Sta/Elev= 30
  3658.4 1192.82  3778.6 1183.97  3814.9 1184.44  3904.3 1176.77  3984.3 1173.46
  4092.8 1166.36  4201.3 1160.39  4470.8 1154.82  4626.5 1152.52  4907.4 1149.97
  4947.6 1147.26  4948.1 1146.76    4963 1147.26  5027.9 1147.32  5050.7 1149.08
  5081.1 1147.54  5164.7 1149.76  5265.2 1150.52  5365.6 1151.08  5506.9 1151.12
  5778.5 1147.81  5823.7 1148.22  5993.5 1158.18    6067 1160.19  6218.5 1168.77
  6419.3 1176.68  6487.8  1181.1  6601.8 1184.65    6693 1190.46  6824.8 1192.93
#Mann= 14 ,-1 , 0
  3658.4     .12       0  3984.3    .035       0  4092.8     .07       0
  4201.3    .035       0  4470.8     .07       0  4626.5    .035       0
  4907.4     .07       0  4947.6     .05       0    4963     .07       0
  5164.7    .035       0  5265.2     .07       0  5365.6    .035       0
  5778.5     .07       0  6218.5     .12       0
Bank Sta=4947.6,4963
XS Rating Curve= 0 ,0
Exp/Cntr=0.3,0.1

Type RM Length L Ch R = 1 ,19996   ,872,872,872
BEGIN DESCRIPTION:
Spring Branch 39.0
END DESCRIPTION:
XS GIS Cut Line= 3
      2145325.02     13879475.01        2144125.       13878975.
      2142324.95     13879275.01
#Sta/Elev= 30
  3704.1 1195.41  3790.2  1189.3  3954.9 1182.48  4009.1 1176.31  4084.9 1171.66
  4114.5 1167.95    4138 1167.78  4172.2  1164.4  4221.7  1162.9  4375.8  1156.4
  4711.6 1148.63  4831.2 1147.68  4883.3 1148.46    4950  1146.4    4958 1144.28
  4958.5 1143.78  4973.4 1144.28  4988.8 1144.64  5001.4 1146.65    5031 1145.16
  5190.7 1148.44  5567.6 1149.18  5761.9 1147.27  5815.2 1145.15  5883.6 1149.88
  5964.3 1150.67  6144.3 1154.98  6314.4 1159.69    6494 1167.76    6829 1182.44
#Mann= 15 ,-1 , 0
  3704.1     .12       0  4009.1    .035       0  4114.5     .12       0
  4172.2     .07       0  4221.7    .035       0  4831.2     .07       0
    4958    .035       0  4973.4     .07       0  4988.8    .035       0
    5031     .07       0  5190.7    .035       0  5567.6     .07       0
  5964.3    .045       0  6144.3    .035       0    6494     .12       0
Bank Sta=4958,4973.4
XS Rating Curve= 0 ,0
Exp/Cntr=0.3,0.1

Type RM Length L Ch R = 1 ,19124   ,216,216,216
BEGIN DESCRIPTION:
Spring Branch 38.0
END DESCRIPTION:
XS GIS Cut Line= 3
        2145125.       13878425.        2144525.       13878325.
      2143178.31      13878290.9
#Sta/Elev= 30
    4392 1165.22  4433.3 1162.44  4513.7  1159.1  4663.2 1151.05  4706.3 1149.94
  4736.7 1147.61  4816.5  1144.7  4878.6 1144.09  4911.6 1141.61  4942.5  1142.4
  4967.3 1142.13  4972.3 1141.19  4972.8 1140.69  4987.8 1141.19  5041.5 1142.93
  5070.3 1144.13    5140 1144.43  5251.9 1144.36  5280.4 1143.25  5330.4 1144.83
  5435.6 1144.56  5534.1  1143.3  5610.5 1144.87  5690.5 1143.08  5780.5 1146.14
  5829.6 1145.98  5928.1 1146.91  6072.5 1147.86  6223.6    1150  6347.4 1148.76
#Mann= 15 ,-1 , 0
    4392     .07       0  4433.3    .035       0  4816.5     .07       0
  4942.5     .12       0  4972.3     .05       0  4987.8     .12       0
  5041.5    .035       0    5140     .07       0  5251.9     .12       0
  5435.6     .07       0  5534.1     .12       0  5829.6     .07       0
  5928.1    .035       0  6072.5     .07       0  6223.6    .045       0
Bank Sta=4972.3,4987.8
XS Rating Curve= 0 ,0
Exp/Cntr=0.3,0.1

Type RM Length L Ch R = 1 ,18908   ,266,266,266
BEGIN DESCRIPTION:
Spring Branch 37.5
END DESCRIPTION:
XS GIS Cut Line= 3
      2145280.96     13878177.53       2144575.4     13878125.17
      2143325.67     13878099.06
#Sta/Elev= 30
  4292.5 1173.79  4327.4 1170.86  4395.4 1166.34  4458.9  1160.9  4539.1 1156.21
  4609.3 1154.09    4792 1145.56    4870 1144.97  4890.1 1142.73  4936.2 1141.91
  4939.3 1141.55  5012.6 1137.93  5013.1 1137.43  5028.2 1137.93  5060.4 1141.16
  5110.4 1142.47  5282.6 1142.55  5340.5 1141.48  5380.5 1142.81  5440.5 1141.47
  5530.5 1144.54  5580.5 1143.78  5590.5 1144.64  5620.5 1142.43  5660.5 1141.96
  5700.6  1142.3  5725.9 1144.78  5760.7 1145.33  5993.5 1146.14    6250 1147.42
#Mann= 11 ,-1 , 0
  4292.5    .035       0  4327.4     .07       0  4395.4    .035       0
    4792     .07       0  4936.2     .12       0  4939.3     .07       0
  5012.6     .05       0  5028.2     .07       0  5282.6     .12       0
  5760.7    .035       0  5993.5     .07       0
Bank Sta=5012.6,5028.2
XS Rating Curve= 0 ,0
Exp/Cntr=0.3,0.1

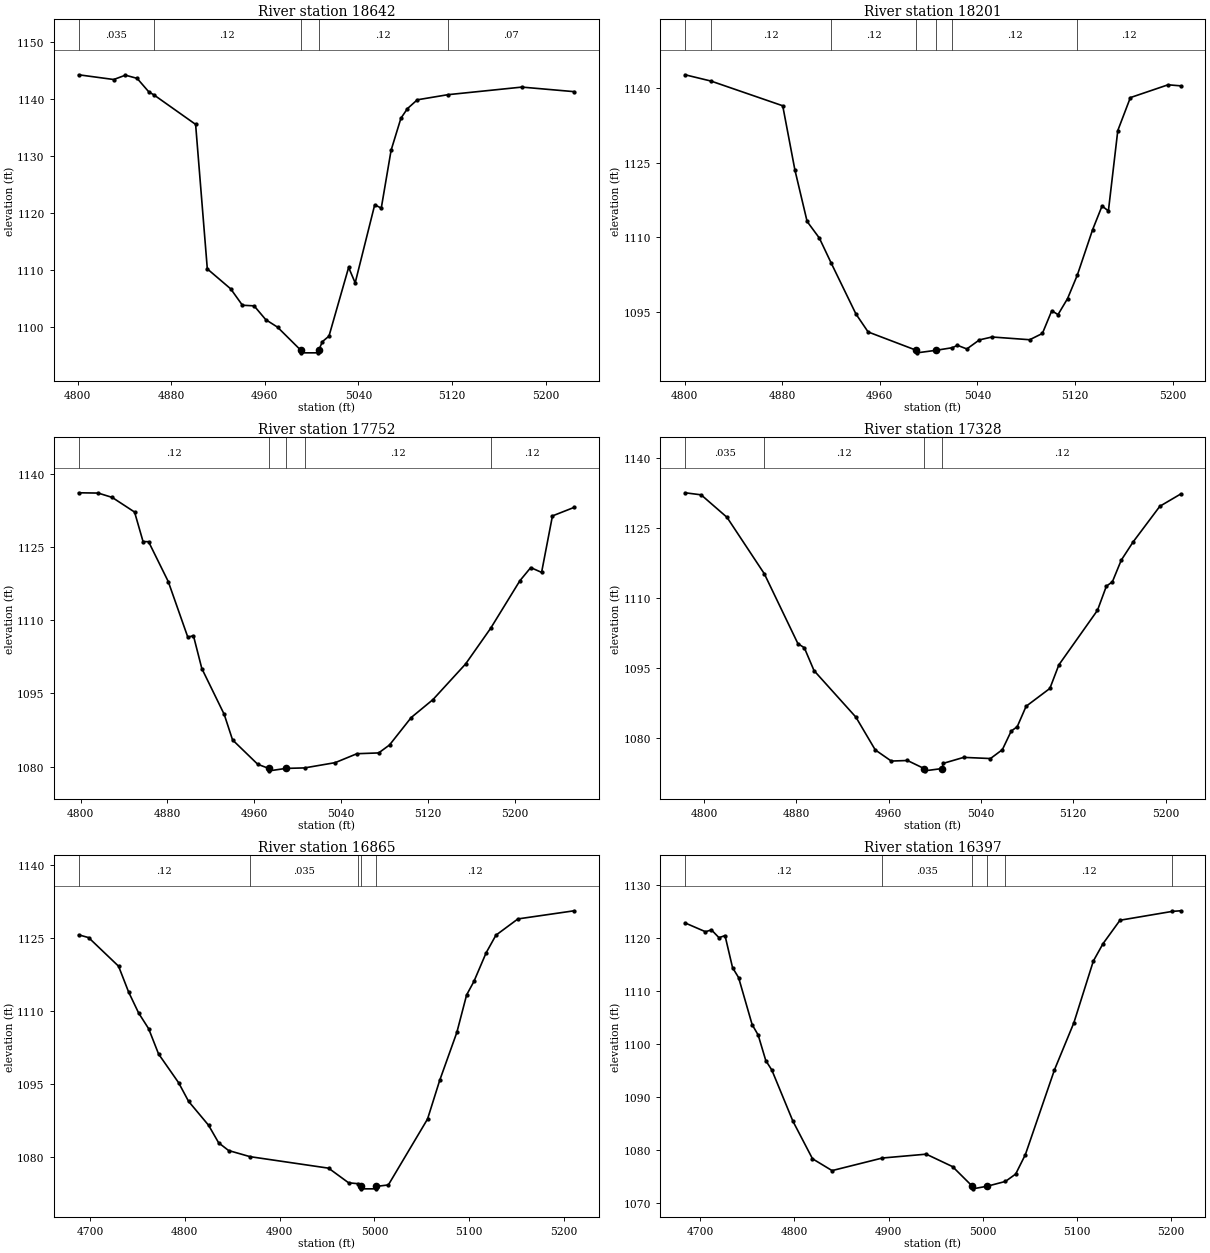
Type RM Length L Ch R = 1 ,18642   ,441,441,441
BEGIN DESCRIPTION:
Spring Branch 37.0
END DESCRIPTION:
XS GIS Cut Line= 3
      2144825.04       13877875.        2144625.       13877875.
      2144425.04     13877974.98
#Sta/Elev= 30
  4800.8  1144.2  4830.8 1143.37  4840.8 1144.13  4850.8 1143.57  4860.8  1141.2
  4865.1 1140.68  4900.8  1135.5  4910.8 1110.15  4930.8 1106.65  4940.8 1103.78
  4950.8 1103.67  4960.8 1101.24  4970.8 1099.94  4990.5 1095.93    4991 1095.43
  5005.6 1095.43  5006.1 1095.93  5009.2  1097.4  5014.8 1098.36  5031.6 1110.41
  5037.2  1107.7  5053.9  1121.4  5059.5 1120.81  5067.9 1130.96  5076.3 1136.58
  5081.9 1138.27  5090.3 1139.81  5116.5 1140.71  5179.7 1142.04  5224.4 1141.24
#Mann= 5 ,-1 , 0
  4800.8    .035       0  4865.1     .12       0  4990.5     .05       0
  5006.1     .12       0  5116.5     .07       0
Bank Sta=4990.5,5006.1
XS Rating Curve= 0 ,0
Exp/Cntr=0.3,0.1

Type RM Length L Ch R = 1 ,18201   ,449,449,449
BEGIN DESCRIPTION:
Spring Branch 36.0
END DESCRIPTION:
XS GIS Cut Line= 3
      2144824.99       13877525.        2144625.       13877525.
      2144425.04     13877574.99
#Sta/Elev= 30
  4800.4 1142.64  4821.6 1141.38  4880.4 1136.42  4890.4 1123.52  4900.4  1113.2
  4910.4 1109.88  4920.1 1104.87  4940.4 1094.64  4950.4 1091.03    4990 1087.34
  4990.5 1086.84  5005.8 1087.34  5019.4 1087.87  5023.6 1088.35  5031.3 1087.62
  5041.6 1089.44  5051.9 1090.02  5082.8 1089.47  5093.2 1090.73  5100.9 1095.29
    5106 1094.51  5113.8 1097.71  5121.8 1102.42  5134.4 1111.58  5142.1 1116.31
  5147.3 1115.31    5155 1131.45  5165.3 1138.06  5196.2 1140.63  5206.5 1140.42
#Mann= 7 ,-1 , 0
  4800.4    .035       0  4821.6     .12       0  4920.1     .12       0
    4990     .05       0  5005.8     .12       0  5019.4     .12       0
  5121.8     .12       0
Bank Sta=4990,5005.8
XS Rating Curve= 0 ,0
Exp/Cntr=0.3,0.1

Type RM Length L Ch R = 1 ,17752   ,424,424,424
BEGIN DESCRIPTION:
Spring Branch 35.0
END DESCRIPTION:
XS GIS Cut Line= 3
        2144825.       13877125.        2144625.       13877075.
      2144374.96       13877075.
#Sta/Elev= 30
  4798.2 1136.12  4816.2 1136.06  4829.1 1135.17  4849.7 1132.17  4857.5 1126.13
  4862.6 1126.09  4880.7 1117.93  4898.7 1106.54  4903.9 1106.83  4911.6 1100.11
  4932.2 1090.72  4939.9 1085.48  4963.1 1080.48  4973.2 1079.64  4973.7 1079.14
  4989.1 1079.64  5006.2 1079.74  5034.4 1080.82  5054.4 1082.65  5074.4 1082.81
  5084.4 1084.44  5104.4 1090.07  5124.4 1093.74  5154.4 1101.03  5177.5 1108.35
  5204.4 1118.09  5214.4 1120.79  5224.4 1119.81  5234.4 1131.38  5254.4 1133.13
#Mann= 5 ,-1 , 0
  4798.2     .12       0  4973.2     .05       0  4989.1     .12       0
  5006.2     .12       0  5177.5     .12       0
Bank Sta=4973.2,4989.1
XS Rating Curve= 0 ,0
Exp/Cntr=0.3,0.1

Type RM Length L Ch R = 1 ,17328   ,463,463,463
BEGIN DESCRIPTION:
Spring Branch 34.0
END DESCRIPTION:
XS GIS Cut Line= 3
      2144874.97     13876824.98        2144675.       13876725.
      2144475.02     13876675.01
#Sta/Elev= 30
  4783.4 1132.58  4797.3 1132.14  4819.7 1127.32  4852.1 1115.19  4881.2  1100.2
  4886.8  1099.3  4895.2  1094.4  4931.5 1084.41  4948.3 1077.37  4962.2 1074.98
  4976.2  1075.1  4990.6 1073.38  4991.1 1072.88  5006.5 1073.38    5007 1074.47
    5025 1075.77  5048.2 1075.52  5058.5 1077.42  5066.2 1081.42  5071.4 1082.35
  5079.1 1086.74  5099.7 1090.57  5107.5 1095.63    5141 1107.35  5148.7 1112.53
  5153.9 1113.46  5161.6 1118.11  5171.9 1122.03  5195.1 1129.69  5213.1 1132.31
#Mann= 4 ,-1 , 0
  4783.4    .035       0  4852.1     .12       0  4990.6     .05       0
  5006.5     .12       0
Bank Sta=4990.6,5006.5
XS Rating Curve= 0 ,0
Exp/Cntr=0.3,0.1

Type RM Length L Ch R = 1 ,16865   ,468,468,468
BEGIN DESCRIPTION:
Spring Branch 33.0
END DESCRIPTION:
XS GIS Cut Line= 3
      2145074.98     13876424.99        2144775.       13876325.
      2144574.97     13876274.99
#Sta/Elev= 30
  4688.1 1125.59  4698.6 1125.02  4730.2 1119.15  4740.8 1113.85  4751.3 1109.57
  4761.9 1106.33  4772.4 1101.13  4793.5 1095.25    4804 1091.43  4825.1 1086.52
  4835.7 1082.92  4846.2 1081.34  4868.8 1080.08  4951.6 1077.72  4972.7 1074.72
  4982.8 1074.53  4985.8 1073.98  4986.3 1073.48  5001.3 1073.48  5001.8 1073.98
  5014.6 1074.28  5055.9 1087.79  5068.7 1095.71  5086.8 1105.56  5097.1 1113.25
  5104.8 1116.02  5117.7  1121.9    5128 1125.51  5151.2 1128.85  5210.5 1130.52
#Mann= 5 ,-1 , 0
  4688.1     .12       0  4868.8    .035       0  4982.8     .12       0
  4985.8     .05       0  5001.8     .12       0
Bank Sta=4985.8,5001.8
XS Rating Curve= 0 ,0
Exp/Cntr=0.3,0.1

Type RM Length L Ch R = 1 ,16397   ,449,449,449
BEGIN DESCRIPTION:
Spring Branch 32.0
END DESCRIPTION:
XS GIS Cut Line= 3
      2145275.01     13876225.01        2145075.       13875975.
        2145025.     13875775.02
#Sta/Elev= 30
  4683.9 1122.91  4705.5 1121.25  4711.9 1121.59  4719.9 1120.12  4726.3 1120.52
  4734.3 1114.45  4740.7 1112.58  4755.1 1103.68  4761.5 1101.71  4769.6 1096.87
    4776 1095.09  4798.4 1085.41  4819.2  1078.3    4840 1076.06  4893.4 1078.44
    4940 1079.17    4968 1076.81  4988.9 1073.11  4989.4 1072.61  5004.9 1073.11
  5024.1 1074.01    5035 1075.41  5045.3 1079.09  5076.2 1095.12  5096.8 1104.02
  5117.5 1115.71  5127.8    1119  5145.8 1123.42  5201.5  1125.1  5210.2 1125.21
#Mann= 6 ,-1 , 0
  4683.9     .12       0  4893.4    .035       0  4988.9    .035       0
  5004.9    .035       0  5024.1     .12       0  5201.5     .07       0
Bank Sta=4988.9,5004.9
XS Rating Curve= 0 ,0
Exp/Cntr=0.3,0.1

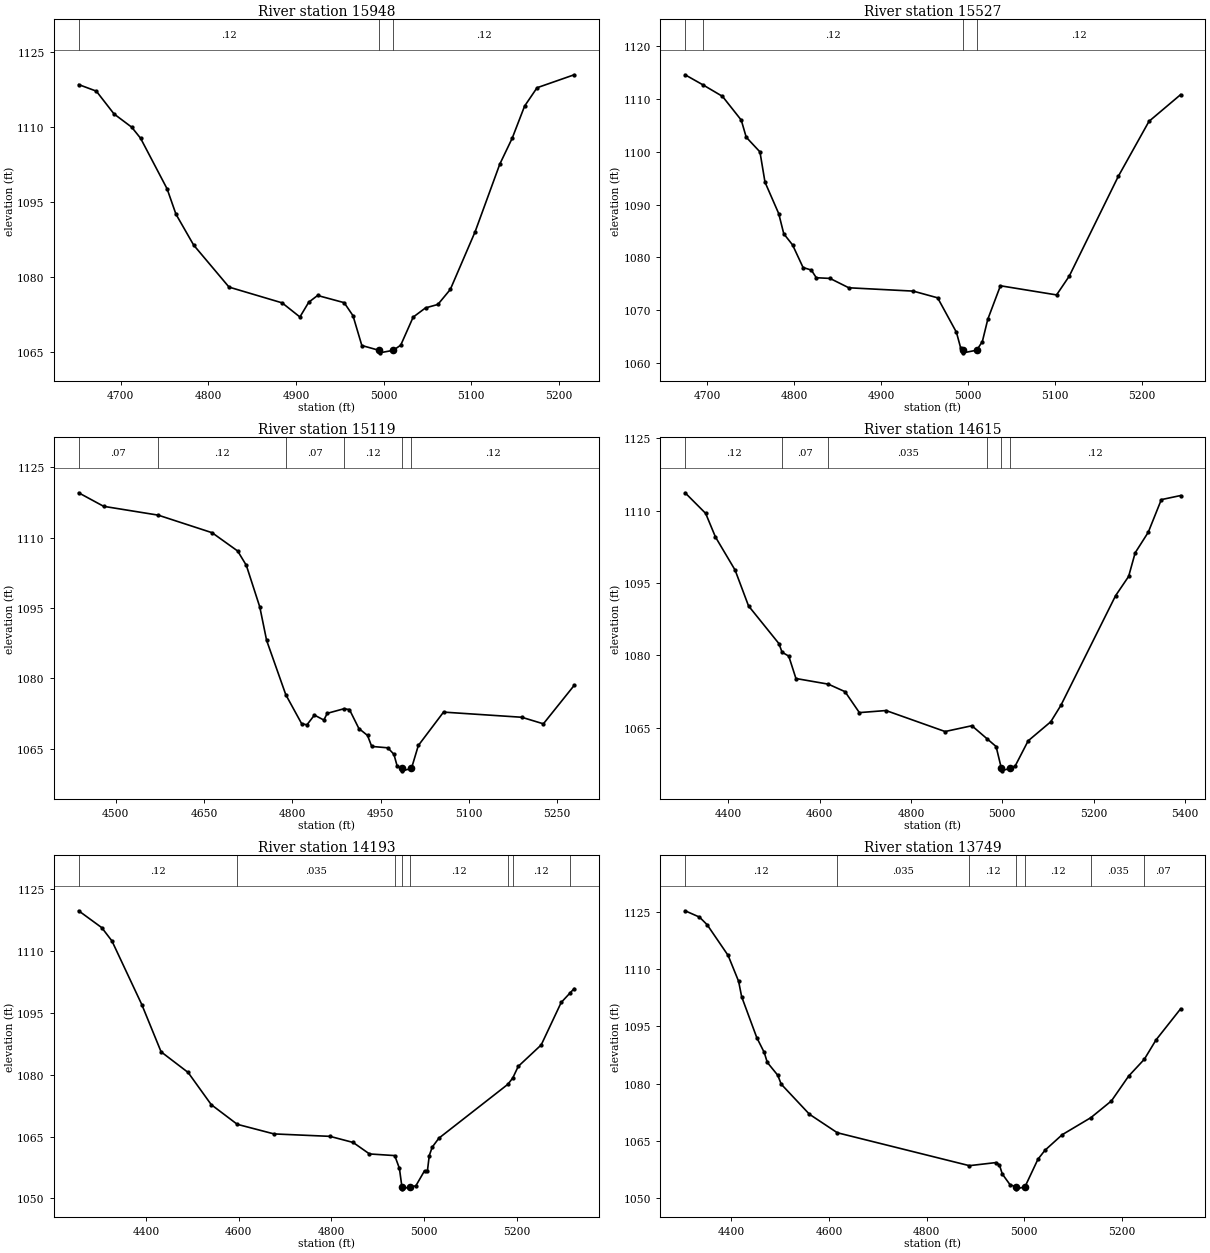
Type RM Length L Ch R = 1 ,15948   ,421,421,421
BEGIN DESCRIPTION:
Spring Branch 31.0
END DESCRIPTION:
XS GIS Cut Line= 3
        2145425.     13876175.01        2145475.       13875825.
        2145325.       13875675.
#Sta/Elev= 30
  4651.9 1118.55  4672.1 1117.23  4692.3 1112.66  4712.5    1110  4722.6 1107.79
  4752.9 1097.64    4763 1092.56  4783.2 1086.37  4823.6 1077.94  4884.2 1074.78
  4904.5 1071.95  4914.6 1074.91  4924.7 1076.26    4955 1074.82  4965.1 1072.21
  4975.2 1066.23  4994.9 1065.26  4995.4 1064.76    5011 1065.26  5019.6  1066.3
  5033.8 1071.92  5047.9 1073.77    5062 1074.46  5076.2 1077.47  5104.5 1089.03
  5132.7  1102.6  5146.9 1107.81    5161 1114.23  5175.2 1117.91  5217.6 1120.51
#Mann= 3 ,-1 , 0
  4651.9     .12       0  4994.9     .05       0    5011     .12       0
Bank Sta=4994.9,5011
XS Rating Curve= 0 ,0
Exp/Cntr=0.3,0.1

Type RM Length L Ch R = 1 ,15527   ,408,408,408
BEGIN DESCRIPTION:
Spring Branch 30.0
END DESCRIPTION:
XS GIS Cut Line= 3
       2145983.9     13875902.79        2145825.       13875625.
      2145625.02     13875475.02
#Sta/Elev= 30
  4674.5 1114.54  4695.3 1112.61  4717.5 1110.46  4739.1 1105.97  4744.8 1102.74
  4760.6 1099.96  4766.4 1094.24  4782.2 1088.29    4788 1084.48  4798.1 1082.38
  4810.2  1078.1  4819.7 1077.62  4825.4 1076.17  4841.2 1076.04  4862.8 1074.27
  4936.9 1073.64    4965 1072.37  4986.6 1065.86  4991.6 1062.82  4993.8 1062.47
  4994.3 1061.97  5009.9 1062.47  5016.4 1064.09  5022.7 1068.33  5037.2 1074.65
  5101.8 1072.92  5116.4 1076.48  5172.7 1095.31  5208.1 1105.74  5244.5 1110.79
#Mann= 4 ,-1 , 0
  4674.5    .035       0  4695.3     .12       0  4993.8     .05       0
  5009.9     .12       0
Bank Sta=4993.8,5009.9
XS Rating Curve= 0 ,0
Exp/Cntr=0.3,0.1

Type RM Length L Ch R = 1 ,15119   ,504,504,504
BEGIN DESCRIPTION:
Spring Branch 29.0
END DESCRIPTION:
XS GIS Cut Line= 3
      2146312.47     13875803.92      2146038.97     13875311.93
      2145763.28     13875353.44
#Sta/Elev= 30
  4437.1 1119.59  4479.6  1116.7  4572.2 1114.82  4663.8 1111.07  4707.2 1107.17
  4721.9 1104.12  4744.8 1095.23  4756.4  1088.1    4789  1076.5  4815.9 1070.33
  4824.9 1070.09  4837.6 1072.16  4853.6 1071.11  4859.4 1072.54  4887.9 1073.52
  4897.1 1073.34  4913.1  1069.3  4927.8 1067.82  4934.9 1065.48  4962.3 1065.18
  4972.6  1063.8  4978.3 1061.22  4986.2 1060.77  4986.7 1060.27  5002.4 1060.77
  5014.1 1065.68  5056.9  1072.8  5189.8  1071.7  5226.5  1070.3  5278.8  1078.5
#Mann= 6 ,-1 , 0
  4437.1     .07       0  4572.2     .12       0    4789     .07       0
  4887.9     .12       0  4986.2     .05       0  5002.4     .12       0
Bank Sta=4986.2,5002.4
XS Rating Curve= 0 ,0
Exp/Cntr=0.3,0.1

Type RM Length L Ch R = 1 ,14615   ,422,422,422
BEGIN DESCRIPTION:
Spring Branch 28.0
END DESCRIPTION:
XS GIS Cut Line= 3
      2146824.98     13875224.99        2146225.       13874875.
      2145925.01     13874625.01
#Sta/Elev= 30
  4305.4  1113.7  4350.4 1109.43  4371.9 1104.53  4414.9 1097.67  4444.3 1090.25
  4510.9 1082.43  4517.7 1080.65  4532.4 1079.84  4548.1  1075.2    4619 1074.03
  4655.6 1072.47    4687 1068.13  4745.3 1068.56  4874.7 1064.21  4933.4 1065.41
  4966.8 1062.69  4986.4  1061.1    4998 1056.56  4998.5 1056.06  5016.3 1056.56
    5028 1057.03  5056.6 1062.28  5106.1 1066.23  5128.2 1069.62    5248 1092.36
  5276.6 1096.36  5290.9 1101.25  5319.6 1105.52  5348.2 1112.28  5390.5 1113.13
#Mann= 6 ,-1 , 0
  4305.4     .12       0  4517.7     .07       0    4619    .035       0
  4966.8     .12       0    4998     .05       0  5016.3     .12       0
Bank Sta=4998,5016.3
XS Rating Curve= 0 ,0
Exp/Cntr=0.3,0.1

Type RM Length L Ch R = 1 ,14193   ,444,444,444
BEGIN DESCRIPTION:
Spring Branch 27.0
END DESCRIPTION:
XS GIS Cut Line= 3
      2147024.98     13874974.99        2146425.       13874525.
      2146175.03     13874325.02
#Sta/Elev= 30
  4254.4  1119.8  4304.4  1115.7  4326.3 1112.48  4390.8 1097.03  4432.5 1085.56
  4490.8 1080.56  4540.8 1072.74    4597 1067.97  4676.3 1065.64  4797.1 1065.05
  4847.1 1063.57  4882.5 1060.78    4937 1060.38  4947.1 1057.29  4952.5 1052.81
    4953 1052.31  4970.8 1052.81  4982.5 1053.02  5001.3 1056.68  5007.6 1056.68
  5011.6 1060.38    5018 1062.44  5032.4 1064.61  5181.4 1077.69  5191.9 1079.22
  5203.7 1082.03  5253.3 1087.24  5296.5 1097.55  5315.1 1099.79  5324.5 1100.92
#Mann= 8 ,-1 , 0
  4254.4     .12       0    4597    .035       0    4937     .12       0
  4952.5     .05       0  4970.8     .12       0  5181.4     .07       0
  5191.9     .12       0  5315.1    .035       0
Bank Sta=4952.5,4970.8
XS Rating Curve= 0 ,0
Exp/Cntr=0.3,0.1

Type RM Length L Ch R = 1 ,13749   ,467,467,467
BEGIN DESCRIPTION:
Spring Branch 26.0
END DESCRIPTION:
XS GIS Cut Line= 3
        2147375.       13874625.        2146775.       13874275.
      2146524.98     13874074.98
#Sta/Elev= 30
  4305.4 1125.23  4334.8 1123.58  4350.5 1121.59  4393.5 1113.55    4415 1106.78
  4421.2 1102.76  4452.2 1092.05  4467.5 1088.17  4473.7 1085.58  4495.2 1082.21
  4502.2 1079.89  4560.1 1072.01  4617.1 1067.18  4887.5 1058.57  4942.1 1059.38
  4949.2 1058.73  4954.9 1056.41  4970.7 1053.61    4983 1053.01  4983.5 1052.51
  5001.3 1053.01    5028 1060.26  5042.4  1062.6  5077.7 1066.67  5136.5 1071.14
  5178.5 1075.51  5213.7 1081.99  5245.9 1086.41  5269.7 1091.44  5320.2  1099.6
#Mann= 7 ,-1 , 0
  4305.4     .12       0  4617.1    .035       0  4887.5     .12       0
    4983     .05       0  5001.3     .12       0  5136.5    .035       0
  5245.9     .07       0
Bank Sta=4983,5001.3
XS Rating Curve= 0 ,0
Exp/Cntr=0.3,0.1

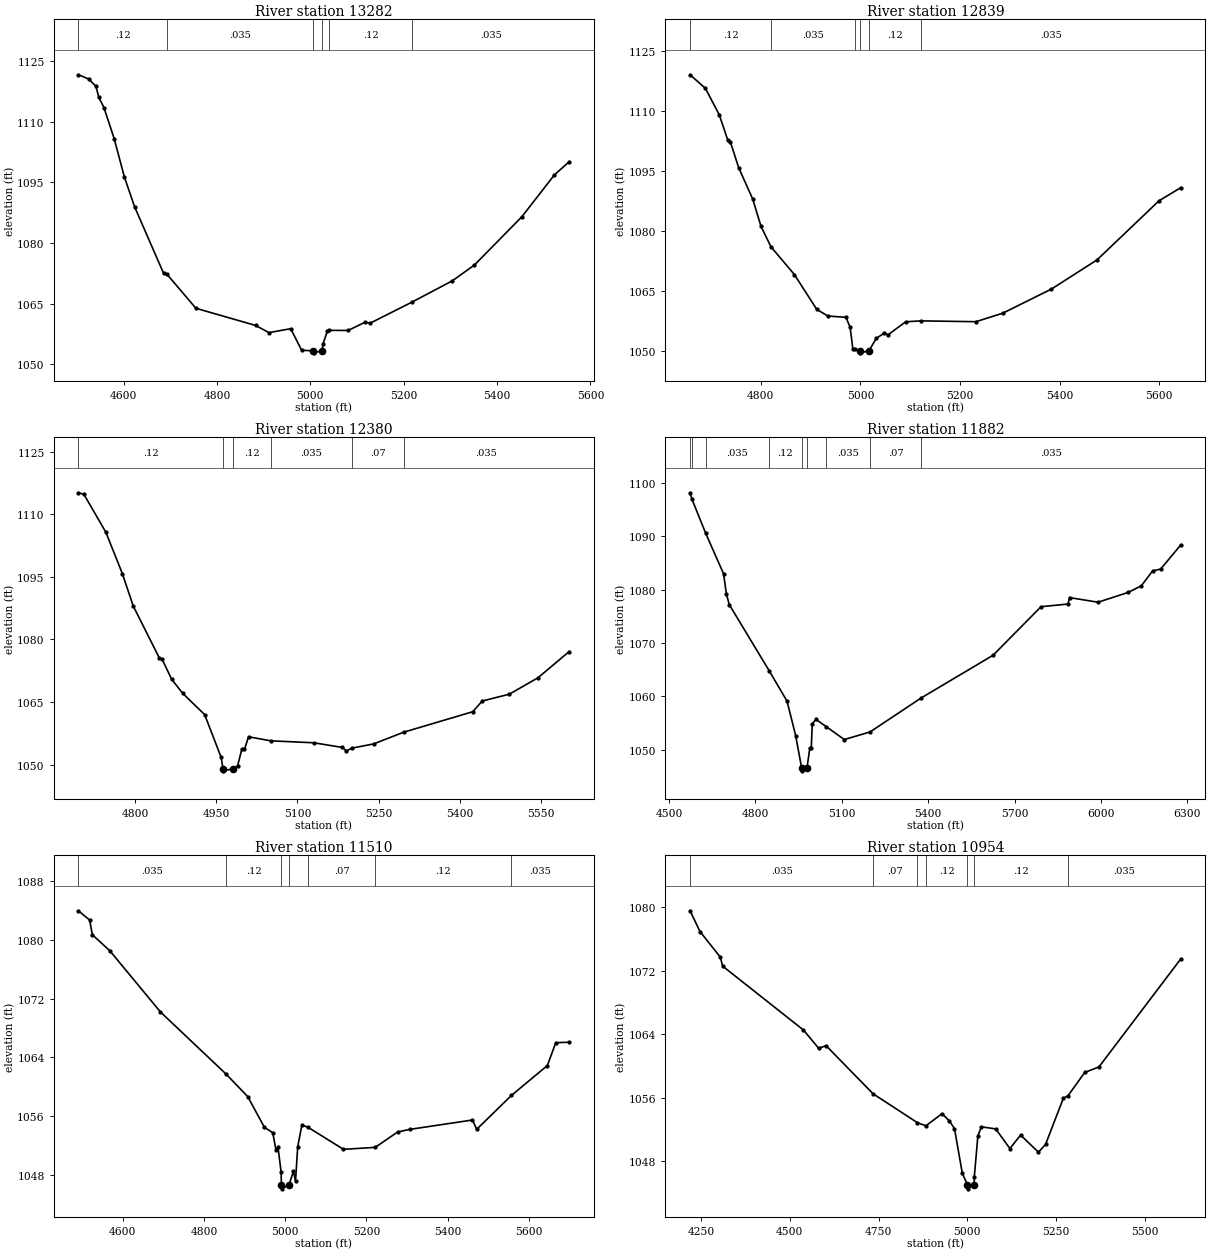
Type RM Length L Ch R = 1 ,13282   ,443,443,443
BEGIN DESCRIPTION:
Spring Branch 25.0
END DESCRIPTION:
XS GIS Cut Line= 3
      2147574.99     13874174.99        2147125.       13873975.
      2146575.05     13873875.01
#Sta/Elev= 30
  4503.3 1121.57  4525.2 1120.53  4540.9 1118.72  4547.1 1115.96    4558 1113.48
  4579.9  1105.8  4601.8 1096.32  4623.7 1088.94  4685.9 1072.47  4692.9 1072.29
    4755 1063.87  4882.9 1059.63  4911.6 1057.85  4958.1 1058.83  4981.4  1053.5
  5006.9 1053.36  5007.4 1052.86  5025.3 1053.36  5027.5 1055.12  5036.4 1058.17
    5041 1058.42  5080.9 1058.39  5117.7 1060.44  5127.9 1060.17  5218.1 1065.41
  5304.5 1070.67  5351.5 1074.55  5453.1 1086.47    5523 1096.84  5554.7 1100.09
#Mann= 6 ,-1 , 0
  4503.3     .12       0  4692.9    .035       0  5006.9    .035       0
  5025.3    .035       0    5041     .12       0  5218.1    .035       0
Bank Sta=5006.9,5025.3
XS Rating Curve= 0 ,0
Exp/Cntr=0.3,0.1

Type RM Length L Ch R = 1 ,12839   ,459,459,459
BEGIN DESCRIPTION:
Spring Branch 24.0
END DESCRIPTION:
XS GIS Cut Line= 3
      2147724.99       13873825.        2147425.       13873675.
        2146825.       13873425.
#Sta/Elev= 30
    4658 1118.96  4688.7 1115.59  4716.7 1108.96  4733.5 1102.73  4739.1 1102.12
  4755.8 1095.69  4783.8 1087.92  4800.5 1081.08  4820.5 1075.96  4867.6 1069.02
  4912.3 1060.34  4934.7 1058.67    4971 1058.35  4979.4 1055.85    4985 1050.37
  4989.2 1050.38  4998.8 1049.97  4999.3 1049.47  5017.2 1049.97  5031.9  1053.1
  5047.6 1054.36  5055.7 1053.99  5090.9 1057.23  5121.5 1057.46  5231.7 1057.25
  5285.9 1059.38  5383.4  1065.4  5474.9 1072.68  5599.5 1087.47  5643.4 1090.76
#Mann= 6 ,-1 , 0
    4658     .12       0  4820.5    .035       0  4989.2     .12       0
  4998.8     .05       0  5017.2     .12       0  5121.5    .035       0
Bank Sta=4998.8,5017.2
XS Rating Curve= 0 ,0
Exp/Cntr=0.3,0.1

Type RM Length L Ch R = 1 ,12380   ,498,498,498
BEGIN DESCRIPTION:
Spring Branch 23.0
END DESCRIPTION:
XS GIS Cut Line= 3
      2147874.97     13873324.99        2147575.       13873275.
      2146974.99       13873325.
#Sta/Elev= 30
  4695.5 1115.12  4705.6 1114.77  4746.2 1105.67  4776.6 1095.78  4796.8 1087.98
    4845 1075.54  4850.1 1075.22  4867.8 1070.43  4888.1 1067.08  4928.6 1061.99
  4959.1 1051.73  4962.5 1049.02    4963 1048.52  4980.9 1049.02  4989.5 1049.76
  4997.1 1053.64  5002.1 1053.64  5009.6 1056.68  5050.5 1055.71  5130.1 1055.24
  5182.7 1054.13  5190.3  1053.3  5200.8 1053.97  5240.4 1054.96  5296.2 1057.78
  5423.6 1062.68  5441.1 1065.24  5491.3 1066.89    5544 1070.81  5601.7  1077.1
#Mann= 6 ,-1 , 0
  4695.5     .12       0  4962.5     .05       0  4980.9     .12       0
  5050.5    .035       0  5200.8     .07       0  5296.2    .035       0
Bank Sta=4962.5,4980.9
XS Rating Curve= 0 ,0
Exp/Cntr=0.3,0.1

Type RM Length L Ch R = 1 ,11882   ,372,372,372
BEGIN DESCRIPTION:
Spring Branch 22.0
END DESCRIPTION:
XS GIS Cut Line= 3
      2148001.11     13872836.31      2147575.15     13872809.58
      2146348.96     13873168.69
#Sta/Elev= 30
  4573.2  1098.2  4580.1 1096.96  4627.4 1090.62  4689.5 1083.02  4699.6 1079.18
  4709.6  1077.2    4848 1064.82    4910 1059.11    4940 1052.65  4960.9 1046.54
  4961.4 1046.04  4979.3 1046.54  4989.2 1050.37  4994.2 1050.26  4997.6 1054.88
  5010.6 1055.68  5046.2 1054.33  5108.9 1051.91  5198.2 1053.33  5376.4 1059.73
  5625.4 1067.72  5792.1 1076.83  5885.8 1077.33    5891 1078.54  5990.1 1077.67
  6094.3  1079.5  6140.6 1080.76  6179.2 1083.53  6207.4 1083.89  6277.7 1088.44
#Mann= 9 ,-1 , 0
  4573.2    .035       0  4580.1     .12       0  4627.4    .035       0
    4848     .12       0  4960.9     .05       0  4979.3     .12       0
  5046.2    .035       0  5198.2     .07       0  5376.4    .035       0
Bank Sta=4960.9,4979.3
XS Rating Curve= 0 ,0
Exp/Cntr=0.3,0.1

Type RM Length L Ch R = 1 ,11510   ,556,556,556
BEGIN DESCRIPTION:
Spring Branch 21.0
END DESCRIPTION:
XS GIS Cut Line= 2
      2148071.99     13872577.93      2146892.57     13872311.21
#Sta/Elev= 30
  4490.6 1083.95  4518.3 1082.69    4525 1080.69  4568.1 1078.51  4692.6  1070.2
  4855.1 1061.71  4907.9 1058.67  4948.9  1054.5  4969.4 1053.78  4977.2 1051.45
  4982.3 1051.84  4989.9 1048.46  4990.9 1046.64  4991.4 1046.14  5009.3 1046.64
  5020.4 1048.53  5025.5  1047.2  5030.9 1051.87  5041.2 1054.81  5055.7 1054.53
  5143.7 1051.51  5221.9 1051.78    5277 1053.87  5307.7 1054.23  5461.5  1055.5
  5471.8 1054.23  5557.4 1058.84    5646 1062.91  5666.6 1066.01  5699.8 1066.08
#Mann= 7 ,-1 , 0
  4490.6    .035       0  4855.1     .12       0  4990.9     .05       0
  5009.3     .12       0  5055.7     .07       0  5221.9     .12       0
  5557.4    .035       0
Bank Sta=4990.9,5009.3
XS Rating Curve= 0 ,0
Exp/Cntr=0.3,0.1

Type RM Length L Ch R = 1 ,10954   ,246,246,246
BEGIN DESCRIPTION:
Spring Branch 20.0
END DESCRIPTION:
XS GIS Cut Line= 3
      2148124.99     13872424.99        2147525.       13871925.
      2146924.99       13871875.
#Sta/Elev= 30
  4218.9 1079.54  4246.9 1076.93  4304.2 1073.71  4310.7 1072.58  4538.5 1064.54
  4581.4 1062.24  4602.2 1062.57  4734.6 1056.52  4859.7 1052.88  4883.5 1052.49
    4929 1054.02  4949.8  1053.1  4964.1 1052.13  4986.2  1046.5  5000.6 1045.06
  5001.1 1044.56  5019.3 1045.06    5020  1046.1    5030 1051.24  5040.1 1052.36
  5080.2  1052.1  5120.3 1049.63  5150.4 1051.33  5200.6 1049.17  5220.7 1050.15
  5270.8 1055.95  5283.9 1056.27  5331.1  1059.2  5371.2  1059.9    5602  1073.5
#Mann= 7 ,-1 , 0
  4218.9    .035       0  4734.6     .07       0  4859.7    .035       0
  4883.5     .12       0  5000.6     .05       0  5019.3     .12       0
  5283.9    .035       0
Bank Sta=5000.6,5019.3
XS Rating Curve= 0 ,0
Exp/Cntr=0.3,0.1