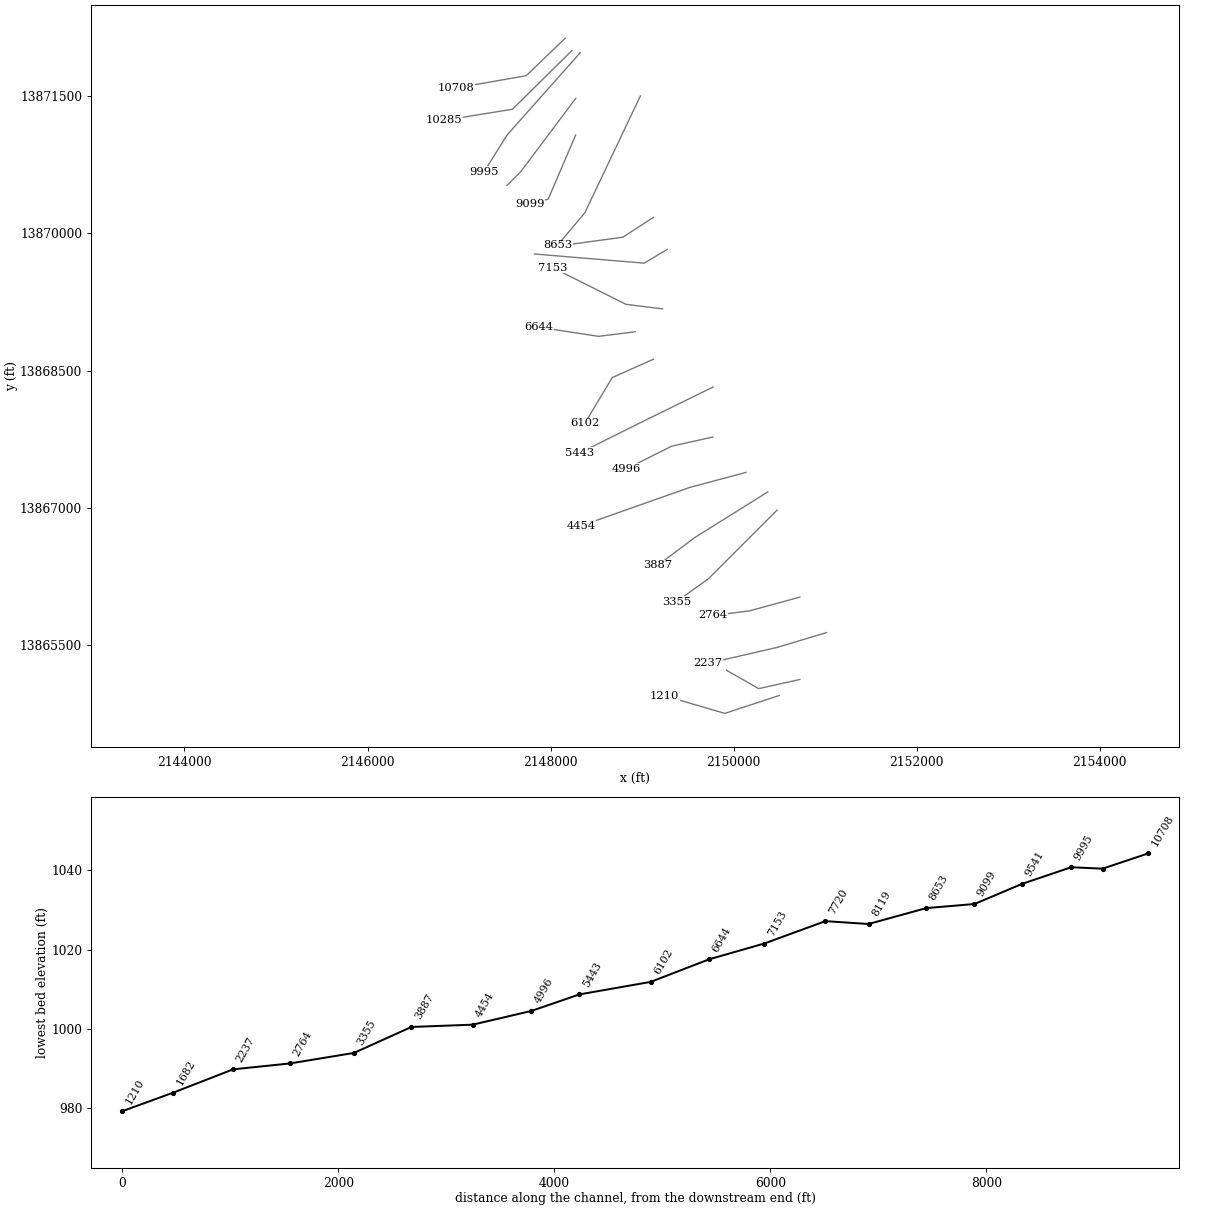
HEC-RAS study Spring Branch.prj: Spring Branch Base Level Engineering

--- Spring Branch.g01 (geometry) --- (continued)

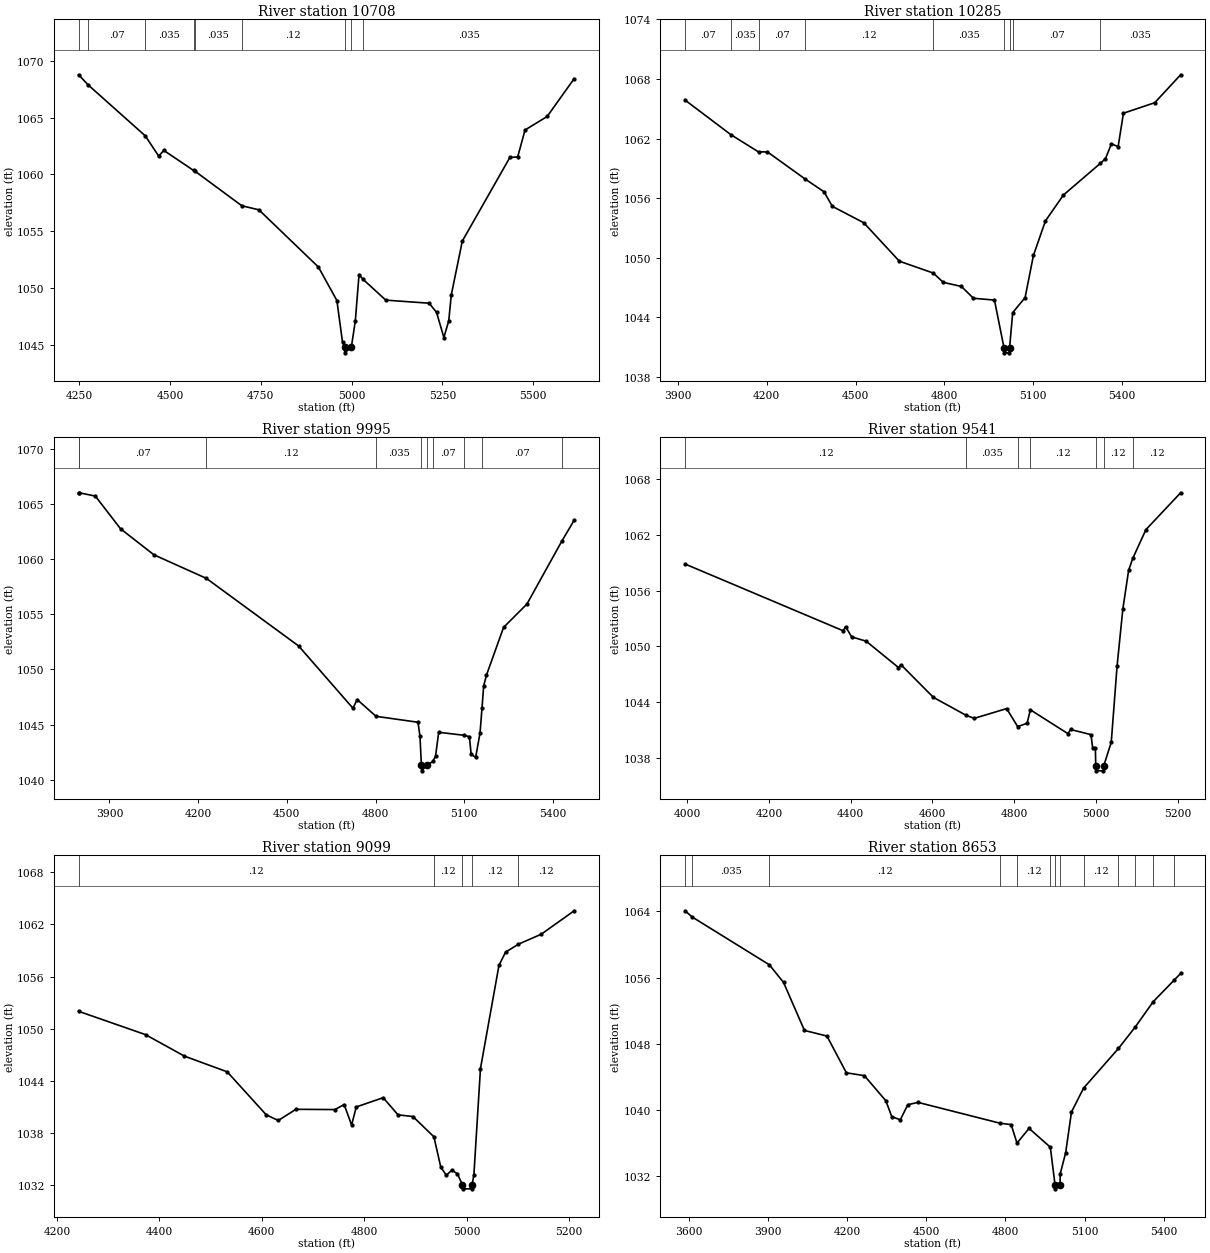
Type RM Length L Ch R = 1 ,10708   ,423,423,423
BEGIN DESCRIPTION:
Spring Branch 19.1
END DESCRIPTION:
XS GIS Cut Line= 3
      2148159.48     13872131.98      2147734.43     13871723.61
      2146971.84     13871590.26
#Sta/Elev= 30
  4248.9 1068.77    4275 1067.88  4432.4 1063.39  4469.2 1061.61  4483.3 1062.11
  4565.1 1060.35  4568.3  1060.3  4697.9 1057.24    4745 1056.88  4908.8 1051.84
  4959.6 1048.89  4975.1 1045.21  4980.7 1044.79  4981.2 1044.29  4999.4 1044.79
  5010.3 1047.11  5020.5 1051.18  5031.6 1050.76  5094.1 1048.93  5213.4 1048.66
  5233.7 1047.86    5254 1045.64  5267.4 1047.12  5274.3 1049.38  5304.7 1054.13
  5435.7  1061.5    5457 1061.53  5477.3 1063.91  5538.2  1065.1  5612.5 1068.43
#Mann= 9 ,-1 , 0
  4248.9    .035       0    4275     .07       0  4432.4    .035       0
  4565.1     .07       0  4568.3    .035       0  4697.9     .12       0
  4980.7     .05       0  4999.4     .12       0  5031.6    .035       0
Bank Sta=4980.7,4999.4
XS Rating Curve= 0 ,0
Exp/Cntr=0.3,0.1

Type RM Length L Ch R = 1 ,10285   ,290,290,290
BEGIN DESCRIPTION:
Spring Branch 19.0
END DESCRIPTION:
XS GIS Cut Line= 3
       2148234.5     13871998.63      2147584.41     13871356.87
      2146834.27     13871236.02
#Sta/Elev= 30
  3924.2 1065.87  4078.4  1062.4  4172.1 1060.66  4202.2 1060.66  4328.6 1057.95
  4393.1 1056.65  4421.4 1055.18  4527.5 1053.53  4647.7 1049.66  4762.1 1048.47
  4796.1 1047.53  4857.3 1047.12  4897.9 1045.93  4968.8 1045.75  5001.1 1040.94
  5001.6 1040.44  5019.4 1040.44  5019.9 1040.94  5030.4 1044.49  5072.3    1046
  5100.4 1050.24    5141 1053.72  5201.7 1056.32  5326.2  1059.5  5343.5 1059.97
  5363.8 1061.47  5386.5 1061.19  5404.3 1064.55  5510.1 1065.61  5597.5 1068.42
#Mann= 9 ,-1 , 0
  3924.2     .07       0  4078.4    .035       0  4172.1     .07       0
  4328.6     .12       0  4762.1    .035       0  5001.1    .035       0
  5019.9    .035       0  5030.4     .07       0  5326.2    .035       0
Bank Sta=5001.1,5019.9
XS Rating Curve= 0 ,0
Exp/Cntr=0.3,0.1

Type RM Length L Ch R = 1 ,9995    ,454,454,454
BEGIN DESCRIPTION:
Spring Branch 18.0
END DESCRIPTION:
XS GIS Cut Line= 3
      2148325.01     13871975.01        2147525.       13871075.
      2147274.99     13870674.98
#Sta/Elev= 30
  3795.8 1066.04  3797.7 1066.04  3852.3 1065.74  3937.6 1062.77  4050.4 1060.41
  4227.9 1058.27  4539.6 1052.14  4723.6 1046.48  4737.8 1047.27  4801.5 1045.75
  4943.5 1045.21  4950.2 1043.95    4955  1041.3  4955.5  1040.8  4973.8  1041.3
  4993.9 1041.66  5002.9 1042.14  5013.5  1044.3  5098.4 1044.03  5117.3 1043.91
  5123.2 1042.32  5138.5 1042.02  5153.3 1044.23    5160  1046.5  5165.7 1048.52
  5175.1 1049.49  5232.9 1053.82  5311.9 1055.94  5429.3 1061.62  5471.7 1063.55
#Mann= 10 ,-1 , 0
  3795.8    .035       0  3797.7     .07       0  4227.9     .12       0
  4801.5    .035       0    4955     .05       0  4973.8    .035       0
  4993.9     .07       0  5098.4    .035       0    5160     .07       0
  5429.3    .035       0
Bank Sta=4955,4973.8
XS Rating Curve= 0 ,0
Exp/Cntr=0.3,0.1

Type RM Length L Ch R = 1 ,9541    ,442,442,442
BEGIN DESCRIPTION:
Spring Branch 17.0
END DESCRIPTION:
XS GIS Cut Line= 3
        2148275.       13871475.        2147675.       13870675.
      2147525.02     13870525.02
#Sta/Elev= 30
  3994.9 1058.87  4381.4 1051.69  4387.6 1052.13  4402.2 1051.03  4437.6 1050.57
  4516.8 1047.73    4523 1048.03  4602.2 1044.52  4682.5 1042.58  4702.2 1042.26
  4781.4 1043.31  4808.4 1041.37  4831.4 1041.73  4839.4 1043.18  4931.4 1040.61
  4937.6 1041.06  4987.6 1040.51  4991.8  1039.1  4998.4  1039.1  4999.4 1037.11
  4999.9 1036.61  5018.1 1036.61  5018.6 1037.11  5037.3 1039.69  5051.5 1047.88
  5065.6 1054.02  5079.8  1058.2  5089.9 1059.48  5122.2 1062.58    5207 1066.54
#Mann= 7 ,-1 , 0
  3994.9     .12       0  4682.5    .035       0  4808.4     .12       0
  4839.4     .12       0  4999.4     .05       0  5018.6     .12       0
  5089.9     .12       0
Bank Sta=4999.4,5018.6
XS Rating Curve= 0 ,0
Exp/Cntr=0.3,0.1

Type RM Length L Ch R = 1 ,9099    ,446,446,446
BEGIN DESCRIPTION:
Spring Branch 16.0
END DESCRIPTION:
XS GIS Cut Line= 3
      2148275.01     13871075.03        2147975.       13870375.
      2147774.97     13870324.99
#Sta/Elev= 30
  4242.3 1051.99  4372.9  1049.3    4449 1046.82  4532.5 1045.01  4608.6 1040.06
  4632.2  1039.4  4666.6 1040.69  4742.8 1040.66  4760.9 1041.24  4775.4 1038.87
  4784.5 1040.96  4837.1 1042.03  4866.1 1040.05  4895.1 1039.86  4936.2 1037.52
  4949.5 1034.04  4960.4 1033.08  4971.3 1033.68  4982.2 1033.24  4991.6 1032.02
  4992.1 1031.52  5010.3 1031.52  5010.8 1032.02  5014.2  1033.1  5027.1 1045.39
  5063.2 1057.28  5076.1 1058.81  5101.3 1059.73  5145.6 1060.87  5210.1 1063.58
#Mann= 5 ,-1 , 0
  4242.3     .12       0  4936.2     .12       0  4991.6     .05       0
  5010.8     .12       0  5101.3     .12       0
Bank Sta=4991.6,5010.8
XS Rating Curve= 0 ,0
Exp/Cntr=0.3,0.1

Type RM Length L Ch R = 1 ,8653    ,534,534,534
BEGIN DESCRIPTION:
Spring Branch 15.0
END DESCRIPTION:
XS GIS Cut Line= 3
      2148982.44     13871502.26        2148375.       13870225.
      2148076.21     13869870.33
#Sta/Elev= 30
  3585.7 1064.07  3611.5 1063.34  3904.8 1057.55  3958.8 1055.42    4038 1049.62
  4123.3 1048.94    4197  1044.5  4265.1 1044.16  4346.7 1041.12  4368.9 1039.21
  4401.4 1038.83  4429.7 1040.65  4468.5 1040.93  4779.9 1038.41  4821.4 1038.25
  4843.6 1036.01  4889.3 1037.79  4969.9 1035.52  4987.7 1030.99  4988.2 1030.49
  5006.9 1030.99  5007.2 1032.28    5028 1034.84  5050.1 1039.77  5096.1 1042.66
  5228.1 1047.44  5292.1 1050.05  5360.1  1053.1  5439.7 1055.71  5463.8  1056.5
#Mann= 13 ,-1 , 0
  3585.7     .12       0  3611.5    .035       0  3904.8     .12       0
  4779.9     .12       0  4843.6     .12       0  4969.9     .12       0
  4987.7     .05       0  5006.9     .12       0  5096.1     .12       0
  5228.1     .07       0  5292.1     .12       0  5360.1     .07       0
  5439.7    .035       0
Bank Sta=4987.7,5006.9
XS Rating Curve= 0 ,0
Exp/Cntr=0.3,0.1

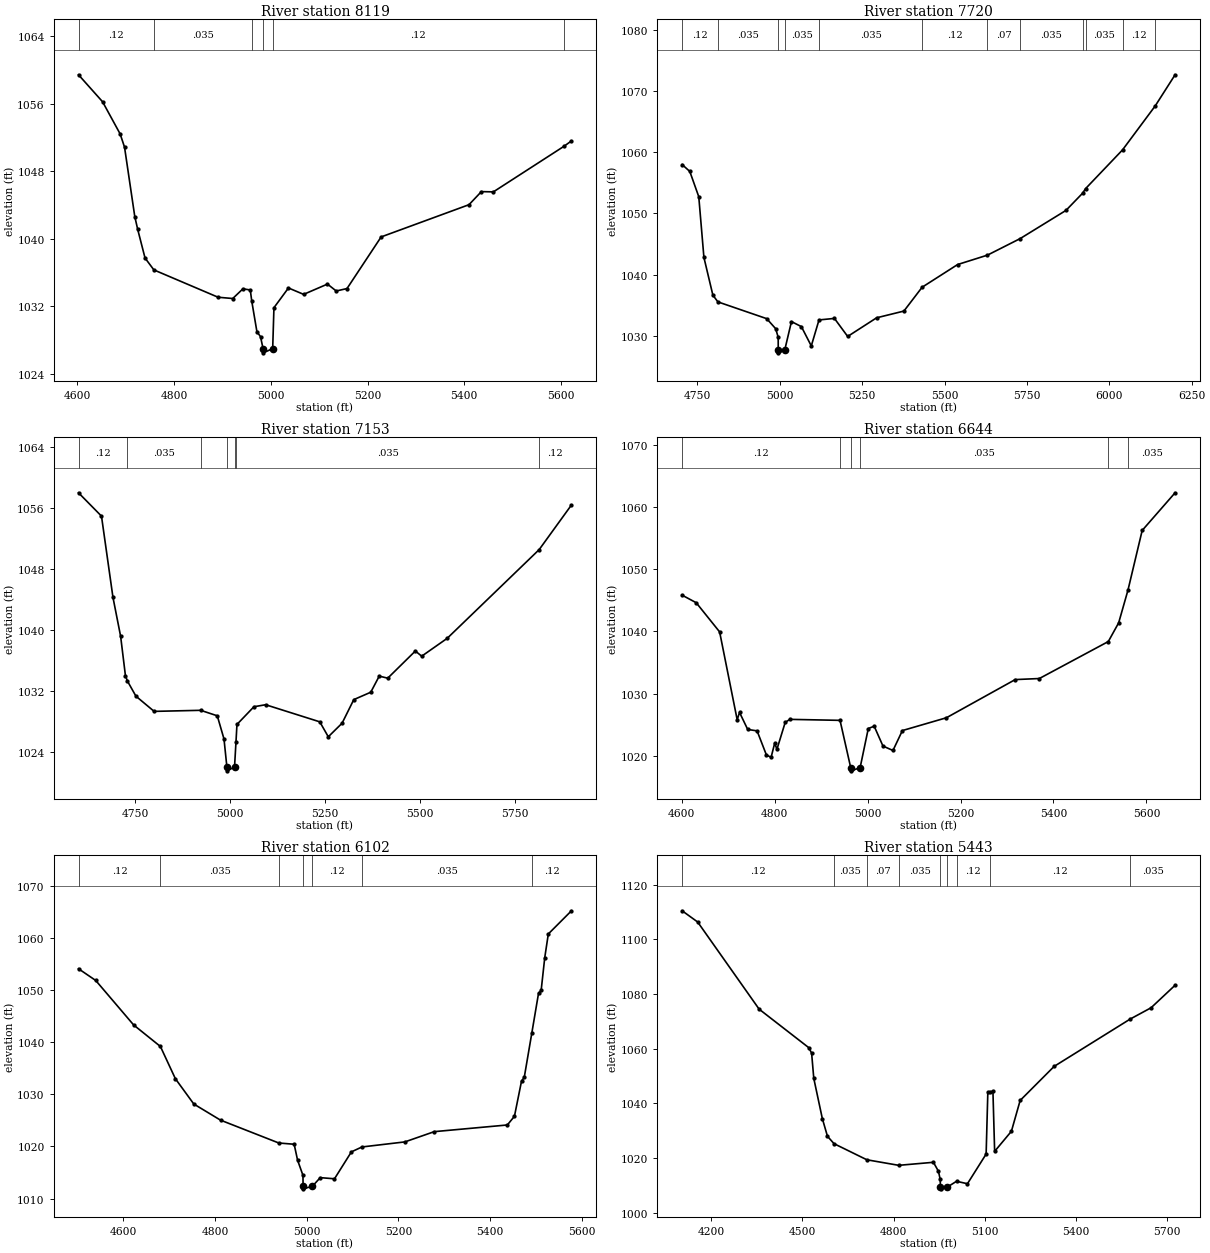
Type RM Length L Ch R = 1 ,8119    ,399,399,399
BEGIN DESCRIPTION:
Spring Branch 14.0
END DESCRIPTION:
XS GIS Cut Line= 3
      2149124.99     13870174.99      2148789.47     13869958.37
      2148174.98       13869875.
#Sta/Elev= 30
  4602.1 1059.44  4651.9 1056.24  4688.2 1052.43  4697.3 1050.86  4718.5 1042.63
  4724.5 1041.12  4739.7 1037.72    4758 1036.31  4890.8 1033.07  4921.1 1032.92
  4942.2 1034.07  4957.4 1033.93  4960.3 1032.65  4971.1 1028.98  4978.5  1028.4
  4983.8 1026.98  4984.3 1026.48  5003.7 1026.98  5006.3 1031.83  5036.3 1034.17
  5067.7 1033.41    5117 1034.63  5135.1 1033.81  5157.4  1034.1    5228 1040.22
  5409.7 1044.04  5435.3 1045.59  5460.1 1045.56  5605.8 1050.95  5621.6  1051.6
#Mann= 6 ,-1 , 0
  4602.1     .12       0    4758    .035       0  4960.3     .12       0
  4983.8     .05       0  5003.7     .12       0  5605.8     .07       0
Bank Sta=4983.8,5003.7
XS Rating Curve= 0 ,0
Exp/Cntr=0.3,0.1

Type RM Length L Ch R = 1 ,7720    ,567,567,567
BEGIN DESCRIPTION:
Spring Branch 13.0
END DESCRIPTION:
XS GIS Cut Line= 3
        2149275.       13869825.        2149025.       13869675.
        2147825.       13869775.
#Sta/Elev= 30
  4703.9 1057.99  4727.2 1056.86  4754.4 1052.73    4770  1042.8  4797.2 1036.63
  4812.5 1035.53  4960.5 1032.79  4987.7 1031.15  4995.4 1029.74  4995.5  1027.7
    4996  1027.2  5015.4  1027.7  5035.6 1032.31  5065.7 1031.49  5095.8 1028.33
  5119.2 1032.58    5166 1032.83  5206.2 1029.88    5294 1032.93  5376.8 1034.03
  5432.1 1037.93  5539.8 1041.64  5630.4 1043.18  5729.5 1045.88  5868.5 1050.49
  5919.1 1053.31  5927.8 1054.04  6040.2 1060.39  6139.1 1067.56  6199.6 1072.67
#Mann= 12 ,-1 , 0
  4703.9     .12       0  4812.5    .035       0  4995.5     .05       0
  5015.4    .035       0  5119.2    .035       0  5432.1     .12       0
  5630.4     .07       0  5729.5    .035       0  5919.1     .12       0
  5927.8    .035       0  6040.2     .12       0  6139.1    .035       0
Bank Sta=4995.5,5015.4
XS Rating Curve= 0 ,0
Exp/Cntr=0.3,0.1

Type RM Length L Ch R = 1 ,7153    ,509,509,509
BEGIN DESCRIPTION:
Spring Branch 12.0
END DESCRIPTION:
XS GIS Cut Line= 3
      2149225.02       13869175.        2148825.       13869225.
      2148024.96     13869625.02
#Sta/Elev= 30
    4601 1057.98  4661.5 1054.92  4691.7 1044.28  4711.9 1039.17  4724.5 1034.03
  4729.5 1033.34  4752.2 1031.33  4800.1 1029.34  4922.6 1029.48  4966.3 1028.76
    4984 1025.72  4991.6 1022.05  4992.1 1021.55  5011.7 1022.05  5015.5  1025.3
  5018.1 1027.63  5062.8 1029.95  5093.6 1030.21  5236.1 1027.97  5258.5 1026.01
  5294.8 1027.79  5325.6 1030.88  5370.3 1031.85  5392.6 1033.96    5415 1033.69
  5487.7 1037.25  5504.4 1036.57  5571.5 1038.91  5813.7 1050.54  5898.6 1056.38
#Mann= 7 ,-1 , 0
    4601     .12       0  4729.5    .035       0  4922.6     .12       0
  4991.6     .05       0  5011.7     .12       0  5015.5    .035       0
  5813.7     .12       0
Bank Sta=4991.6,5011.7
XS Rating Curve= 0 ,0
Exp/Cntr=0.3,0.1

Type RM Length L Ch R = 1 ,6644    ,542,542,542
BEGIN DESCRIPTION:
Spring Branch 11.0
END DESCRIPTION:
XS GIS Cut Line= 3
      2148925.04     13868925.01        2148525.       13868875.
        2147875.       13868975.
#Sta/Elev= 30
  4600.9  1045.8  4631.2 1044.59  4681.6  1039.9  4719.4 1025.78  4724.4 1026.97
    4742 1024.23  4762.2    1024  4782.3 1020.12  4792.4 1019.76    4800    1022
    4805 1021.06  4822.7 1025.36  4832.7 1025.85  4940.7 1025.69  4963.7 1018.08
  4964.2 1017.58  4983.9 1018.08  5001.5 1024.38  5014.2 1024.75  5033.1 1021.56
  5054.6 1020.85  5074.9 1024.05  5169.7 1026.11  5317.7 1032.24  5369.6 1032.41
    5518 1038.35  5540.3 1041.36  5560.3 1046.61  5590.9  1056.2  5661.7 1062.25
#Mann= 6 ,-1 , 0
  4600.9     .12       0  4940.7    .035       0  4963.7    .035       0
  4983.9    .035       0    5518     .12       0  5560.3    .035       0
Bank Sta=4963.7,4983.9
XS Rating Curve= 0 ,0
Exp/Cntr=0.3,0.1

Type RM Length L Ch R = 1 ,6102    ,659,659,659
BEGIN DESCRIPTION:
Spring Branch 10.0
END DESCRIPTION:
XS GIS Cut Line= 3
      2149124.96     13868624.98        2148675.       13868425.
        2148375.     13867924.99
#Sta/Elev= 30
    4502 1054.12  4539.6 1051.87  4622.3 1043.33  4680.7  1039.2  4713.3 1033.02
  4753.6 1028.15  4811.8 1025.06    4939 1020.67  4972.5 1020.43    4980 1017.36
  4991.7 1014.46    4992 1012.37  4992.5 1011.87  5012.4 1012.37  5029.4 1014.02
  5060.5  1013.8  5097.4 1018.97  5120.5 1019.91    5214 1020.88  5278.2 1022.85
  5437.6 1024.13  5453.1  1025.8  5468.6 1032.57  5474.5 1033.26    5491 1041.77
  5505.6 1049.38  5511.4 1049.98  5519.2 1056.24    5527  1060.8  5577.5 1065.25
#Mann= 7 ,-1 , 0
    4502     .12       0  4680.7    .035       0    4939     .12       0
    4992     .05       0  5012.4     .12       0  5120.5    .035       0
    5491     .12       0
Bank Sta=4992,5012.4
XS Rating Curve= 0 ,0
Exp/Cntr=0.3,0.1

Type RM Length L Ch R = 1 ,5443    ,447,447,447
BEGIN DESCRIPTION:
Spring Branch 9.0
END DESCRIPTION:
XS GIS Cut Line= 3
      2149777.58      13868321.7       2148973.5     13867927.12
      2148322.75     13867602.96
#Sta/Elev= 30
  4103.9 1110.43    4155 1106.33  4357.4 1074.44  4520.4 1060.39  4530.1  1058.4
  4537.3 1049.11  4565.4 1034.43  4582.3 1027.95  4603.9 1025.24    4712 1019.35
  4816.9 1017.32  4931.1 1018.43  4947.7 1015.13  4953.4 1012.17  4954.3 1009.22
  4954.8 1008.72  4974.7 1009.22  5007.2 1011.48  5043.1 1010.59  5104.6 1021.44
  5110.2 1043.99  5116.3 1044.13    5127 1044.42  5132.6 1022.43  5187.8 1029.77
  5216.6 1041.05  5328.5 1053.51  5578.8 1070.82  5647.5 1074.95  5726.6 1083.19
#Mann= 9 ,-1 , 0
  4103.9     .12       0  4603.9    .035       0    4712     .07       0
  4816.9    .035       0  4954.3    .035       0  4974.7    .035       0
  5007.2     .12       0  5116.3     .12       0  5578.8    .035       0
Bank Sta=4954.3,4974.7
XS Rating Curve= 0 ,0
Exp/Cntr=0.3,0.1

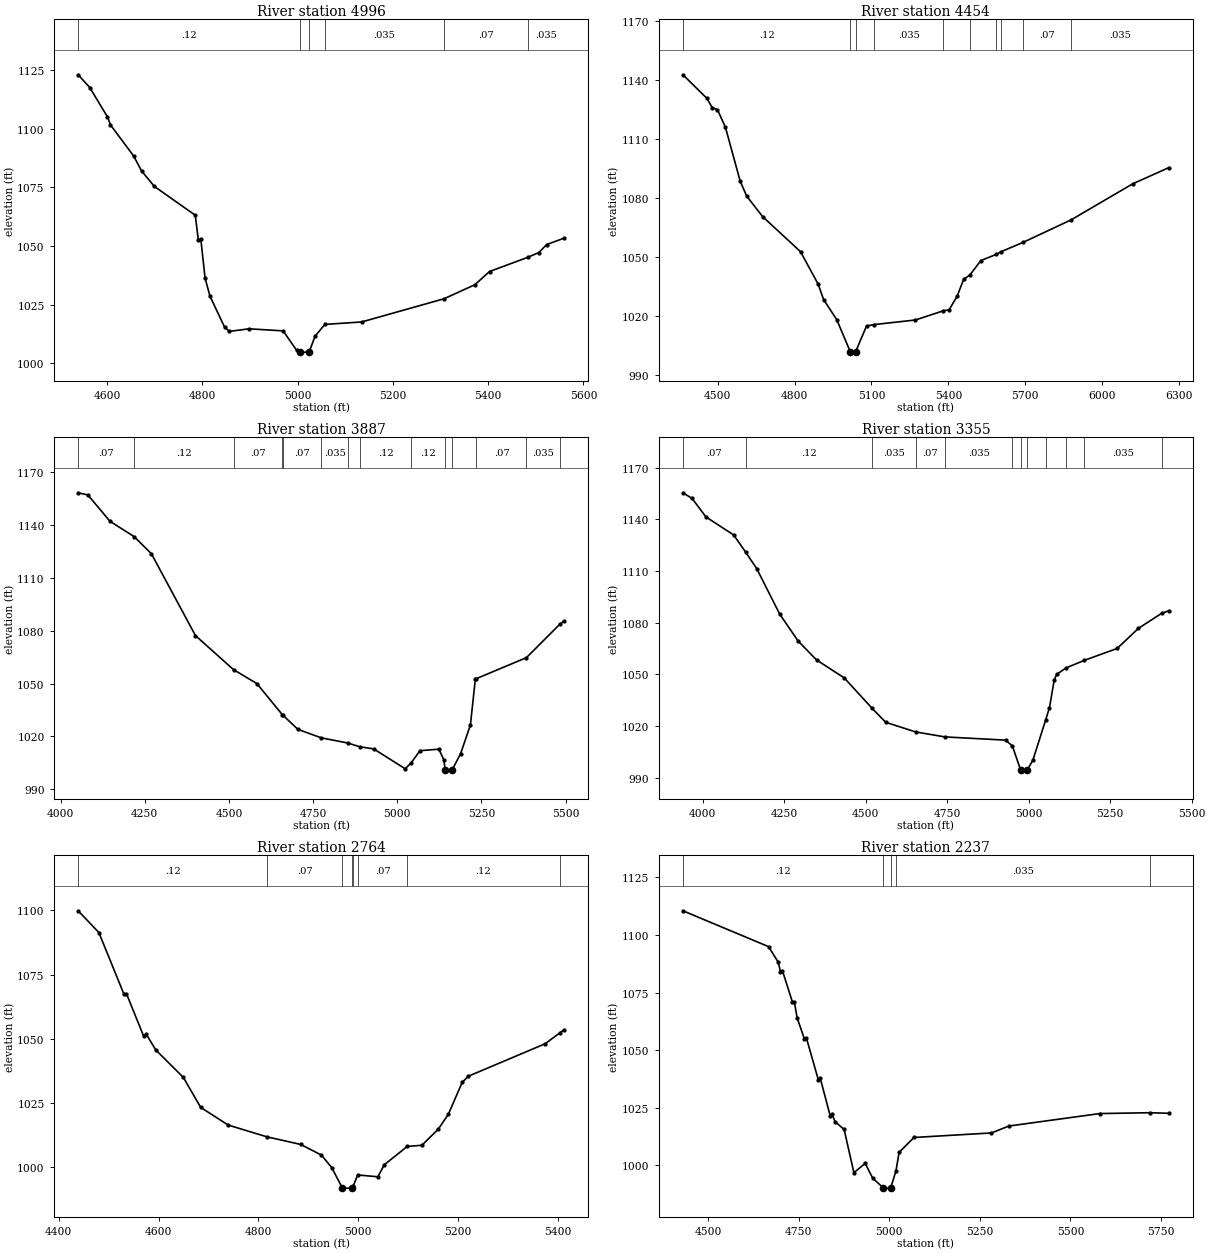
Type RM Length L Ch R = 1 ,4996    ,542,542,542
BEGIN DESCRIPTION:
Spring Branch 8.0
END DESCRIPTION:
XS GIS Cut Line= 3
      2149775.03     13867775.01        2149325.       13867675.
      2148825.03     13867425.01
#Sta/Elev= 30
  4539.2    1123  4563.6 1117.57  4600.7 1105.06  4607.1 1101.64  4655.8 1088.37
  4672.4    1082  4699.3 1075.42  4785.1 1063.15  4791.5 1052.54  4796.6 1053.17
  4805.6  1036.4  4815.8 1028.76  4846.6 1015.46  4856.8 1013.67  4897.8 1014.77
  4969.5 1013.89  4997.7 1005.64  5003.9 1005.03  5004.4 1004.53  5024.4 1005.03
  5036.5 1011.62  5057.1 1016.64  5134.4 1017.69  5307.3 1027.57    5372 1033.55
  5402.7 1039.17  5483.1 1045.23  5506.1 1047.24  5522.9 1050.67  5559.2 1053.39
#Mann= 6 ,-1 , 0
  4539.2     .12       0  5003.9     .05       0  5024.4     .12       0
  5057.1    .035       0  5307.3     .07       0  5483.1    .035       0
Bank Sta=5003.9,5024.4
XS Rating Curve= 0 ,0
Exp/Cntr=0.3,0.1

Type RM Length L Ch R = 1 ,4454    ,567,567,567
BEGIN DESCRIPTION:
Spring Branch 7.0
END DESCRIPTION:
XS GIS Cut Line= 3
      2150135.18     13867387.66        2149525.       13867225.
      2148333.14     13866804.34
#Sta/Elev= 30
  4364.4 1142.56  4457.7 1130.61  4478.4 1125.88  4499.1  1124.8  4530.2 1115.89
  4587.7 1088.47    4613 1080.87  4675.1 1070.43  4823.2 1052.54  4892.4 1035.92
  4913.1 1028.21  4964.8 1017.88  5017.4 1001.58  5017.9 1001.08  5037.9 1001.58
  5080.7 1014.74  5110.1 1015.46  5271.6  1017.8  5380.5 1022.49  5402.8 1022.98
  5433.8 1029.78  5459.4 1038.48  5483.9  1040.7  5526.6 1048.04  5587.3 1051.19
  5603.3 1052.42  5690.7 1057.25  5878.7 1068.74  6118.6 1087.05  6259.8 1095.32
#Mann= 10 ,-1 , 0
  4364.4     .12       0  5017.4     .05       0  5037.9     .12       0
  5110.1    .035       0  5380.5     .07       0  5483.9     .12       0
  5587.3     .07       0  5603.3     .12       0  5690.7     .07       0
  5878.7    .035       0
Bank Sta=5017.4,5037.9
XS Rating Curve= 0 ,0
Exp/Cntr=0.3,0.1

Type RM Length L Ch R = 1 ,3887    ,532,532,532
BEGIN DESCRIPTION:
Spring Branch 6.0
END DESCRIPTION:
XS GIS Cut Line= 3
      2150375.02     13867175.01        2149575.       13866675.
      2149175.02     13866375.01
#Sta/Elev= 30
  4052.2 1158.22  4081.1 1156.99  4146.6 1142.07  4218.7 1133.34  4269.8 1123.64
  4400.7 1077.21  4513.8 1057.89  4582.9 1050.03  4658.4 1032.44  4660.1 1032.12
  4704.9 1024.03  4774.1 1019.24  4853.6 1016.26  4888.1 1014.19  4930.2 1012.93
  5023.7 1001.68  5042.1  1005.2  5067.5 1011.93  5123.7 1012.78  5138.3 1006.83
  5142.6    1001  5143.1  1000.5  5163.2    1001  5188.3 1010.25  5217.5 1026.56
  5232.1 1052.65  5235.5 1052.84  5383.9 1064.71  5484.2 1083.89  5495.6 1085.35
#Mann= 14 ,-1 , 0
  4052.2     .07       0  4218.7     .12       0  4513.8     .07       0
  4658.4     .12       0  4660.1     .07       0  4774.1    .035       0
  4853.6     .07       0  4888.1     .12       0  5042.1     .12       0
  5142.6     .05       0  5163.2     .12       0  5235.5     .07       0
  5383.9    .035       0  5484.2     .12       0
Bank Sta=5142.6,5163.2
XS Rating Curve= 0 ,0
Exp/Cntr=0.3,0.1

Type RM Length L Ch R = 1 ,3355    ,591,591,591
BEGIN DESCRIPTION:
Spring Branch 5.0
END DESCRIPTION:
XS GIS Cut Line= 3
      2150474.99     13866974.99        2149725.       13866225.
      2149374.97     13865974.98
#Sta/Elev= 30
  3939.1 1155.42  3967.4 1152.13  4009.8 1141.39  4094.6 1130.96  4131.8  1120.9
  4165.4 1111.43  4236.1 1084.95  4292.6 1069.34  4349.2 1058.33  4434.1 1047.92
  4519.3 1030.31  4561.3 1022.14  4653.6 1016.52    4743 1013.65    4929 1011.78
  4949.7 1008.45  4975.3  994.45  4975.8  993.95  4995.9  994.45  5013.3 1000.41
  5051.9 1023.44  5063.6 1030.53  5078.4 1046.79  5085.8 1049.95  5114.9 1053.74
  5170.5  1058.1  5271.3    1065  5336.5 1076.65  5407.5 1085.39  5429.9 1086.89
#Mann= 12 ,-1 , 0
  3939.1     .07       0  4131.8     .12       0  4519.3    .035       0
  4653.6     .07       0    4743    .035       0  4949.7     .12       0
  4975.3     .05       0  4995.9     .12       0  5051.9     .12       0
  5114.9     .12       0  5170.5    .035       0  5407.5     .12       0
Bank Sta=4975.3,4995.9
XS Rating Curve= 0 ,0
Exp/Cntr=0.3,0.1

Type RM Length L Ch R = 1 ,2764    ,527,527,527
BEGIN DESCRIPTION:
Spring Branch 4.0
END DESCRIPTION:
XS GIS Cut Line= 3
      2150725.04     13866025.01        2150175.       13865875.
      2149775.04     13865825.01
#Sta/Elev= 30
  4438.9 1099.89  4480.4 1091.39  4530.5 1067.37  4535.7 1067.51  4570.2 1050.85
  4575.4 1051.65  4594.4 1045.54  4649.7 1034.79  4684.3 1023.11  4739.5  1016.2
    4817 1011.61  4884.6 1008.64  4926.1 1004.49  4946.8  999.58  4967.6   991.8
  4968.1   991.3  4988.3   991.8    4990  992.51  4998.8  996.73  5039.3     996
  5051.9 1000.67  5097.9 1007.84  5127.4 1008.32  5160.2 1014.61  5180.4 1020.43
  5208.1  1032.9  5220.7  1035.3  5374.4 1047.97  5403.2 1052.14  5412.1 1053.42
#Mann= 8 ,-1 , 0
  4438.9     .12       0    4817     .07       0  4967.6     .05       0
  4988.3     .07       0    4990    .035       0  4998.8     .07       0
  5097.9     .12       0  5403.2    .035       0
Bank Sta=4967.6,4988.3
XS Rating Curve= 0 ,0
Exp/Cntr=0.3,0.1

Type RM Length L Ch R = 1 ,2237    ,555,555,555
BEGIN DESCRIPTION:
Spring Branch 3.0
END DESCRIPTION:
XS GIS Cut Line= 3
       2151017.2     13865637.68        2150475.       13865475.
      2149719.24     13865301.02
#Sta/Elev= 30
    4430 1110.53  4666.4 1094.97  4693.3 1088.18  4699.4 1084.03  4704.6  1084.6
  4732.5 1070.86  4737.7 1070.84  4745.5 1064.01  4765.5 1054.86  4770.8 1055.39
  4803.8 1037.19    4809    1038  4836.9 1021.34  4842.1 1022.12  4849.9 1018.98
  4875.1  1015.6  4902.1  996.84  4933.4 1000.87  4954.3  994.35  4983.1  990.31
  4983.6  989.81  5003.8  990.31  5018.3  997.62  5026.9 1005.64    5068 1012.11
    5282 1014.08    5330 1017.08    5581 1022.49  5719.5 1022.86  5771.6 1022.61
#Mann= 5 ,-1 , 0
    4430     .12       0  4983.1     .05       0  5003.8     .12       0
  5018.3    .035       0  5719.5     .12       0
Bank Sta=4983.1,5003.8
XS Rating Curve= 0 ,0
Exp/Cntr=0.3,0.1

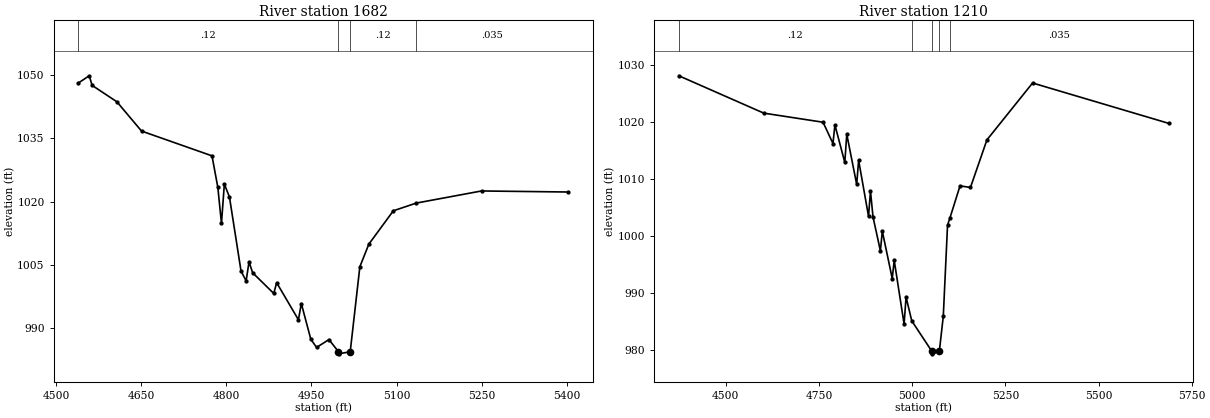
Type RM Length L Ch R = 1 ,1682    ,472,472,472
BEGIN DESCRIPTION:
Spring Branch 2.0
END DESCRIPTION:
XS GIS Cut Line= 3
      2150725.02       13865125.        2150275.       13865025.
      2149925.01       13865225.
#Sta/Elev= 30
    4539  1048.1  4558.2 1049.81  4563.3 1047.53  4606.9 1043.65  4650.4 1036.71
  4774.6 1030.84  4784.9 1023.37  4791.3 1014.83  4796.4 1024.15  4805.4 1021.08
  4825.8 1003.53  4834.8 1001.22  4839.9 1005.72  4846.3 1003.13  4883.5  998.24
  4888.6 1000.79    4927     992  4932.1  995.85  4948.8   987.4    4959  985.45
  4980.8  987.31  4997.6  984.43  4998.1  983.93  5018.3  984.43  5035.3 1004.57
  5051.1 1009.91  5094.3 1017.82  5134.8 1019.65  5249.8 1022.52  5403.1 1022.27
#Mann= 4 ,-1 , 0
    4539     .12       0  4997.6     .05       0  5018.3     .12       0
  5134.8    .035       0
Bank Sta=4997.6,5018.3
XS Rating Curve= 0 ,0
Exp/Cntr=0.3,0.1

Type RM Length L Ch R = 1 ,1210    ,860,860,860
BEGIN DESCRIPTION:
Spring Branch 1.0
END DESCRIPTION:
XS GIS Cut Line= 3
      2150499.99       13864950.      2149905.16     13864754.62
      2149243.58      13864947.4
#Sta/Elev= 30
  4373.9 1028.14  4601.8 1021.57  4760.9 1019.97  4787.4 1016.23  4792.7 1019.49
  4819.2  1012.9  4824.5 1017.86  4851.1 1009.04  4856.3 1013.28  4882.9 1003.42
  4888.1 1007.88  4894.9 1003.32  4914.7  997.36  4919.9  1000.8  4946.5  992.48
  4951.8  995.67  4978.3  984.48  4983.6  989.22  4998.9  985.04  5052.3  979.74
  5052.8  979.24    5073  979.74  5083.5  985.85  5094.9 1001.86    5101 1003.07
  5128.4 1008.78  5156.4  1008.5  5200.6 1016.87  5323.1 1026.87  5689.1 1019.76
#Mann= 5 ,-1 , 0
  4373.9     .12       0  4998.9     .12       0  5052.3     .05       0
    5073     .12       0    5101    .035       0
Bank Sta=5052.3,5073
XS Rating Curve= 0 ,0
Exp/Cntr=0.3,0.1