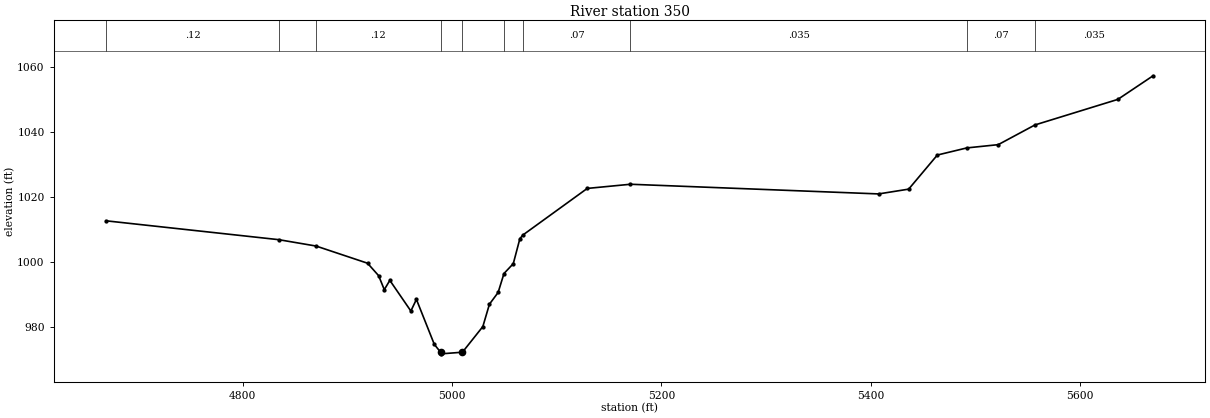
HEC-RAS study Spring Branch.prj: Spring Branch Base Level Engineering

--- Spring Branch.g01 (geometry) --- (continued)

Type RM Length L Ch R = 1 ,350     ,0,0,0
BEGIN DESCRIPTION:
Spring Branch 0.0
END DESCRIPTION:
XS GIS Cut Line= 3
      2149600.04     13864350.01      2149288.97     13864238.07
      2148882.49     13864770.69
#Sta/Elev= 30
  4669.4 1012.57  4834.3 1006.78    4870 1004.82  4919.2  999.54  4929.8  995.71
  4935.2  991.41  4940.5  994.27  4960.6  984.85  4965.9  988.43    4983  974.61
    4989  972.19  4989.5  971.69  5009.9  972.19  5029.4  980.07  5035.7  986.95
    5044  990.55  5049.6  996.38  5058.5  999.41  5064.8 1007.09  5067.8 1008.24
  5129.2 1022.53  5170.5 1023.81  5407.7 1020.84  5436.4 1022.31  5463.8 1032.79
    5492 1034.98    5522 1035.98  5557.1 1042.04  5636.3 1049.89    5670 1057.15
#Mann= 10 ,-1 , 0
  4669.4     .12       0  4834.3     .12       0    4870     .12       0
    4989     .05       0  5009.9     .12       0  5049.6     .12       0
  5067.8     .07       0  5170.5    .035       0    5492     .07       0
  5557.1    .035       0
Bank Sta=4989,5009.9
XS Rating Curve= 0 ,0
Exp/Cntr=0.3,0.1

Chan Stop Cuts=-1
Use User Specified Reach Order=0
Composite Channel Slope=5