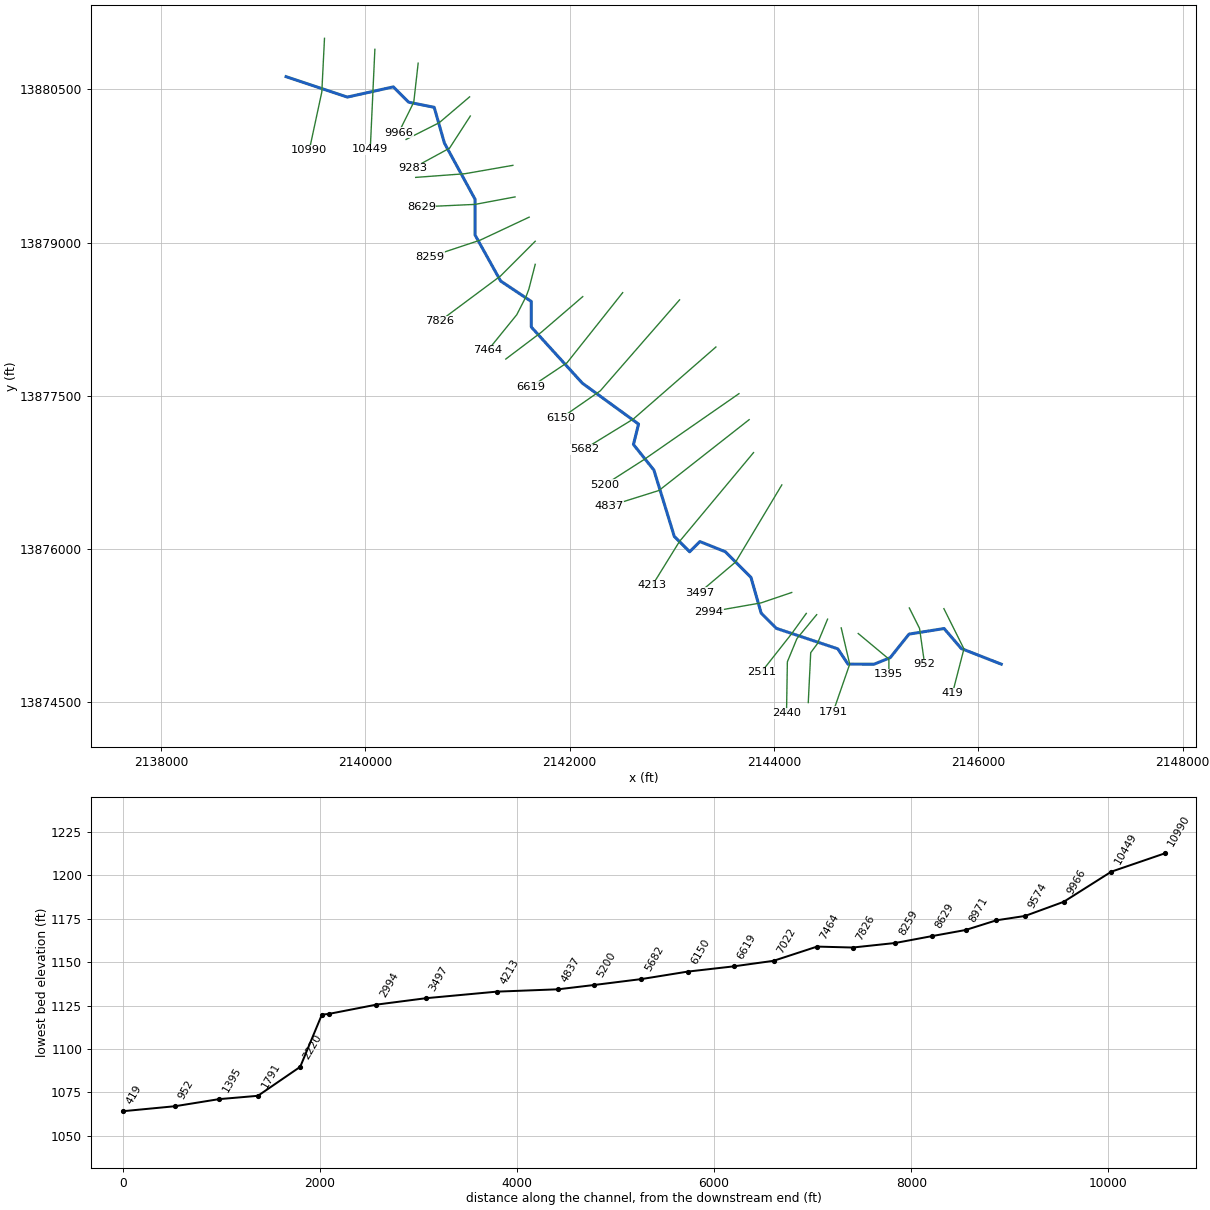
--- Spring Tributary 3.prj (project) ---

Proj Title=Spring Tributary 3 Base Level Engineering
Current Plan=p01
Default Exp/Contr=0.3,0.1
English Units
Geom File=g01
Flow File=f01
Plan File=p01
BEGIN DESCRIPTION:
Spring Tributary 3
END DESCRIPTION:

--- Spring Tributary 3.p01 (plan) ---

Plan Title=Multiple Run
Short Identifier=Multiple
Geom File=g01
Flow File=f01
Subcritical Flow
K Sum by GR= 0
Std Step Tol= 0.01
Critical Tol= 0.01
Num of Std Step Trials= 20
Max Error Tol= 0.3
Flow Tol Ratio= 0.001
Split Flow NTrial= 30
Split Flow Tol= 0.02
Split Flow Ratio= 0.02
Log Output Level= 0
Friction Slope Method= 1
Unsteady Friction Slope Method= 2
Unsteady Bridges Friction Slope Method= 1
Parabolic Critical Depth
Global Vel Dist=  1 , 1 , 1
Global Log Level= 0
CheckData=True
Encroach Param= -1, 0, 0, 0
BEGIN DESCRIPTION:
Multiple Run
END DESCRIPTION:

--- Spring Tributary 3.f01 (steady flow) ---

Flow Title=Multiple
Number of Profiles=7
Profile Names=10-year,25-year,50-year,1pct_min,100-year,1pct_plu,500-year
River Rch & RM= Spring Tributary,Reach-1,10990
     319     495     649     414     826    1647    1317
River Rch & RM= Spring Tributary,Reach-1,8971
    1135    1911    2645    1771    3534    7052    6246
Boundary for River Rch & Prof#=Spring Tributary,Reach-1,1
Up Type=0
Dn Type=3
Dn Slope=0.005
Boundary for River Rch & Prof#=Spring Tributary,Reach-1,2
Up Type=0
Dn Type=3
Dn Slope=0.005
Boundary for River Rch & Prof#=Spring Tributary,Reach-1,3
Up Type=0
Dn Type=3
Dn Slope=0.005
Boundary for River Rch & Prof#=Spring Tributary,Reach-1,4
Up Type=0
Dn Type=3
Dn Slope=0.005
Boundary for River Rch & Prof#=Spring Tributary,Reach-1,5
Up Type=0
Dn Type=3
Dn Slope=0.005
Boundary for River Rch & Prof#=Spring Tributary,Reach-1,6
Up Type=0
Dn Type=3
Dn Slope=0.005
Boundary for River Rch & Prof#=Spring Tributary,Reach-1,7
Up Type=0
Dn Type=3
Dn Slope=0.005

--- Spring Tributary 3.g01 (geometry) ---

Geom Title=Existing Conditions

River Reach=Spring Tributary,Reach-1
Reach XY= 30
      2139225.00     13880625.00      2139825.00     13880425.00
      2140275.00     13880525.00      2140425.00     13880375.00
      2140675.00     13880325.00      2140775.00     13879975.00
      2141075.00     13879425.00      2141075.00     13879075.00
      2141325.00     13878625.00      2141625.00     13878425.00
      2141625.00     13878175.00      2142125.00     13877625.00
      2142675.00     13877225.00      2142625.00     13877025.00
      2142825.00     13876775.00      2143025.00     13876125.00
      2143175.00     13875975.00      2143275.00     13876075.00
      2143525.00     13875975.00      2143775.00     13875725.00
      2143875.00     13875375.00      2144025.00     13875225.00
      2144625.00     13875025.00      2144725.00     13874875.00
      2144979.73     13874874.56      2145138.22     13874938.62
      2145322.45     13875169.27      2145665.41     13875223.80
      2145833.34     13875028.17      2146225.00     13874875.00

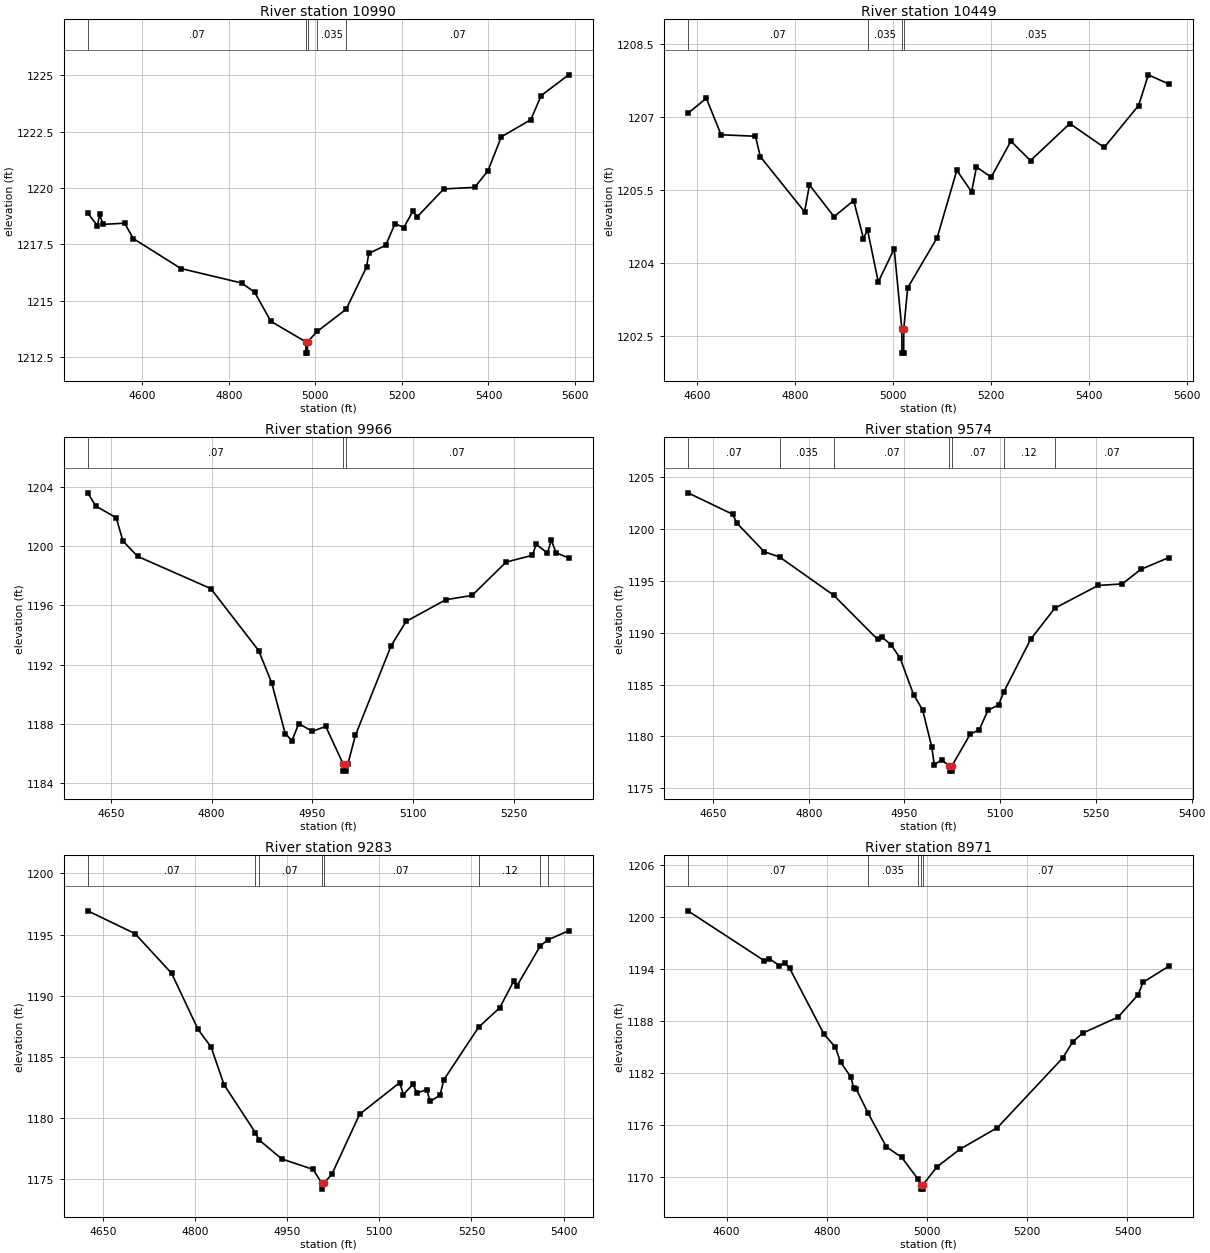
Type RM Length L Ch R = 1,10990,541,541,541
BEGIN DESCRIPTION:
Spring Tributary 3 22.0
END DESCRIPTION:
XS GIS Cut Line= 3
      2139601.24     13881000.14      2139575.00     13880475.00
      2139451.94     13879902.89
#Sta/Elev= 30
  4474.2 1218.89  4496.7 1218.33  4501.8 1218.84  4509.4 1218.39  4559.5 1218.44
  4579.5 1217.76  4689.6 1216.43  4829.8 1215.79  4859.8 1215.38  4897.3 1214.09
  4978.0 1213.18  4978.2 1212.68  4981.7 1212.68  4982.0 1213.18  5004.3 1213.64
  5071.4 1214.63  5118.3 1216.50  5123.4 1217.10  5162.5 1217.46  5184.1 1218.42
  5204.6 1218.25  5225.0 1218.97  5235.3 1218.72  5296.6 1219.96  5368.2 1220.03
  5398.9 1220.77  5429.6 1222.27  5497.7 1223.03  5521.7 1224.10  5585.2 1225.02
#Mann=5,-1,0
  4474.2    0.07       0  4978.0    0.05       0  4982.0    0.07       0
  5004.3   0.035       0  5071.4    0.07       0
Bank Sta=4978,4982
Exp/Cntr=0.3,0.1

Type RM Length L Ch R = 1,10449,483,483,483
BEGIN DESCRIPTION:
Spring Tributary 3 23.0
END DESCRIPTION:
XS GIS Cut Line= 3
      2140094.30     13880892.45      2140075.00     13880475.00
      2140049.16     13879913.29
#Sta/Elev= 30
  4582.1 1207.07  4619.6 1207.38  4649.6 1206.63  4719.7 1206.60  4729.7 1206.18
  4819.8 1205.05  4829.8 1205.60  4879.9 1204.95  4919.9 1205.28  4939.9 1204.50
  4948.1 1204.68  4970.0 1203.61  5002.5 1204.29  5018.0 1202.65  5018.3 1202.15
  5021.8 1202.15  5022.0 1202.65  5030.0 1203.49  5090.1 1204.52  5130.1 1205.90
  5160.2 1205.46  5170.2 1205.97  5200.2 1205.76  5240.3 1206.50  5280.3 1206.10
  5360.4 1206.86  5430.5 1206.37  5500.5 1207.23  5520.5 1207.86  5562.3 1207.67
#Mann=4,-1,0
  4582.1    0.07       0  4948.1   0.035       0  5018.0   0.035       0
  5022.0   0.035       0
Bank Sta=5018,5022
Exp/Cntr=0.3,0.1

Type RM Length L Ch R = 1,9966,392,392,392
BEGIN DESCRIPTION:
Spring Tributary 3 21.0
END DESCRIPTION:
XS GIS Cut Line= 3
      2140517.91     13880757.10      2140475.00     13880375.00
      2140327.78     13880078.21
#Sta/Elev= 30
  4615.5 1203.60  4627.7 1202.70  4657.9 1201.92  4667.9 1200.35  4689.7 1199.31
  4798.7 1197.13  4869.9 1192.94  4889.3 1190.77  4909.4 1187.34  4919.5 1186.86
  4929.6 1188.01  4949.7 1187.49  4969.8 1187.82  4995.5 1185.30  4995.7 1184.80
  4999.2 1184.80  4999.5 1185.30  5002.8 1185.30  5014.0 1187.23  5067.0 1193.26
  5089.3 1194.91  5148.5 1196.38  5187.7 1196.67  5238.1 1198.92  5277.4 1199.38
  5283.0 1200.12  5299.8 1199.53  5305.4 1200.40  5312.6 1199.55  5331.3 1199.20
#Mann=3,-1,0
  4615.5    0.07       0  4995.5    0.05       0  4999.5    0.07       0
Bank Sta=4995.5,4999.5
Exp/Cntr=0.3,0.1

Type RM Length L Ch R = 1,9574,291,291,291
BEGIN DESCRIPTION:
Spring Tributary 3 20.0
END DESCRIPTION:
XS GIS Cut Line= 3
      2141021.41     13880427.22      2140725.00     13880175.00
      2140399.92     13880010.56
#Sta/Elev= 30
  4610.8 1203.48  4681.0 1201.41  4687.6 1200.55  4730.4 1197.80  4754.5 1197.29
  4839.1 1193.61  4908.1 1189.34  4914.9 1189.56  4929.2 1188.83  4943.5 1187.51
  4964.3 1184.02  4978.6 1182.54  4992.9 1178.94  4996.7 1177.28  5008.3 1177.72
  5020.4 1177.15  5020.7 1176.65  5024.2 1176.65  5024.4 1177.15  5052.9 1180.20
  5067.2 1180.64  5080.8 1182.50  5097.5 1183.05  5105.8 1184.30  5147.6 1189.35
  5185.6 1192.36  5253.5 1194.55  5291.4 1194.70  5320.3 1196.10  5364.3 1197.24
#Mann=7,-1,0
  4610.8    0.07       0  4754.5   0.035       0  4839.1    0.07       0
  5020.4    0.05       0  5024.4    0.07       0  5105.8    0.12       0
  5185.6    0.07       0
Bank Sta=5020.4,5024.4
Exp/Cntr=0.3,0.1

Type RM Length L Ch R = 1,9283,312,312,312
BEGIN DESCRIPTION:
Spring Tributary 3 19.0
END DESCRIPTION:
XS GIS Cut Line= 3
      2141028.35     13880239.72      2140825.00     13879925.00
      2140466.48     13879729.63
#Sta/Elev= 30
  4625.3 1196.94  4702.4 1195.07  4761.9 1191.82  4805.0 1187.22  4826.2 1185.78
  4847.3 1182.69  4898.2 1178.77  4904.1 1178.18  4941.0 1176.62  4992.4 1175.75
  5006.1 1174.64  5006.3 1174.14  5010.1 1174.64  5022.8 1175.36  5067.9 1180.27
  5133.4 1182.87  5139.1 1181.89  5155.2 1182.74  5160.9 1182.00  5177.1 1182.30
  5182.8 1181.33  5198.9 1181.83  5205.0 1183.09  5261.6 1187.40  5296.1 1189.00
  5318.6 1191.16  5324.2 1190.80  5362.2 1194.07  5374.5 1194.56  5408.3 1195.31
#Mann=8,-1,0
  4625.3    0.07       0  4898.2    0.12       0  4904.1    0.07       0
  5006.1    0.05       0  5010.1    0.07       0  5261.6    0.12       0
  5362.2    0.07       0  5374.5    0.12       0
Bank Sta=5006.1,5010.1
Exp/Cntr=0.3,0.1

Type RM Length L Ch R = 1,8971,342,342,342
BEGIN DESCRIPTION:
Spring Tributary 3 18.0
END DESCRIPTION:
XS GIS Cut Line= 3
      2141444.99     13879757.05      2140975.00     13879675.00
      2140493.64     13879639.00
#Sta/Elev= 30
  4522.9 1200.67  4675.1 1194.92  4685.3 1195.16  4705.6 1194.33  4715.8 1194.66
  4725.9 1194.04  4794.2 1186.46  4817.3 1184.93  4827.4 1183.22  4847.7 1181.53
  4853.7 1180.27  4858.8 1180.10  4882.1 1177.37  4918.8 1173.44  4949.2 1172.24
  4981.6 1169.76  4987.8 1169.06  4988.1 1168.56  4991.6 1168.56  4991.8 1169.06
  5020.1 1171.14  5066.1 1173.18  5140.4 1175.65  5270.8 1183.69  5290.8 1185.56
  5310.9 1186.57  5381.1 1188.40  5421.2 1190.98  5431.2 1192.42  5482.7 1194.29
#Mann=5,-1,0
  4522.9    0.07       0  4882.1   0.035       0  4981.6    0.07       0
  4987.8    0.05       0  4991.8    0.07       0
Bank Sta=4987.8,4991.8
Exp/Cntr=0.3,0.1

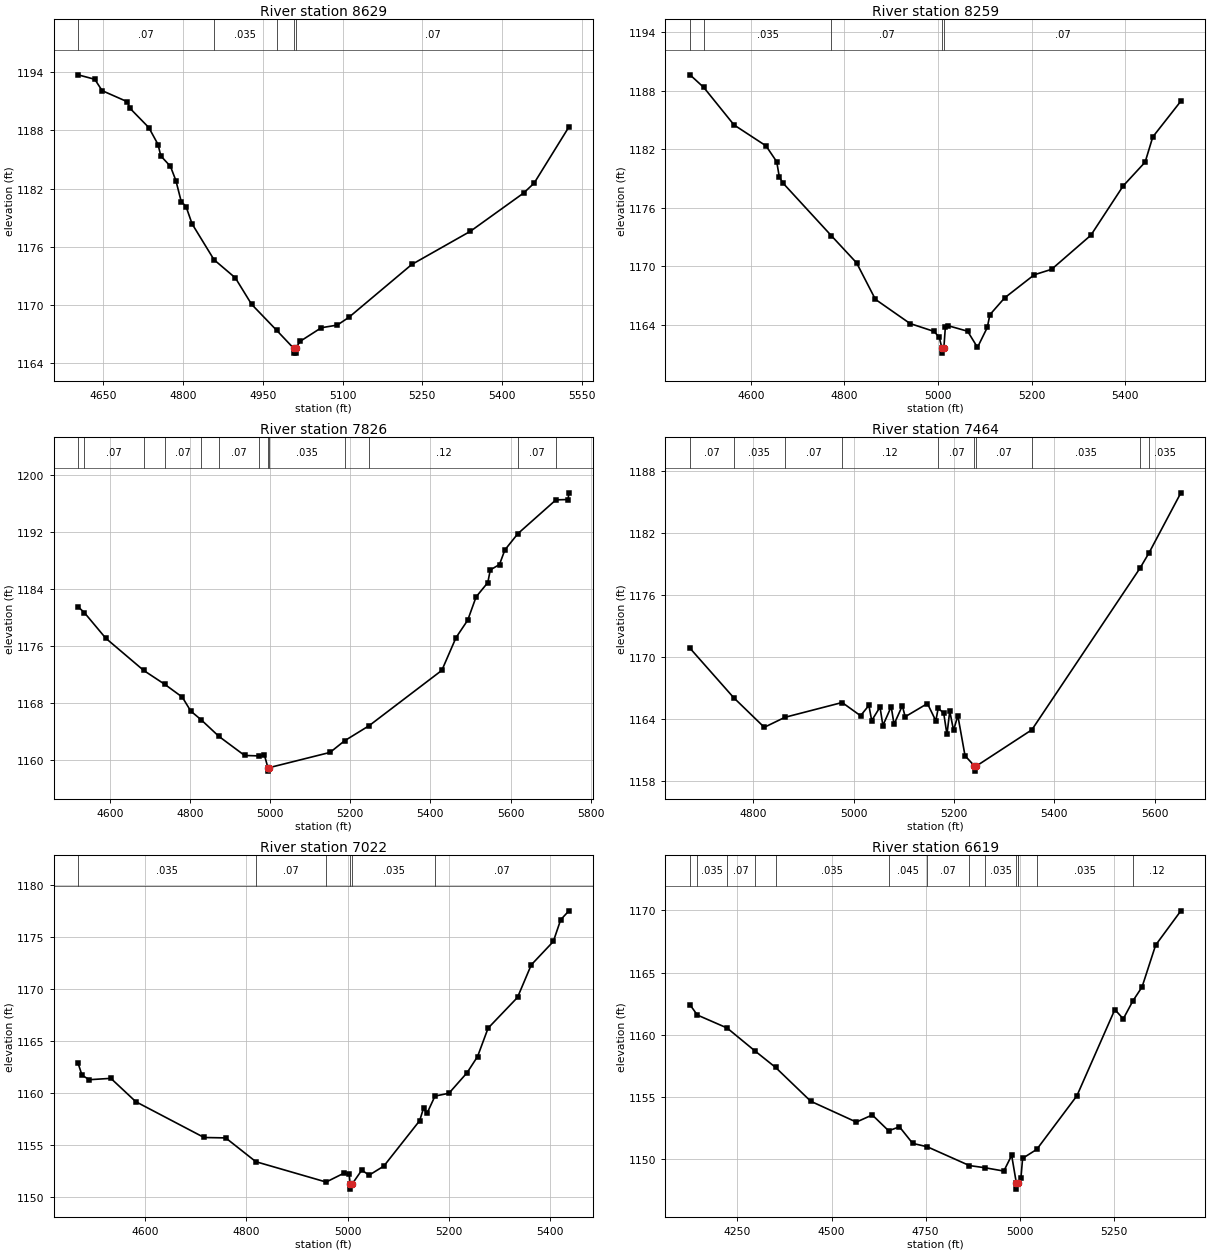
Type RM Length L Ch R = 1,8629,370,370,370
BEGIN DESCRIPTION:
Spring Tributary 3 17.0
END DESCRIPTION:
XS GIS Cut Line= 3
      2141465.84     13879448.03      2141075.00     13879375.00
      2140549.56     13879350.82
#Sta/Elev= 30
  4602.4 1193.73  4633.8 1193.27  4647.6 1192.10  4694.8 1190.96  4700.2 1190.27
  4735.5 1188.29  4752.9 1186.54  4758.0 1185.37  4776.2 1184.29  4786.4 1182.83
  4796.5 1180.66  4805.5 1180.15  4816.9 1178.36  4858.2 1174.66  4898.3 1172.79
  4928.8 1170.07  4975.9 1167.39  5008.0 1165.53  5008.3 1165.03  5011.8 1165.03
  5012.0 1165.53  5020.0 1166.24  5060.1 1167.65  5090.1 1167.92  5111.9 1168.72
  5230.2 1174.17  5340.4 1177.59  5440.5 1181.53  5460.5 1182.56  5526.0 1188.36
#Mann=5,-1,0
  4602.4    0.07       0  4858.2   0.035       0  4975.9    0.07       0
  5008.0    0.05       0  5012.0    0.07       0
Bank Sta=5008,5012
Exp/Cntr=0.3,0.1

Type RM Length L Ch R = 1,8259,433,433,433
BEGIN DESCRIPTION:
Spring Tributary 3 16.0
END DESCRIPTION:
XS GIS Cut Line= 3
      2141604.71     13879250.11      2141125.00     13879025.00
      2140632.52     13878861.23
#Sta/Elev= 30
  4470.1 1189.65  4499.6 1188.35  4564.1 1184.51  4632.5 1182.36  4655.4 1180.73
  4660.9 1179.17  4668.6 1178.55  4771.9 1173.15  4826.1 1170.35  4866.2 1166.61
  4940.2 1164.13  4991.4 1163.32  5002.6 1162.73  5008.5 1161.59  5008.8 1161.09
  5012.5 1161.59  5015.8 1163.82  5021.1 1163.91  5063.2 1163.34  5084.4 1161.68
  5105.4 1163.73  5110.8 1165.03  5142.4 1166.76  5205.7 1169.13  5242.7 1169.69
  5326.7 1173.19  5395.7 1178.25  5442.6 1180.69  5459.0 1183.28  5519.0 1186.95
#Mann=5,-1,0
  4470.1    0.07       0  4499.6   0.035       0  4771.9    0.07       0
  5008.5    0.05       0  5012.5    0.07       0
Bank Sta=5008.5,5012.5
Exp/Cntr=0.3,0.1

Type RM Length L Ch R = 1,7826,362,362,362
BEGIN DESCRIPTION:
Spring Tributary 3 15.0
END DESCRIPTION:
XS GIS Cut Line= 3
      2141663.72     13879013.97      2141325.00     13878675.00
      2140726.76     13878229.66
#Sta/Elev= 30
  4520.8 1181.55  4536.4 1180.73  4589.9 1177.13  4684.7 1172.60  4737.0 1170.66
  4780.8 1168.86  4802.0 1166.90  4828.2 1165.66  4872.3 1163.34  4936.4 1160.66
  4971.6 1160.60  4985.9 1160.69  4994.5 1158.96  4994.7 1158.46  4998.5 1158.96
  5149.6 1161.09  5185.8 1162.72  5247.0 1164.84  5428.6 1172.62  5464.0 1177.22
  5493.2 1179.67  5514.1 1182.94  5543.3 1184.95  5549.5 1186.73  5572.5 1187.49
  5585.9 1189.54  5618.3 1191.82  5713.3 1196.57  5743.5 1196.62  5745.8 1197.56
#Mann=13,-1,0
  4520.8   0.035       0  4536.4    0.07       0  4684.7   0.035       0
  4737.0    0.07       0  4828.2   0.035       0  4872.3    0.07       0
  4971.6   0.035       0  4994.5    0.05       0  4998.5   0.035       0
  5185.8   0.035       0  5247.0    0.12       0  5618.3    0.07       0
  5713.3    0.12       0
Bank Sta=4994.5,4998.5
Exp/Cntr=0.3,0.1

Type RM Length L Ch R = 1,7464,442,442,442
BEGIN DESCRIPTION:
Spring Tributary 3 14.0
END DESCRIPTION:
XS GIS Cut Line= 5
      2141663.75     13878788.35      2141601.24     13878545.25
      2141575.00     13878475.00      2141483.19     13878295.25
      2141199.26     13877945.54
#Sta/Elev= 30
  4674.0 1170.89  4761.0 1166.11  4822.0 1163.24  4863.3 1164.21  4977.2 1165.64
  5013.9 1164.36  5030.5 1165.36  5036.1 1163.89  5052.7 1165.20  5058.4 1163.41
  5075.0 1165.24  5080.6 1163.53  5097.2 1165.33  5102.8 1164.26  5147.2 1165.54
  5163.9 1163.87  5168.7 1165.10  5179.7 1164.59  5186.1 1162.55  5191.7 1164.81
  5199.2 1162.95  5207.8 1164.37  5222.1 1160.49  5240.9 1159.50  5241.2 1159.00
  5244.9 1159.50  5355.3 1163.00  5571.0 1178.65  5588.7 1180.11  5652.3 1185.93
#Mann=10,-1,0
  4674.0    0.07       0  4761.0   0.035       0  4863.3    0.07       0
  4977.2    0.12       0  5168.7    0.07       0  5240.9    0.05       0
  5244.9    0.07       0  5355.3   0.035       0  5571.0    0.07       0
  5588.7   0.035       0
Bank Sta=5240.9,5244.9
Exp/Cntr=0.3,0.1

Type RM Length L Ch R = 1,7022,403,403,403
BEGIN DESCRIPTION:
Spring Tributary 3 13.0
END DESCRIPTION:
XS GIS Cut Line= 3
      2142129.02     13878472.33      2141725.00     13878125.00
      2141375.57     13877861.24
#Sta/Elev= 30
  4467.2 1162.87  4474.9 1161.73  4489.2 1161.29  4532.0 1161.42  4581.4 1159.18
  4716.3 1155.75  4759.1 1155.71  4818.7 1153.43  4957.7 1151.48  4992.9 1152.33
  5003.1 1152.22  5005.3 1151.30  5005.5 1150.80  5009.3 1151.30  5028.1 1152.62
  5042.7 1152.14  5071.8 1153.01  5142.6 1157.36  5150.3 1158.56  5157.1 1158.06
  5172.9 1159.72  5200.5 1159.99  5236.2 1161.95  5257.1 1163.51  5277.9 1166.23
  5336.1 1169.18  5363.3 1172.30  5406.9 1174.54  5421.5 1176.63  5437.8 1177.48
#Mann=6,-1,0
  4467.2   0.035       0  4818.7    0.07       0  4957.7   0.035       0
  5005.3   0.035       0  5009.3   0.035       0  5172.9    0.07       0
Bank Sta=5005.3,5009.3
Exp/Cntr=0.3,0.1

Type RM Length L Ch R = 1,6619,469,469,469
BEGIN DESCRIPTION:
Spring Tributary 3 12.0
END DESCRIPTION:
XS GIS Cut Line= 3
      2142519.57     13878510.91      2141975.00     13877825.00
      2141619.27     13877587.36
#Sta/Elev= 30
  4124.2 1162.41  4143.6 1161.59  4222.6 1160.55  4296.2 1158.72  4351.3 1157.39
  4444.9 1154.67  4565.9 1153.00  4608.3 1153.57  4651.7 1152.30  4680.4 1152.62
  4715.6 1151.29  4754.1 1151.02  4866.2 1149.51  4906.7 1149.34  4957.6 1149.07
  4978.4 1150.33  4990.8 1148.12  4991.0 1147.62  4994.8 1148.12  4994.9 1148.14
  5003.0 1148.50  5007.5 1150.09  5045.1 1150.81  5151.7 1155.11  5252.5 1162.03
  5274.8 1161.28  5300.5 1162.73  5324.7 1163.84  5360.8 1167.20  5427.8 1169.95
#Mann=14,-1,0
  4124.2    0.07       0  4143.6   0.035       0  4222.6    0.07       0
  4296.2    0.12       0  4351.3   0.035       0  4651.7   0.045       0
  4754.1    0.07       0  4866.2   0.045       0  4906.7   0.035       0
  4990.8    0.05       0  4994.8   0.035       0  4994.9    0.07       0
  5045.1   0.035       0  5300.5    0.12       0
Bank Sta=4990.8,4994.8
Exp/Cntr=0.3,0.1

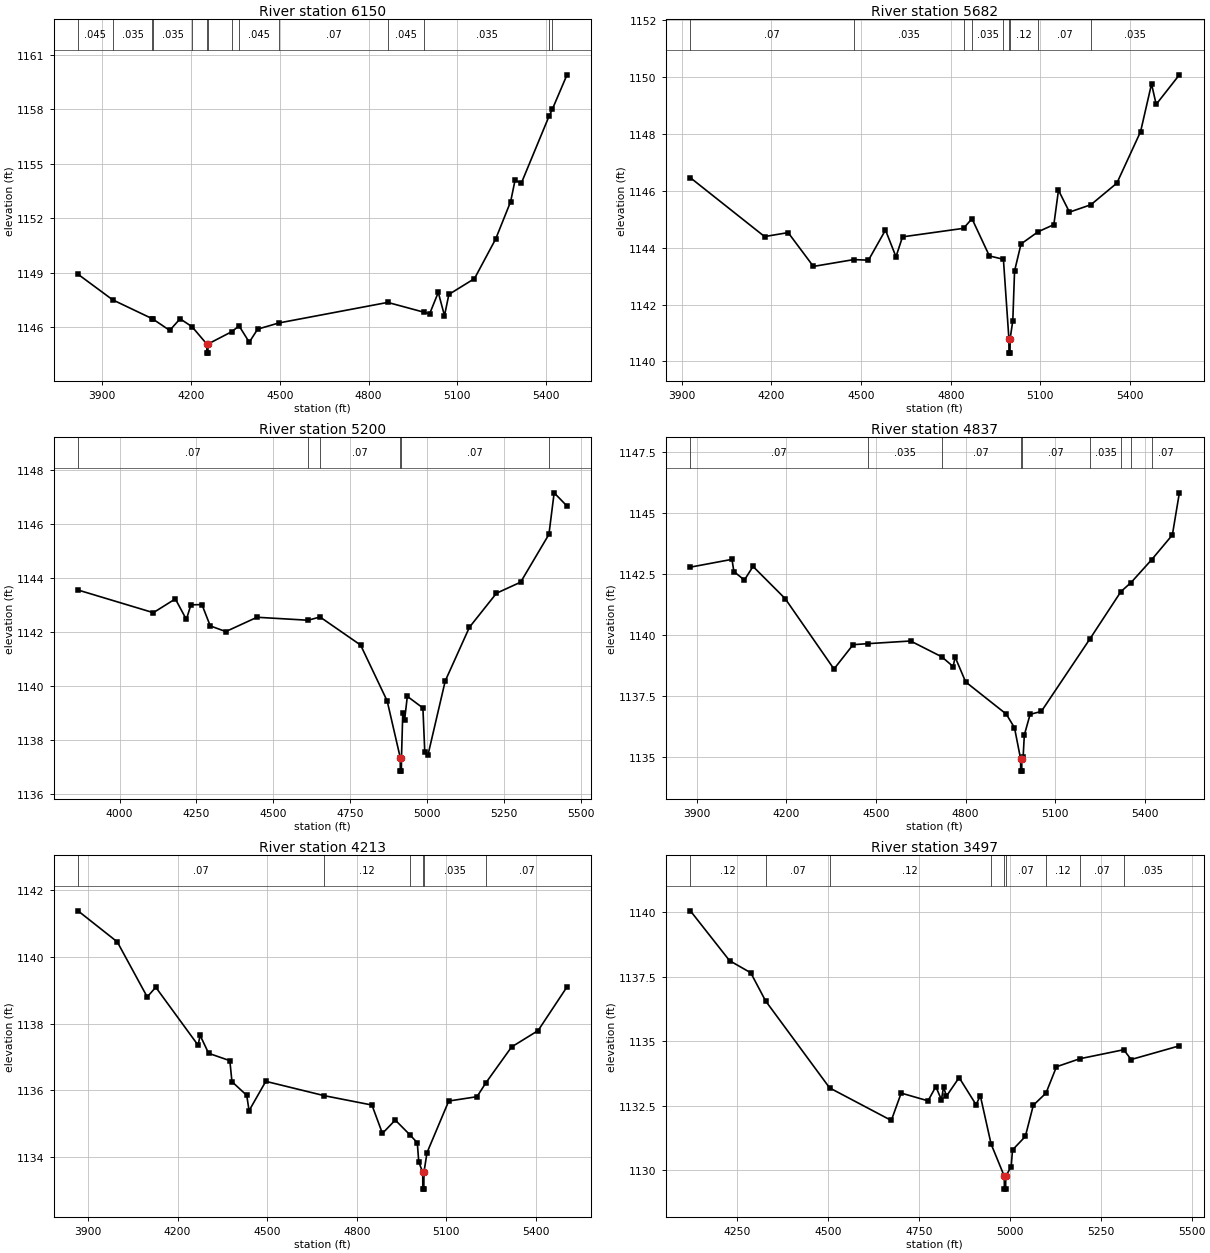
Type RM Length L Ch R = 1,6150,468,468,468
BEGIN DESCRIPTION:
Spring Tributary 3 11.0
END DESCRIPTION:
XS GIS Cut Line= 3
      2143076.31     13878440.38      2142300.22     13877549.78
      2141913.78     13877281.39
#Sta/Elev= 30
  3818.7 1148.92  3936.0 1147.51  4070.0 1146.47  4073.0 1146.44  4128.5 1145.83
  4163.6 1146.47  4204.1 1146.03  4253.7 1145.08  4254.0 1144.58  4257.5 1144.58
  4257.7 1145.08  4338.1 1145.76  4362.8 1146.08  4397.2 1145.18  4425.6 1145.90
  4497.3 1146.24  4865.0 1147.37  4987.5 1146.83  5006.4 1146.74  5035.7 1147.92
  5056.7 1146.64  5071.5 1147.81  5158.0 1148.68  5229.6 1150.86  5280.2 1152.92
  5295.1 1154.10  5316.0 1153.92  5410.0 1157.62  5420.8 1157.99  5470.5 1159.89
#Mann=14,-1,0
  3818.7   0.045       0  3936.0   0.035       0  4070.0   0.045       0
  4073.0   0.035       0  4204.1   0.045       0  4253.7   0.035       0
  4257.7   0.045       0  4338.1   0.035       0  4362.8   0.045       0
  4497.3    0.07       0  4865.0   0.045       0  4987.5   0.035       0
  5410.0    0.12       0  5420.8   0.035       0
Bank Sta=4253.7,4257.7
Exp/Cntr=0.3,0.1

Type RM Length L Ch R = 1,5682,482,482,482
BEGIN DESCRIPTION:
Spring Tributary 3 10.0
END DESCRIPTION:
XS GIS Cut Line= 3
      2143431.95     13877979.03      2142625.00     13877275.00
      2142143.48     13876979.62
#Sta/Elev= 30
  3929.1 1146.46  4177.4 1144.39  4256.2 1144.53  4340.7 1143.34  4475.6 1143.58
  4524.9 1143.56  4581.8 1144.62  4616.9 1143.68  4638.8 1144.38  4843.0 1144.68
  4871.1 1145.02  4929.3 1143.71  4976.3 1143.59  4994.7 1140.79  4994.9 1140.29
  4998.4 1140.29  4998.7 1140.79  5007.7 1141.43  5013.6 1143.18  5035.2 1144.13
  5092.4 1144.56  5145.0 1144.81  5160.5 1146.02  5197.2 1145.25  5268.9 1145.51
  5355.8 1146.27  5435.1 1148.08  5471.8 1149.76  5487.3 1149.04  5564.9 1150.08
#Mann=9,-1,0
  3929.1    0.07       0  4475.6   0.035       0  4843.0    0.07       0
  4871.1   0.035       0  4976.3    0.12       0  4994.7    0.05       0
  4998.7    0.12       0  5092.4    0.07       0  5268.9   0.035       0
Bank Sta=4994.7,4998.7
Exp/Cntr=0.3,0.1

Type RM Length L Ch R = 1,5200,363,363,363
BEGIN DESCRIPTION:
Spring Tributary 3 9.0
END DESCRIPTION:
XS GIS Cut Line= 3
      2143657.54     13877522.33      2142725.00     13876875.00
      2142341.93     13876629.29
#Sta/Elev= 30
  3864.8 1143.57  4109.8 1142.73  4181.4 1143.24  4217.2 1142.48  4232.1 1143.02
  4267.9 1143.03  4294.9 1142.24  4345.6 1142.03  4446.9 1142.56  4612.9 1142.45
  4652.0 1142.57  4783.9 1141.53  4870.3 1139.46  4912.8 1137.36  4913.0 1136.86
  4916.5 1136.86  4916.8 1137.36  4921.0 1139.00  4927.1 1138.77  4935.8 1139.63
  4986.5 1139.20  4992.6 1137.56  5003.0 1137.46  5059.1 1140.20  5137.8 1142.19
  5225.7 1143.45  5304.3 1143.86  5396.3 1145.63  5413.3 1147.17  5455.1 1146.68
#Mann=6,-1,0
  3864.8    0.07       0  4612.9   0.035       0  4652.0    0.07       0
  4912.8    0.05       0  4916.8    0.07       0  5396.3   0.035       0
Bank Sta=4912.8,4916.8
Exp/Cntr=0.3,0.1

Type RM Length L Ch R = 1,4837,624,624,624
BEGIN DESCRIPTION:
Spring Tributary 3 8.0
END DESCRIPTION:
XS GIS Cut Line= 3
      2143757.38     13877267.87      2142875.00     13876575.00
      2142382.54     13876420.26
#Sta/Elev= 30
  3878.1 1142.77  4017.5 1143.09  4023.9 1142.59  4059.1 1142.24  4088.0 1142.80
  4195.6 1141.48  4359.2 1138.59  4423.3 1139.59  4472.4 1139.63  4615.8 1139.74
  4720.4 1139.09  4758.4 1138.69  4765.0 1139.08  4800.3 1138.06  4936.4 1136.74
  4963.9 1136.18  4984.4 1134.90  4984.7 1134.40  4988.2 1134.40  4988.4 1134.90
  4992.8 1134.97  4996.8 1135.88  5016.2 1136.73  5053.8 1136.85  5217.3 1139.84
  5320.6 1141.77  5354.5 1142.14  5422.9 1143.07  5492.7 1144.09  5516.2 1145.82
#Mann=9,-1,0
  3878.1    0.07       0  4472.4   0.035       0  4720.4    0.07       0
  4984.4    0.05       0  4988.4    0.07       0  5217.3   0.035       0
  5320.6    0.07       0  5354.5    0.12       0  5422.9    0.07       0
Bank Sta=4984.4,4988.4
Exp/Cntr=0.3,0.1

Type RM Length L Ch R = 1,4213,716,716,716
BEGIN DESCRIPTION:
Spring Tributary 3 7.0
END DESCRIPTION:
XS GIS Cut Line= 3
      2143800.37     13876945.62      2143075.00     13876075.00
      2142809.80     13875646.30
#Sta/Elev= 30
  3866.8 1141.38  3998.3 1140.45  4098.6 1138.80  4127.2 1139.09  4269.1 1137.35
  4275.6 1137.65  4304.2 1137.11  4375.2 1136.89  4382.3 1136.26  4431.8 1135.85
  4439.6 1135.39  4495.6 1136.27  4691.6 1135.84  4851.0 1135.56  4886.1 1134.71
  4929.1 1135.11  4977.8 1134.67  5002.9 1134.43  5007.7 1133.86  5021.1 1133.54
  5021.3 1133.04  5024.8 1133.04  5025.1 1133.54  5035.3 1134.13  5108.1 1135.68
  5202.7 1135.81  5232.1 1136.22  5318.5 1137.30  5407.2 1137.79  5504.1 1139.10
#Mann=6,-1,0
  3866.8    0.07       0  4691.6    0.12       0  4977.8   0.035       0
  5021.1   0.035       0  5025.1   0.035       0  5232.1    0.07       0
Bank Sta=5021.1,5025.1
Exp/Cntr=0.3,0.1

Type RM Length L Ch R = 1,3497,503,503,503
BEGIN DESCRIPTION:
Spring Tributary 3 6.0
END DESCRIPTION:
XS GIS Cut Line= 3
      2144077.33     13876629.50      2143625.00     13875875.00
      2143268.94     13875573.90
#Sta/Elev= 30
  4120.3 1140.05  4228.2 1138.12  4286.5 1137.65  4327.4 1136.56  4503.7 1133.19
  4673.4 1131.93  4700.6 1132.99  4774.5 1132.69  4795.9 1133.24  4811.4 1132.73
  4817.3 1133.23  4825.1 1132.87  4860.1 1133.59  4906.7 1132.54  4918.4 1132.89
  4948.0 1131.02  4984.4 1129.77  4984.6 1129.27  4988.1 1129.27  4988.4 1129.77
  5003.3 1130.14  5007.1 1130.79  5042.3 1131.31  5064.3 1132.52  5099.2 1132.99
  5128.0 1134.01  5192.2 1134.32  5313.2 1134.67  5333.5 1134.29  5466.3 1134.82
#Mann=9,-1,0
  4120.3    0.12       0  4327.4    0.07       0  4503.7    0.12       0
  4948.0    0.07       0  4984.4    0.05       0  4988.4    0.07       0
  5099.2    0.12       0  5192.2    0.07       0  5313.2   0.035       0
Bank Sta=4984.4,4988.4
Exp/Cntr=0.3,0.1

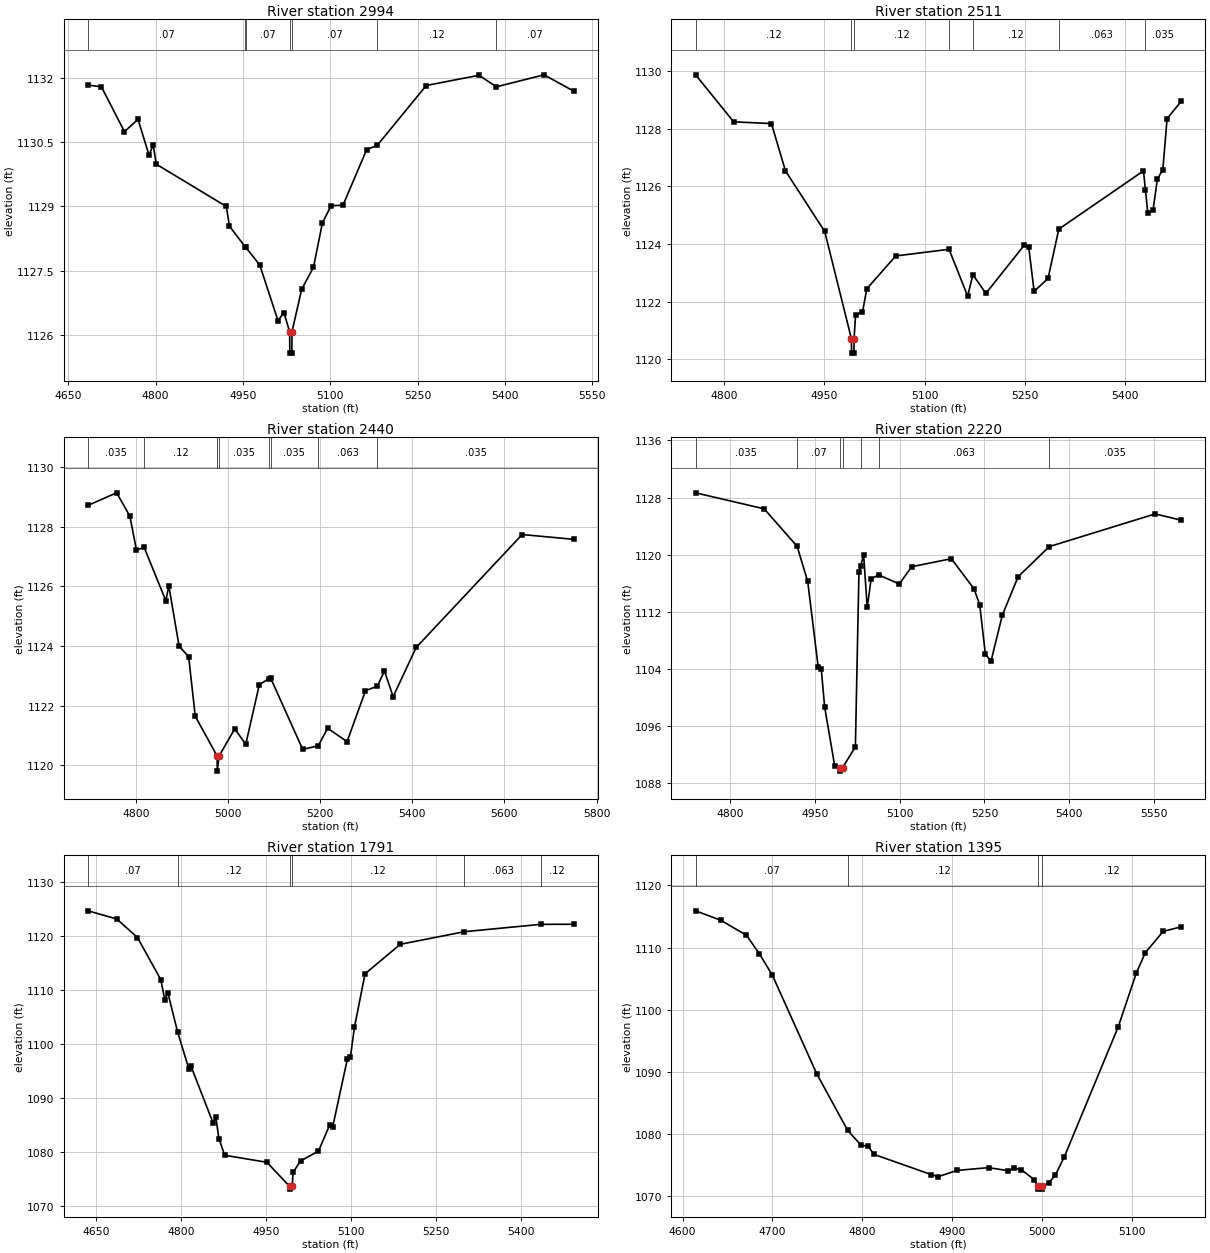
Type RM Length L Ch R = 1,2994,483,483,483
BEGIN DESCRIPTION:
Spring Tributary 3 5.0
END DESCRIPTION:
XS GIS Cut Line= 3
      2144174.15     13875576.50      2143875.00     13875475.00
      2143365.09     13875385.52
#Sta/Elev= 30
  4684.1 1131.84  4707.0 1131.80  4746.6 1130.75  4769.8 1131.04  4788.8 1130.20
  4795.9 1130.44  4801.2 1129.99  4921.5 1129.00  4926.8 1128.54  4953.7 1128.06
  4954.6 1128.05  4978.9 1127.63  5010.2 1126.33  5020.3 1126.52  5030.2 1126.07
  5030.5 1125.57  5034.0 1125.57  5034.2 1126.07  5050.8 1127.06  5071.1 1127.58
  5086.5 1128.62  5101.5 1129.02  5121.8 1129.03  5162.4 1130.33  5180.6 1130.43
  5264.7 1131.83  5355.3 1132.07  5385.1 1131.80  5467.0 1132.08  5517.7 1131.70
#Mann=7,-1,0
  4684.1    0.07       0  4953.7    0.12       0  4954.6    0.07       0
  5030.2    0.05       0  5034.2    0.07       0  5180.6    0.12       0
  5385.1    0.07       0
Bank Sta=5030.2,5034.2
Exp/Cntr=0.3,0.1

Type RM Length L Ch R = 1,2511,71,71,71
BEGIN DESCRIPTION:
Spring Tributary 3 4.0
END DESCRIPTION:
XS GIS Cut Line= 3
      2144316.54     13875371.66      2144175.00     13875175.00
      2143875.56     13874795.26
#Sta/Elev= 30
  4757.7 1129.87  4814.6 1128.24  4871.1 1128.18  4892.0 1126.54  4950.7 1124.44
  4990.6 1120.72  4990.9 1120.22  4994.4 1120.22  4994.6 1120.72  4996.9 1121.55
  5007.2 1121.64  5013.6 1122.45  5056.9 1123.59  5136.6 1123.82  5164.4 1122.20
  5172.3 1122.94  5191.6 1122.29  5249.3 1123.97  5255.7 1123.90  5263.8 1122.36
  5284.6 1122.81  5300.7 1124.52  5427.3 1126.54  5430.2 1125.88  5433.7 1125.09
  5441.7 1125.19  5448.1 1126.26  5456.2 1126.58  5462.6 1128.35  5483.6 1128.95
#Mann=7,-1,0
  4757.7    0.12       0  4990.6    0.05       0  4994.6    0.12       0
  5136.6   0.035       0  5172.3    0.12       0  5300.7   0.063       0
  5430.2   0.035       0
Bank Sta=4990.6,4994.6
Exp/Cntr=0.3,0.1

Type RM Length L Ch R = 1,2440,220,220,220
BEGIN DESCRIPTION:
Spring Tributary 3 3.2
END DESCRIPTION:
XS GIS Cut Line= 4
      2144418.16     13875359.35      2144225.00     13875125.00
      2144131.47     13874897.88      2144123.20     13874393.37
#Sta/Elev= 30
  4696.3 1128.72  4758.3 1129.14  4787.0 1128.36  4801.3 1127.22  4818.0 1127.31
  4865.1 1125.52  4871.6 1126.02  4893.8 1124.00  4914.6 1123.64  4929.0 1121.64
  4976.3 1120.31  4976.5 1120.30  4976.7 1119.80  4980.5 1120.30  5014.7 1121.22
  5038.6 1120.70  5068.0 1122.70  5088.2 1122.90  5092.4 1122.93  5162.2 1120.53
  5195.9 1120.65  5216.3 1121.24  5258.5 1120.79  5298.5 1122.50  5324.1 1122.65
  5339.6 1123.16  5358.5 1122.30  5408.5 1123.95  5638.6 1127.74  5750.2 1127.58
#Mann=9,-1,0
  4696.3   0.035       0  4818.0    0.12       0  4976.3   0.035       0
  4976.5   0.035       0  4980.5   0.035       0  5088.2   0.063       0
  5092.4   0.035       0  5195.9   0.063       0  5324.1   0.035       0
Bank Sta=4976.5,4980.5
Exp/Cntr=0.3,0.1

Type RM Length L Ch R = 1,2220,429,429,429
BEGIN DESCRIPTION:
Spring Tributary 3 3.1
END DESCRIPTION:
XS GIS Cut Line= 4
      2144524.99     13875315.65      2144425.00     13875075.00
      2144359.93     13874987.26      2144336.04     13874499.18
#Sta/Elev= 30
  4739.4 1128.67  4860.6 1126.43  4918.9 1121.18  4937.6 1116.26  4956.1 1104.32
  4961.5 1104.06  4967.5 1098.73  4985.4 1090.42  4995.3 1090.22  4995.5 1089.72
  4999.3 1090.22  5021.9 1093.12  5028.2 1117.60  5031.1 1118.42  5036.5 1119.95
  5042.8 1112.63  5049.8 1116.64  5063.1 1117.18  5099.6 1115.91  5121.5 1118.33
  5191.6 1119.45  5231.6 1115.24  5241.7 1113.02  5251.7 1106.10  5261.7 1105.10
  5281.7 1111.54  5309.6 1116.92  5364.6 1121.14  5552.0 1125.72  5597.9 1124.84
#Mann=7,-1,0
  4739.4   0.035       0  4918.9    0.07       0  4995.3    0.05       0
  4999.3    0.07       0  5031.1    0.12       0  5063.1   0.063       0
  5364.6   0.035       0
Bank Sta=4995.3,4999.3
Exp/Cntr=0.3,0.1

Type RM Length L Ch R = 1,1791,396,396,396
BEGIN DESCRIPTION:
Spring Tributary 3 3.0
END DESCRIPTION:
XS GIS Cut Line= 3
      2144658.60     13875229.89      2144741.72     13874875.00
      2144580.19     13874409.53
#Sta/Elev= 30
  4635.5 1124.67  4686.1 1123.16  4722.7 1119.72  4763.8 1111.92  4771.1 1108.11
  4776.2 1109.51  4793.6 1102.20  4813.5 1095.31  4817.1 1095.87  4856.0 1085.38
  4861.1 1086.34  4866.5 1082.42  4876.7 1079.32  4951.2 1078.02  4991.5 1073.54
  4991.8 1073.04  4995.9 1073.54  4997.4 1076.14  5010.6 1078.26  5042.3 1080.10
  5062.2 1084.97  5067.5 1084.65  5093.4 1097.22  5098.7 1097.55  5105.8 1103.07
  5124.5 1112.99  5186.7 1118.46  5300.0 1120.80  5434.6 1122.16  5492.7 1122.18
#Mann=6,-1,0
  4635.5    0.07       0  4793.6    0.12       0  4991.5    0.05       0
  4995.9    0.12       0  5300.0   0.063       0  5434.6    0.12       0
Bank Sta=4991.5,4995.9
Exp/Cntr=0.3,0.1

Type RM Length L Ch R = 1,1395,443,443,443
BEGIN DESCRIPTION:
Spring Tributary 3 2.0
END DESCRIPTION:
XS GIS Cut Line= 3
      2144825.01     13875174.99      2145125.00     13874925.00
      2145125.00     13874775.00
#Sta/Elev= 30
  4614.5 1115.92  4642.5 1114.40  4671.1 1111.99  4685.4 1109.02  4699.8 1105.60
  4749.2 1089.72  4783.7 1080.59  4798.7 1078.17  4806.5 1078.03  4813.0 1076.71
  4876.8 1073.45  4884.6 1073.12  4905.4 1074.12  4940.6 1074.57  4962.7 1074.07
  4969.2 1074.46  4977.0 1074.25  4991.3 1072.65  4995.6 1071.61  4995.9 1071.11
  4999.7 1071.11  5000.0 1071.61  5007.5 1072.06  5015.0 1073.38  5025.0 1076.32
  5085.0 1097.25  5105.0 1105.86  5115.0 1109.16  5135.0 1112.61  5155.0 1113.34
#Mann=4,-1,0
  4614.5    0.07       0  4783.7    0.12       0  4995.6    0.05       0
  5000.0    0.12       0
Bank Sta=4995.6,5000
Exp/Cntr=0.3,0.1

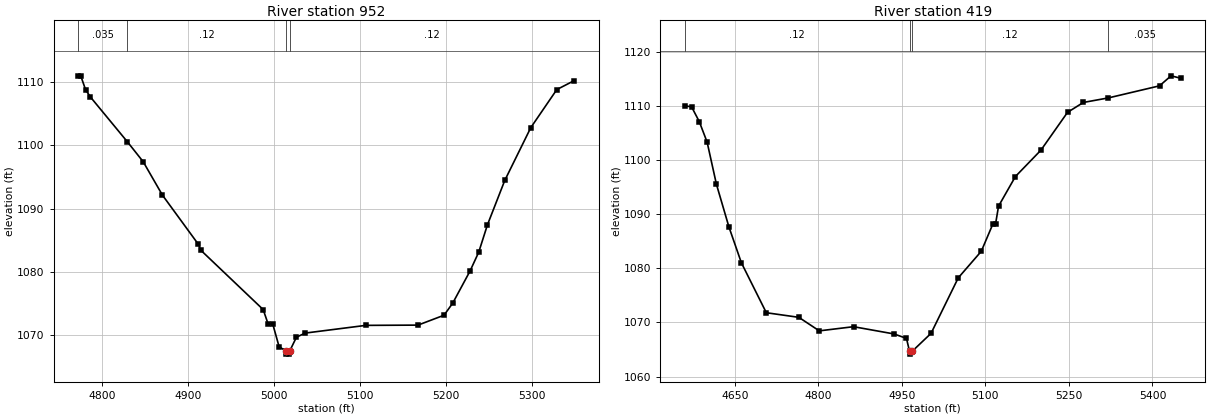
Type RM Length L Ch R = 1,952,533,533,533
BEGIN DESCRIPTION:
Spring Tributary 3 1.0
END DESCRIPTION:
XS GIS Cut Line= 3
      2145324.99     13875425.02      2145425.00     13875225.00
      2145475.00     13874874.99
#Sta/Elev= 30
  4772.1 1110.98  4774.9 1110.98  4780.5 1108.80  4786.1 1107.65  4829.3 1100.55
  4847.6 1097.42  4870.0 1092.15  4911.9 1084.37  4914.7 1083.45  4987.3 1074.08
  4992.9 1071.86  4998.3 1071.86  5005.8 1068.23  5013.7 1067.55  5014.0 1067.05
  5017.9 1067.05  5018.2 1067.55  5026.0 1069.72  5036.1 1070.37  5106.8 1071.59
  5167.5 1071.63  5197.8 1073.19  5207.9 1075.09  5228.1 1080.17  5238.2 1083.14
  5248.3 1087.44  5268.5 1094.46  5298.8 1102.80  5329.1 1108.81  5349.3 1110.22
#Mann=4,-1,0
  4772.1   0.035       0  4829.3    0.12       0  5013.7    0.05       0
  5018.2    0.12       0
Bank Sta=5013.7,5018.2
Exp/Cntr=0.3,0.1

Type RM Length L Ch R = 1,419,0,0,0
BEGIN DESCRIPTION:
Spring Tributary 3 0.0
END DESCRIPTION:
XS GIS Cut Line= 3
      2145663.33     13875418.25      2145859.57     13875024.66
      2145747.01     13874588.35
#Sta/Elev= 30
  4560.2 1110.02  4572.3 1109.87  4586.2 1107.12  4600.3 1103.32  4617.0 1095.54
  4639.4 1087.67  4661.8 1081.03  4706.6 1071.80  4765.0 1070.95  4801.7 1068.45
  4863.2 1069.22  4935.9 1067.88  4958.3 1067.06  4963.8 1064.65  4964.1 1064.15
  4968.3 1064.65  5002.4 1067.99  5051.3 1078.25  5092.6 1083.15  5113.2 1088.14
  5118.4 1088.28  5123.6 1091.49  5153.9 1096.97  5199.7 1101.84  5247.5 1108.83
  5275.9 1110.66  5320.9 1111.50  5412.7 1113.73  5433.4 1115.58  5450.6 1115.14
#Mann=4,-1,0
  4560.2    0.12       0  4963.8    0.05       0  4968.3    0.12       0
  5320.9   0.035       0
Bank Sta=4963.8,4968.3
Exp/Cntr=0.3,0.1

Chan Stop Cuts=-1