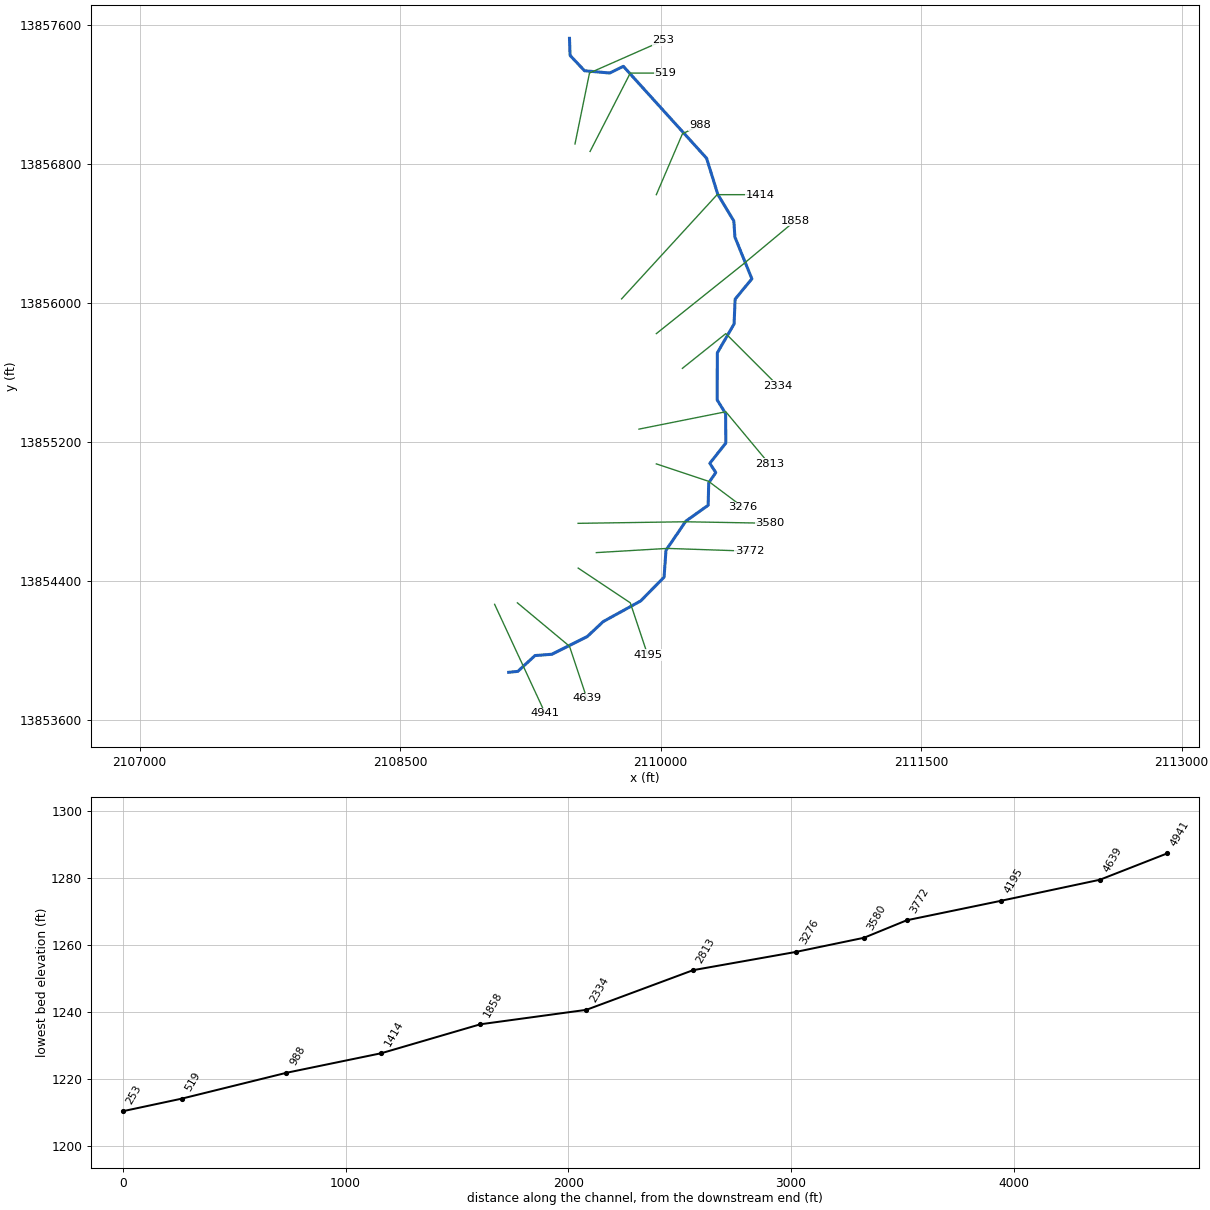
--- Stream0001_DS.prj (project) ---

Proj Title=Stream0001_DS Base Level Engineering
Current Plan=p01
Default Exp/Contr=0.3,0.1
English Units
Geom File=g01
Flow File=f01
Plan File=p01
BEGIN DESCRIPTION:
Stream0001_DS
END DESCRIPTION:

--- Stream0001_DS.p01 (plan) ---

Plan Title=Multiple Run
Short Identifier=Multiple
Geom File=g01
Flow File=f01
Subcritical Flow
K Sum by GR= 0
Std Step Tol= 0.01
Critical Tol= 0.01
Num of Std Step Trials= 20
Max Error Tol= 0.3
Flow Tol Ratio= 0.001
Split Flow NTrial= 30
Split Flow Tol= 0.02
Split Flow Ratio= 0.02
Log Output Level= 0
Friction Slope Method= 1
Unsteady Friction Slope Method= 2
Unsteady Bridges Friction Slope Method= 1
Parabolic Critical Depth
Global Vel Dist=  1 , 1 , 1
Global Log Level= 0
CheckData=True
Encroach Param= -1, 0, 0, 0
BEGIN DESCRIPTION:
Multiple Run
END DESCRIPTION:

--- Stream0001_DS.f01 (steady flow) ---

Flow Title=Multiple
Number of Profiles=7
Profile Names=10-year,25-year,50-year,1pct_min,100-year,1pct_plu,500-year
River Rch & RM= Stream0001_DS,Reach-1,4941
     911    1520    2090    1394    2782    5550    4870
Boundary for River Rch & Prof#=Stream0001_DS,Reach-1,1
Up Type=0
Dn Type=3
Dn Slope=0.005
Boundary for River Rch & Prof#=Stream0001_DS,Reach-1,2
Up Type=0
Dn Type=3
Dn Slope=0.005
Boundary for River Rch & Prof#=Stream0001_DS,Reach-1,3
Up Type=0
Dn Type=3
Dn Slope=0.005
Boundary for River Rch & Prof#=Stream0001_DS,Reach-1,4
Up Type=0
Dn Type=3
Dn Slope=0.005
Boundary for River Rch & Prof#=Stream0001_DS,Reach-1,5
Up Type=0
Dn Type=3
Dn Slope=0.005
Boundary for River Rch & Prof#=Stream0001_DS,Reach-1,6
Up Type=0
Dn Type=3
Dn Slope=0.005
Boundary for River Rch & Prof#=Stream0001_DS,Reach-1,7
Up Type=0
Dn Type=3
Dn Slope=0.005

--- Stream0001_DS.g01 (geometry) ---

Geom Title=Existing Conditions

River Reach=Stream0001_DS,Reach-1
Reach XY= 30
      2109125.00     13853875.00      2109177.51     13853880.33
      2109276.50     13853971.39      2109373.41     13853978.83
      2109577.29     13854080.85      2109668.96     13854166.82
      2109884.68     13854285.78      2110019.53     13854422.55
      2110030.48     13854577.44      2110144.78     13854745.13
      2110273.36     13854836.83      2110276.56     13854965.39
      2110317.19     13855025.10      2110283.01     13855078.33
      2110375.04     13855194.98      2110373.78     13855364.49
      2110325.21     13855443.27      2110326.20     13855714.50
      2110422.64     13855880.52      2110428.56     13856023.53
      2110525.04     13856140.34      2110427.35     13856380.97
      2110421.17     13856473.42      2110328.83     13856626.58
      2110264.24     13856834.68      2109785.06     13857363.90
      2109706.77     13857325.32      2109561.65     13857338.35
      2109478.37     13857426.39      2109475.00     13857525.00

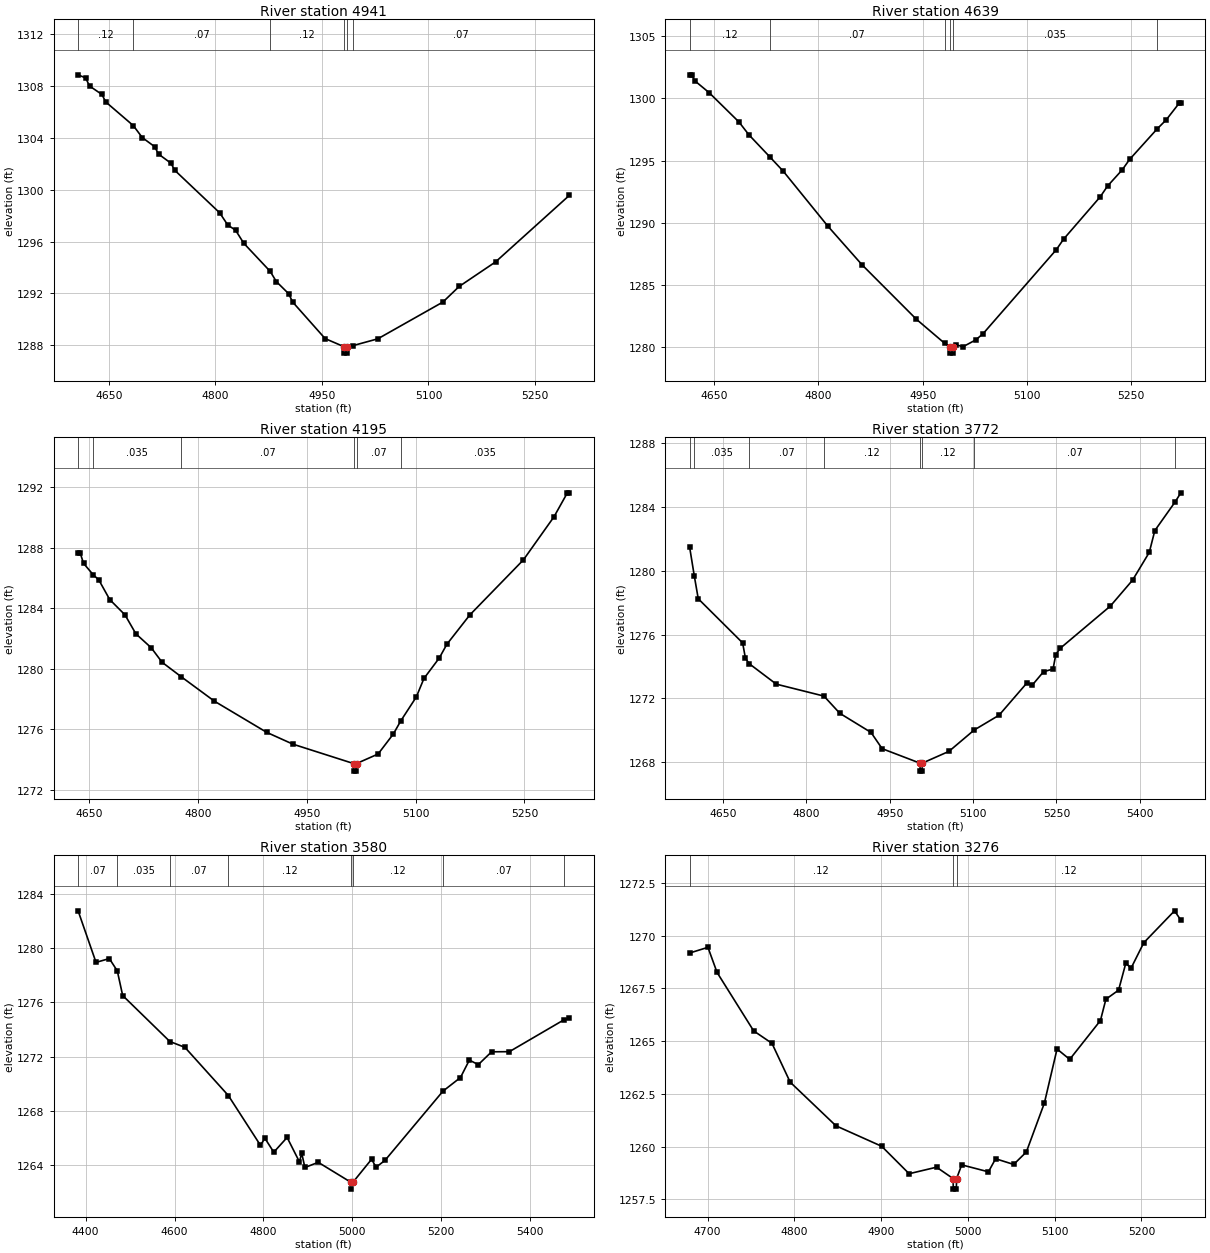
Type RM Length L Ch R = 1,4941,302,302,302
BEGIN DESCRIPTION:
Stream0001_DS 11.0
END DESCRIPTION:
XS GIS Cut Line= 2
      2109043.97     13854266.24      2109334.97     13853638.51
#Sta/Elev= 30
  4606.5 1308.83  4617.1 1308.59  4622.6 1307.97  4640.0 1307.32  4645.5 1306.74
  4684.3 1304.92  4696.9 1304.00  4714.3 1303.30  4719.8 1302.73  4737.2 1302.03
  4742.7 1301.48  4805.9 1298.21  4817.3 1297.27  4828.3 1296.87  4839.8 1295.87
  4877.1 1293.70  4885.7 1292.92  4903.1 1291.98  4908.6 1291.35  4954.4 1288.53
  4980.8 1287.91  4981.1 1287.41  4984.6 1287.41  4984.8 1287.91  4993.8 1287.99
  5028.6 1288.51  5120.3 1291.34  5143.2 1292.54  5194.5 1294.43  5298.4 1299.55
#Mann=6,-1,0
  4606.5    0.12       0  4684.3    0.07       0  4877.1    0.12       0
  4980.8    0.05       0  4984.8    0.12       0  4993.8    0.07       0
Bank Sta=4980.8,4984.8
Exp/Cntr=0.3,0.1

Type RM Length L Ch R = 1,4639,444,444,444
BEGIN DESCRIPTION:
Stream0001_DS 10.0
END DESCRIPTION:
XS GIS Cut Line= 3
      2109174.97     13854275.03      2109475.00     13854025.00
      2109575.01     13853724.98
#Sta/Elev= 30
  4614.7 1301.90  4618.0 1301.90  4621.9 1301.43  4642.7 1300.47  4685.7 1298.11
  4700.0 1297.08  4729.7 1295.33  4749.5 1294.15  4813.3 1289.76  4862.7 1286.64
  4940.8 1282.27  4981.8 1280.32  4989.6 1280.04  4989.8 1279.54  4993.3 1279.54
  4993.6 1280.04  4998.1 1280.22  5007.9 1280.05  5026.3 1280.60  5036.9 1281.10
  5142.3 1287.85  5152.8 1288.70  5205.5 1292.10  5216.1 1292.97  5237.2 1294.27
  5247.7 1295.10  5287.3 1297.55  5300.4 1298.28  5318.8 1299.60  5321.5 1299.60
#Mann=6,-1,0
  4614.7    0.12       0  4729.7    0.07       0  4981.8   0.035       0
  4989.6   0.035       0  4993.6   0.035       0  5287.3    0.12       0
Bank Sta=4989.6,4993.6
Exp/Cntr=0.3,0.1

Type RM Length L Ch R = 1,4195,423,423,423
BEGIN DESCRIPTION:
Stream0001_DS 9.0
END DESCRIPTION:
XS GIS Cut Line= 3
      2109525.00     13854475.00      2109825.00     13854275.00
      2109925.00     13853974.99
#Sta/Elev= 30
  4635.1 1287.64  4638.1 1287.64  4642.6 1286.97  4656.1 1286.21  4663.6 1285.88
  4678.7 1284.58  4699.7 1283.57  4714.7 1282.32  4735.8 1281.40  4750.8 1280.44
  4777.0 1279.49  4822.9 1277.87  4895.0 1275.81  4931.1 1275.03  5014.7 1273.75
  5015.0 1273.25  5018.5 1273.25  5018.7 1273.75  5048.4 1274.38  5069.4 1275.70
  5079.7 1276.57  5101.1 1278.15  5111.6 1279.37  5132.7 1280.72  5143.2 1281.63
  5174.9 1283.57  5248.6 1287.20  5290.8 1290.05  5309.2 1291.63  5311.9 1291.63
#Mann=6,-1,0
  4635.1    0.12       0  4656.1   0.035       0  4777.0    0.07       0
  5014.7    0.05       0  5018.7    0.07       0  5079.7   0.035       0
Bank Sta=5014.7,5018.7
Exp/Cntr=0.3,0.1

Type RM Length L Ch R = 1,3772,192,192,192
BEGIN DESCRIPTION:
Stream0001_DS 8.0
END DESCRIPTION:
XS GIS Cut Line= 3
      2109629.52     13854564.09      2110038.40     13854588.31
      2110511.73     13854572.31
#Sta/Elev= 30
  4590.4 1281.49  4598.8 1279.68  4605.9 1278.25  4685.7 1275.48  4690.7 1274.52
  4697.3 1274.18  4746.2 1272.89  4831.9 1272.14  4860.4 1271.06  4916.5 1269.86
  4936.5 1268.84  5004.6 1267.93  5004.9 1267.43  5008.4 1267.43  5008.6 1267.93
  5056.6 1268.67  5102.0 1270.01  5146.7 1270.94  5196.7 1272.96  5206.7 1272.84
  5226.7 1273.67  5243.8 1273.84  5248.8 1274.75  5256.7 1275.14  5346.8 1277.79
  5386.8 1279.42  5416.8 1281.16  5426.8 1282.53  5463.1 1284.32  5473.6 1284.90
#Mann=8,-1,0
  4590.4    0.07       0  4598.8   0.035       0  4697.3    0.07       0
  4831.9    0.12       0  5004.6    0.05       0  5008.6    0.12       0
  5102.0    0.07       0  5463.1   0.035       0
Bank Sta=5004.6,5008.6
Exp/Cntr=0.3,0.1

Type RM Length L Ch R = 1,3580,304,304,304
BEGIN DESCRIPTION:
Stream0001_DS 7.5
END DESCRIPTION:
XS GIS Cut Line= 3
      2109524.71     13854732.65      2110141.64     13854741.70
      2110629.87     13854733.10
#Sta/Elev= 30
  4383.0 1282.77  4423.3 1278.96  4453.3 1279.24  4471.2 1278.33  4483.3 1276.51
  4589.5 1273.11  4623.3 1272.68  4721.0 1269.12  4793.3 1265.44  4803.3 1265.96
  4823.3 1264.93  4853.3 1266.02  4881.1 1264.21  4886.1 1264.86  4893.3 1263.80
  4923.4 1264.18  4997.2 1262.70  4997.4 1262.20  5001.2 1262.70  5043.4 1264.41
  5053.4 1263.82  5073.4 1264.32  5203.9 1269.44  5243.4 1270.45  5263.4 1271.74
  5283.4 1271.40  5313.4 1272.35  5353.4 1272.36  5476.5 1274.72  5488.3 1274.82
#Mann=8,-1,0
  4383.0    0.07       0  4471.2   0.035       0  4589.5    0.07       0
  4721.0    0.12       0  4997.2    0.05       0  5001.2    0.12       0
  5203.9    0.07       0  5476.5   0.035       0
Bank Sta=4997.2,5001.2
Exp/Cntr=0.3,0.1

Type RM Length L Ch R = 1,3276,463,463,463
BEGIN DESCRIPTION:
Stream0001_DS 7.0
END DESCRIPTION:
XS GIS Cut Line= 3
      2109975.00     13855075.00      2110275.00     13854975.00
      2110474.98     13854825.02
#Sta/Elev= 30
  4679.3 1269.18  4700.4 1269.45  4710.9 1268.26  4753.1 1265.49  4774.2 1264.90
  4795.2 1263.06  4848.0 1260.99  4900.7 1260.02  4932.3 1258.72  4963.9 1259.03
  4983.0 1258.49  4983.2 1257.99  4986.7 1257.99  4987.0 1258.49  4992.9 1259.14
  5023.7 1258.81  5032.0 1259.43  5052.8 1259.16  5067.4 1259.75  5088.2 1262.07
  5102.8 1264.63  5117.4 1264.14  5152.8 1265.98  5159.1 1266.99  5173.7 1267.42
  5182.0 1268.69  5188.2 1268.47  5202.8 1269.67  5238.2 1271.18  5245.5 1270.74
#Mann=3,-1,0
  4679.3    0.12       0  4983.0    0.05       0  4987.0    0.12       0
Bank Sta=4983,4987
Exp/Cntr=0.3,0.1

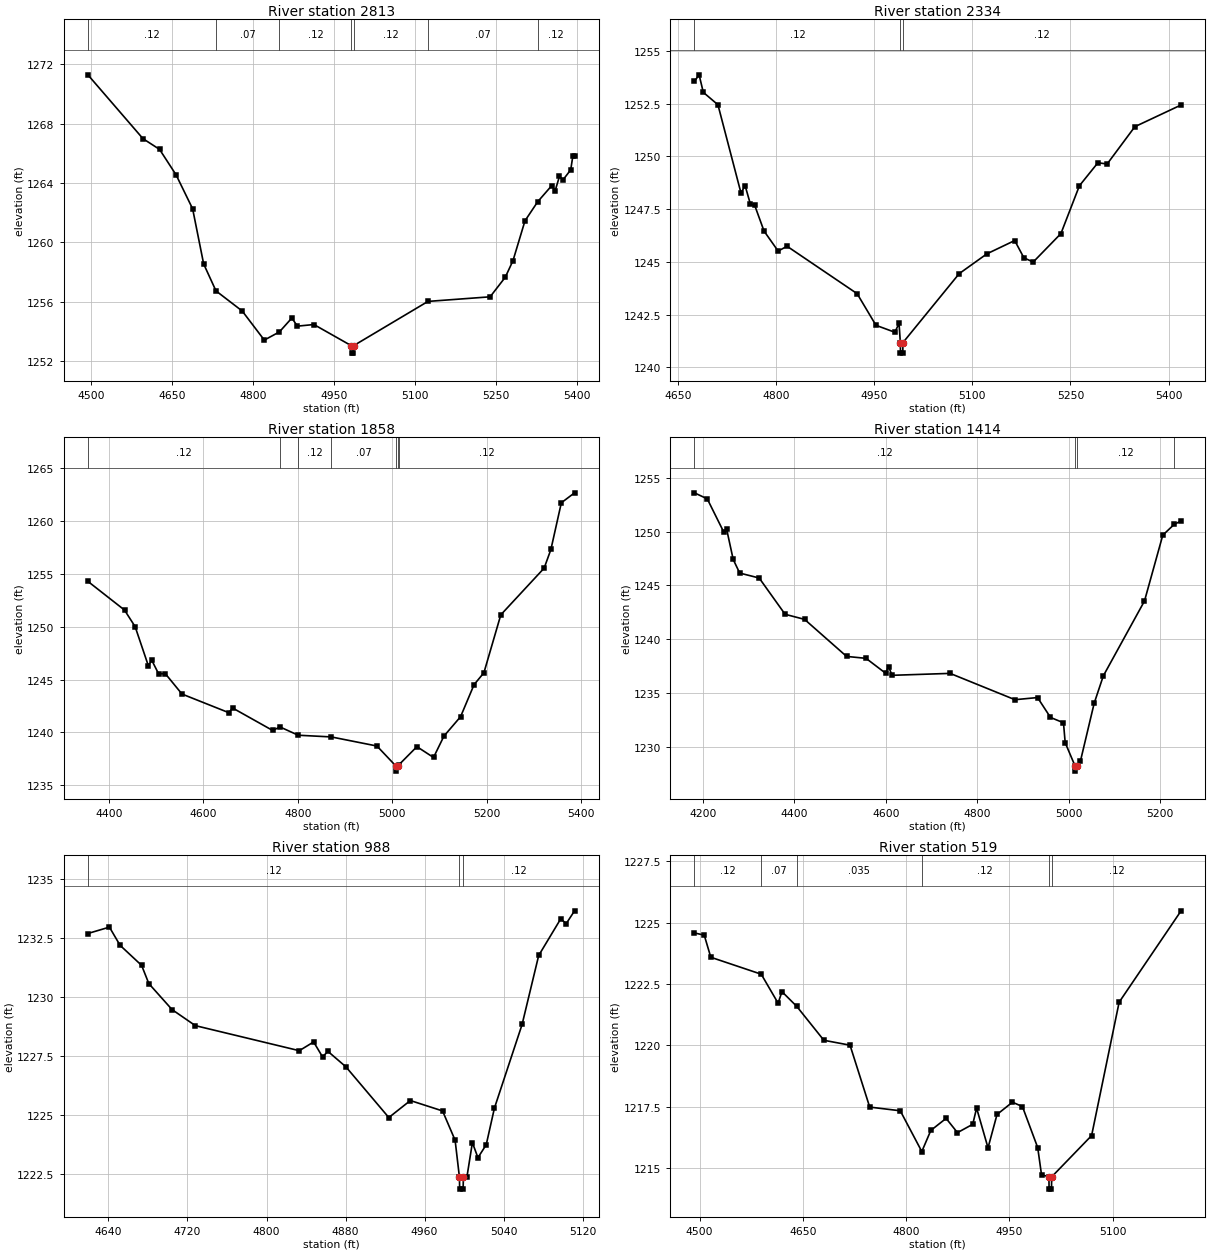
Type RM Length L Ch R = 1,2813,479,479,479
BEGIN DESCRIPTION:
Stream0001_DS 6.0
END DESCRIPTION:
XS GIS Cut Line= 3
      2109874.97     13855274.99      2110375.00     13855375.00
      2110624.97     13855075.04
#Sta/Elev= 30
  4494.3 1271.30  4596.3 1266.99  4626.9 1266.27  4657.5 1264.55  4688.1 1262.26
  4708.5 1258.54  4731.3 1256.72  4779.9 1255.36  4820.7 1253.40  4848.6 1253.95
  4871.7 1254.89  4881.9 1254.34  4912.5 1254.45  4981.8 1253.02  4982.1 1252.52
  4985.6 1252.52  4985.8 1253.02  5123.5 1256.01  5238.5 1256.32  5266.5 1257.64
  5280.8 1258.76  5303.0 1261.45  5326.6 1262.74  5352.4 1263.82  5358.9 1263.49
  5366.8 1264.45  5373.3 1264.21  5387.6 1264.89  5391.5 1265.81  5394.7 1265.81
#Mann=7,-1,0
  4494.3    0.12       0  4731.3    0.07       0  4848.6    0.12       0
  4981.8    0.05       0  4985.8    0.12       0  5123.5    0.07       0
  5326.6    0.12       0
Bank Sta=4981.8,4985.8
Exp/Cntr=0.3,0.1

Type RM Length L Ch R = 1,2334,476,476,476
BEGIN DESCRIPTION:
Stream0001_DS 5.0
END DESCRIPTION:
XS GIS Cut Line= 3
      2110124.99     13855624.99      2110375.00     13855825.00
      2110674.98     13855525.02
#Sta/Elev= 30
  4674.8 1253.56  4682.0 1253.87  4688.4 1253.04  4710.8 1252.45  4746.0 1248.27
  4752.4 1248.61  4760.5 1247.73  4766.9 1247.69  4781.3 1246.46  4802.9 1245.51
  4816.5 1245.74  4923.7 1243.49  4952.5 1241.99  4981.4 1241.66  4987.8 1242.08
  4989.8 1241.17  4990.0 1240.67  4993.5 1240.67  4993.8 1241.17  5079.8 1244.44
  5122.2 1245.38  5164.7 1246.01  5178.8 1245.19  5193.0 1244.99  5235.4 1246.34
  5263.7 1248.61  5292.0 1249.70  5306.1 1249.64  5348.5 1251.41  5419.2 1252.44
#Mann=3,-1,0
  4674.8    0.12       0  4989.8    0.05       0  4993.8    0.12       0
Bank Sta=4989.8,4993.8
Exp/Cntr=0.3,0.1

Type RM Length L Ch R = 1,1858,444,444,444
BEGIN DESCRIPTION:
Stream0001_DS 4.0
END DESCRIPTION:
XS GIS Cut Line= 3
      2109975.00     13855825.00      2110475.00     13856225.00
      2110774.98     13856474.98
#Sta/Elev= 30
  4355.2 1254.27  4432.8 1251.56  4455.3 1249.99  4483.3 1246.30  4490.5 1246.82
  4504.9 1245.55  4519.3 1245.55  4554.5 1243.63  4653.7 1241.87  4661.8 1242.31
  4746.6 1240.19  4762.2 1240.52  4800.7 1239.74  4870.7 1239.58  4967.5 1238.72
  5007.2 1236.85  5007.4 1236.35  5011.2 1236.85  5014.0 1236.95  5052.1 1238.66
  5087.3 1237.64  5109.4 1239.66  5144.6 1241.49  5173.2 1244.52  5194.0 1245.64
  5229.8 1251.11  5321.6 1255.52  5335.9 1257.28  5358.0 1261.69  5386.0 1262.63
#Mann=7,-1,0
  4355.2    0.12       0  4762.2    0.07       0  4800.7    0.12       0
  4870.7    0.07       0  5007.2    0.05       0  5011.2    0.07       0
  5014.0    0.12       0
Bank Sta=5007.2,5011.2
Exp/Cntr=0.3,0.1

Type RM Length L Ch R = 1,1414,426,426,426
BEGIN DESCRIPTION:
Stream0001_DS 3.0
END DESCRIPTION:
XS GIS Cut Line= 3
      2109774.97     13856024.97      2110325.00     13856625.00
      2110575.01     13856625.00
#Sta/Elev= 30
  4181.4 1253.62  4209.5 1253.06  4245.3 1249.99  4252.0 1250.21  4266.2 1247.42
  4280.4 1246.15  4323.0 1245.69  4379.7 1242.31  4422.2 1241.84  4514.1 1238.39
  4556.7 1238.21  4599.2 1236.83  4606.0 1237.44  4613.4 1236.63  4740.4 1236.81
  4882.2 1234.36  4931.6 1234.56  4959.9 1232.71  4988.3 1232.21  4992.0 1230.36
  5013.4 1228.21  5013.6 1227.71  5017.4 1228.21  5025.4 1228.65  5055.4 1234.03
  5075.4 1236.58  5165.4 1243.55  5205.4 1249.68  5230.3 1250.68  5245.4 1251.00
#Mann=4,-1,0
  4181.4    0.12       0  5013.4    0.05       0  5017.4    0.12       0
  5230.3    0.07       0
Bank Sta=5013.4,5017.4
Exp/Cntr=0.3,0.1

Type RM Length L Ch R = 1,988,469,469,469
BEGIN DESCRIPTION:
Stream0001_DS 2.0
END DESCRIPTION:
XS GIS Cut Line= 3
      2109975.00     13856625.00      2110125.00     13856975.00
      2110225.00     13857025.00
#Sta/Elev= 30
  4619.2 1232.68  4641.0 1232.95  4651.8 1232.18  4673.6 1231.33  4680.9 1230.56
  4704.4 1229.46  4728.0 1228.78  4833.2 1227.72  4847.7 1228.09  4856.7 1227.46
  4862.2 1227.69  4880.3 1227.04  4923.8 1224.89  4945.6 1225.61  4978.2 1225.17
  4990.9 1223.93  4995.3 1222.36  4995.5 1221.86  4999.0 1221.86  4999.3 1222.36
  5002.8 1222.36  5008.4 1223.83  5014.0 1223.19  5022.4 1223.74  5030.7 1225.29
  5058.7 1228.83  5075.5 1231.75  5097.8 1233.30  5103.4 1233.10  5111.8 1233.64
#Mann=3,-1,0
  4619.2    0.12       0  4995.3    0.05       0  4999.3    0.12       0
Bank Sta=4995.3,4999.3
Exp/Cntr=0.3,0.1

Type RM Length L Ch R = 1,519,266,266,266
BEGIN DESCRIPTION:
Stream0001_DS 1.0
END DESCRIPTION:
XS GIS Cut Line= 3
      2109593.48     13856873.85      2109825.00     13857325.00
      2110025.01     13857325.00
#Sta/Elev= 30
  4492.4 1224.58  4506.7 1224.49  4516.2 1223.59  4589.5 1222.90  4614.0 1221.72
  4619.6 1222.19  4641.1 1221.59  4680.5 1220.21  4718.5 1220.01  4747.1 1217.49
  4791.5 1217.34  4822.8 1215.68  4835.9 1216.54  4858.1 1217.03  4874.6 1216.45
  4896.8 1216.79  4902.4 1217.45  4919.0 1215.83  4932.1 1217.19  4954.5 1217.69
  4969.0 1217.51  4991.2 1215.84  4996.7 1214.74  5007.5 1214.65  5007.7 1214.15
  5011.2 1214.15  5011.5 1214.65  5069.5 1216.33  5109.5 1221.76  5199.5 1225.48
#Mann=6,-1,0
  4492.4    0.12       0  4589.5    0.07       0  4641.1   0.035       0
  4822.8    0.12       0  5007.5    0.05       0  5011.5    0.12       0
Bank Sta=5007.5,5011.5
Exp/Cntr=0.3,0.1

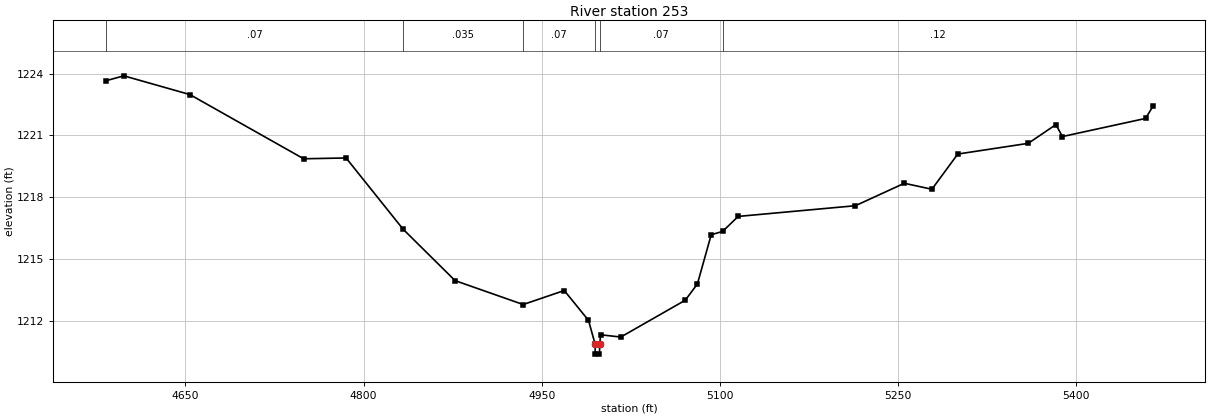
Type RM Length L Ch R = 1,253,0,0,0
BEGIN DESCRIPTION:
Stream0001_DS 0.0
END DESCRIPTION:
XS GIS Cut Line= 3
      2109506.61     13856916.82      2109590.16     13857325.36
      2110015.41     13857512.73
#Sta/Elev= 30
  4583.0 1223.65  4598.2 1223.89  4653.8 1222.98  4749.6 1219.86  4785.3 1219.90
  4833.3 1216.44  4877.1 1213.94  4934.4 1212.78  4969.0 1213.46  4989.4 1212.01
  4994.9 1210.87  4995.1 1210.37  4998.6 1210.37  4998.9 1210.87  4999.6 1211.31
  5016.6 1211.20  5070.9 1212.99  5081.1 1213.78  5092.7 1216.17  5102.3 1216.33
  5115.4 1217.06  5214.1 1217.58  5255.3 1218.67  5278.5 1218.38  5300.3 1220.09
  5359.6 1220.61  5382.9 1221.52  5388.4 1220.94  5458.4 1221.82  5464.7 1222.42
#Mann=6,-1,0
  4583.0    0.07       0  4833.3   0.035       0  4934.4    0.07       0
  4994.9    0.05       0  4998.9    0.07       0  5102.3    0.12       0
Bank Sta=4994.9,4998.9
Exp/Cntr=0.3,0.1

Chan Stop Cuts=-1