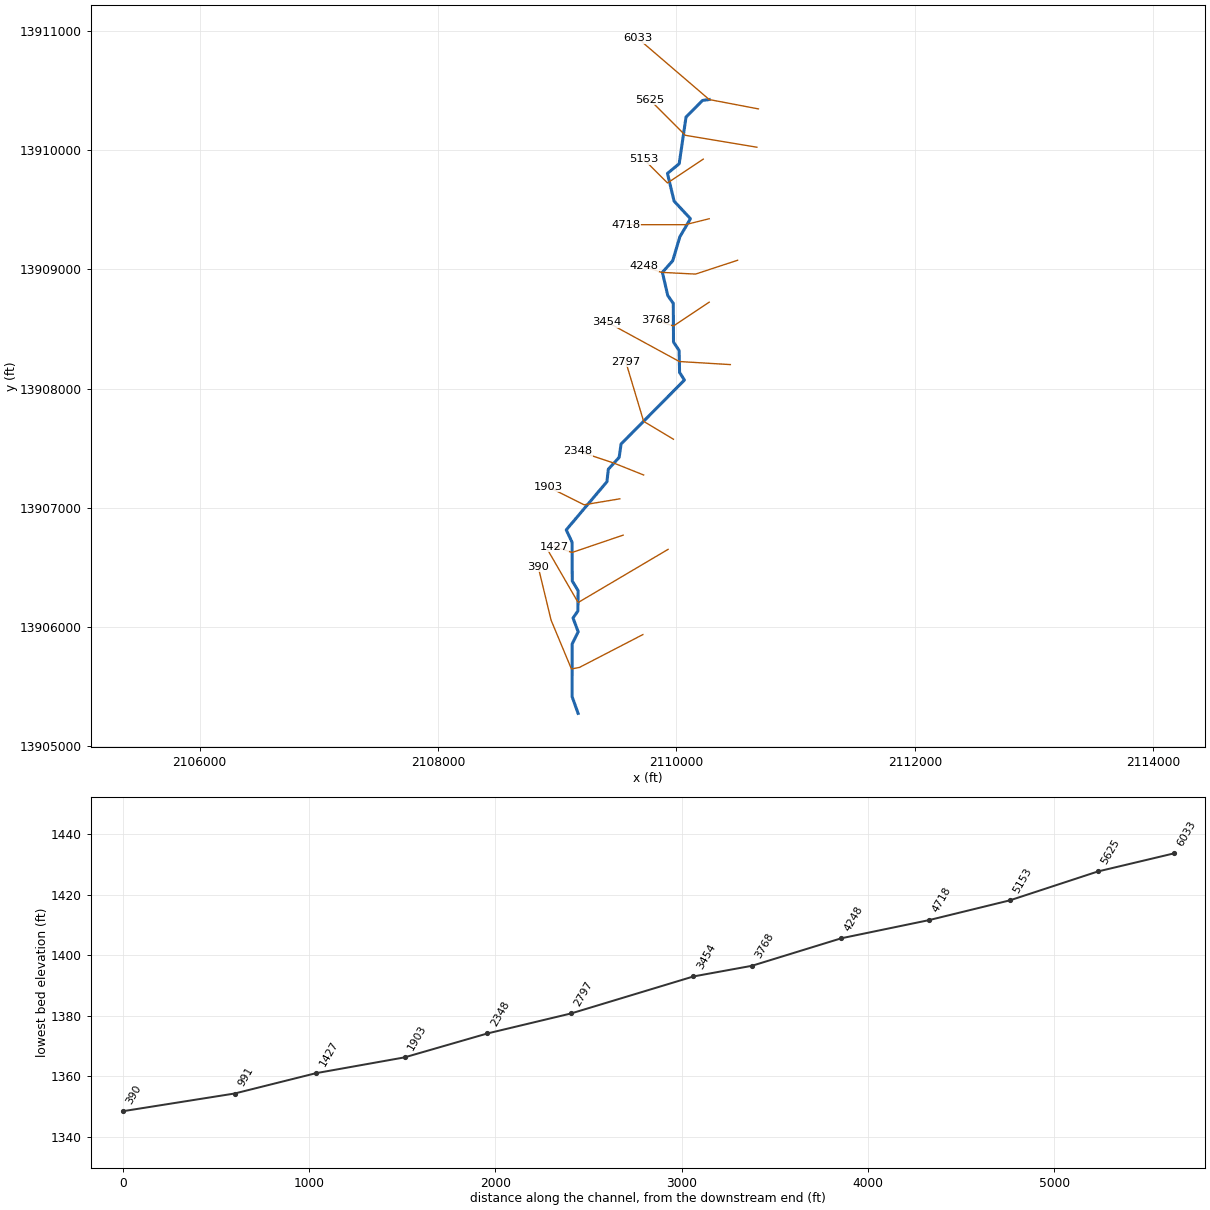
--- Stream0016_DS.prj (project) ---

Proj Title=Stream0016_DS Base Level Engineering
Current Plan=p01
Default Exp/Contr=0.3,0.1
English Units
Geom File=g01
Flow File=f01
Plan File=p01
BEGIN DESCRIPTION:
Stream0016_DS
END DESCRIPTION:

--- Stream0016_DS.p01 (plan) ---

Plan Title=Multiple Run
Short Identifier=Multiple
Geom File=g01
Flow File=f01
Subcritical Flow
K Sum by GR= 0
Std Step Tol= 0.01
Critical Tol= 0.01
Num of Std Step Trials= 20
Max Error Tol= 0.3
Flow Tol Ratio= 0.001
Split Flow NTrial= 30
Split Flow Tol= 0.02
Split Flow Ratio= 0.02
Log Output Level= 0
Friction Slope Method= 1
Unsteady Friction Slope Method= 2
Unsteady Bridges Friction Slope Method= 1
Parabolic Critical Depth
Global Vel Dist=  1 , 1 , 1
Global Log Level= 0
CheckData=True
Encroach Param= -1, 0, 0, 0
BEGIN DESCRIPTION:
Multiple Run
END DESCRIPTION:

--- Stream0016_DS.f01 (steady flow) ---

Flow Title=Multiple
Number of Profiles=7
Profile Names=10-year,25-year,50-year,1pct_min,100-year,1pct_plu,500-year
River Rch & RM= Stream0016_DS,Reach-1,6033
     497     815    1110     738    1472    2938    2556
River Rch & RM= Stream0016_DS,Reach-1,5625
    1315    2283    3230    2218    4425    8830    8210
River Rch & RM= Stream0016_DS,Reach-1,3768
    1478    2572    3644    2503    4995    9966    9280
Boundary for River Rch & Prof#=Stream0016_DS,Reach-1,1
Up Type=0
Dn Type=3
Dn Slope=0.005
Boundary for River Rch & Prof#=Stream0016_DS,Reach-1,2
Up Type=0
Dn Type=3
Dn Slope=0.005
Boundary for River Rch & Prof#=Stream0016_DS,Reach-1,3
Up Type=0
Dn Type=3
Dn Slope=0.005
Boundary for River Rch & Prof#=Stream0016_DS,Reach-1,4
Up Type=0
Dn Type=3
Dn Slope=0.005
Boundary for River Rch & Prof#=Stream0016_DS,Reach-1,5
Up Type=0
Dn Type=3
Dn Slope=0.005
Boundary for River Rch & Prof#=Stream0016_DS,Reach-1,6
Up Type=0
Dn Type=3
Dn Slope=0.005
Boundary for River Rch & Prof#=Stream0016_DS,Reach-1,7
Up Type=0
Dn Type=3
Dn Slope=0.005

--- Stream0016_DS.g01 (geometry) ---

Geom Title=Existing Conditions

River Reach=Stream0016_DS,Reach-1
Reach XY= 30
      2110275.00     13910425.00      2110218.79     13910417.24
      2110080.46     13910277.45      2110023.12     13909886.16
      2109924.76     13909805.05      2109980.52     13909572.57
      2110117.71     13909425.09      2110028.83     13909273.42
      2109969.14     13909072.70      2109882.33     13908975.10
      2109927.39     13908780.53      2109973.78     13908714.50
      2109975.52     13908390.22      2110022.74     13908319.06
      2110026.39     13908135.43      2110067.21     13908071.58
      2109535.52     13907534.79      2109519.46     13907422.58
      2109428.63     13907323.50      2109417.14     13907218.83
      2109075.60     13906814.38      2109124.30     13906711.09
      2109126.22     13906385.50      2109174.93     13906304.97
      2109173.45     13906134.59      2109132.56     13906075.00
      2109175.69     13905959.94      2109125.21     13905856.73
      2109124.54     13905415.72      2109175.00     13905275.00

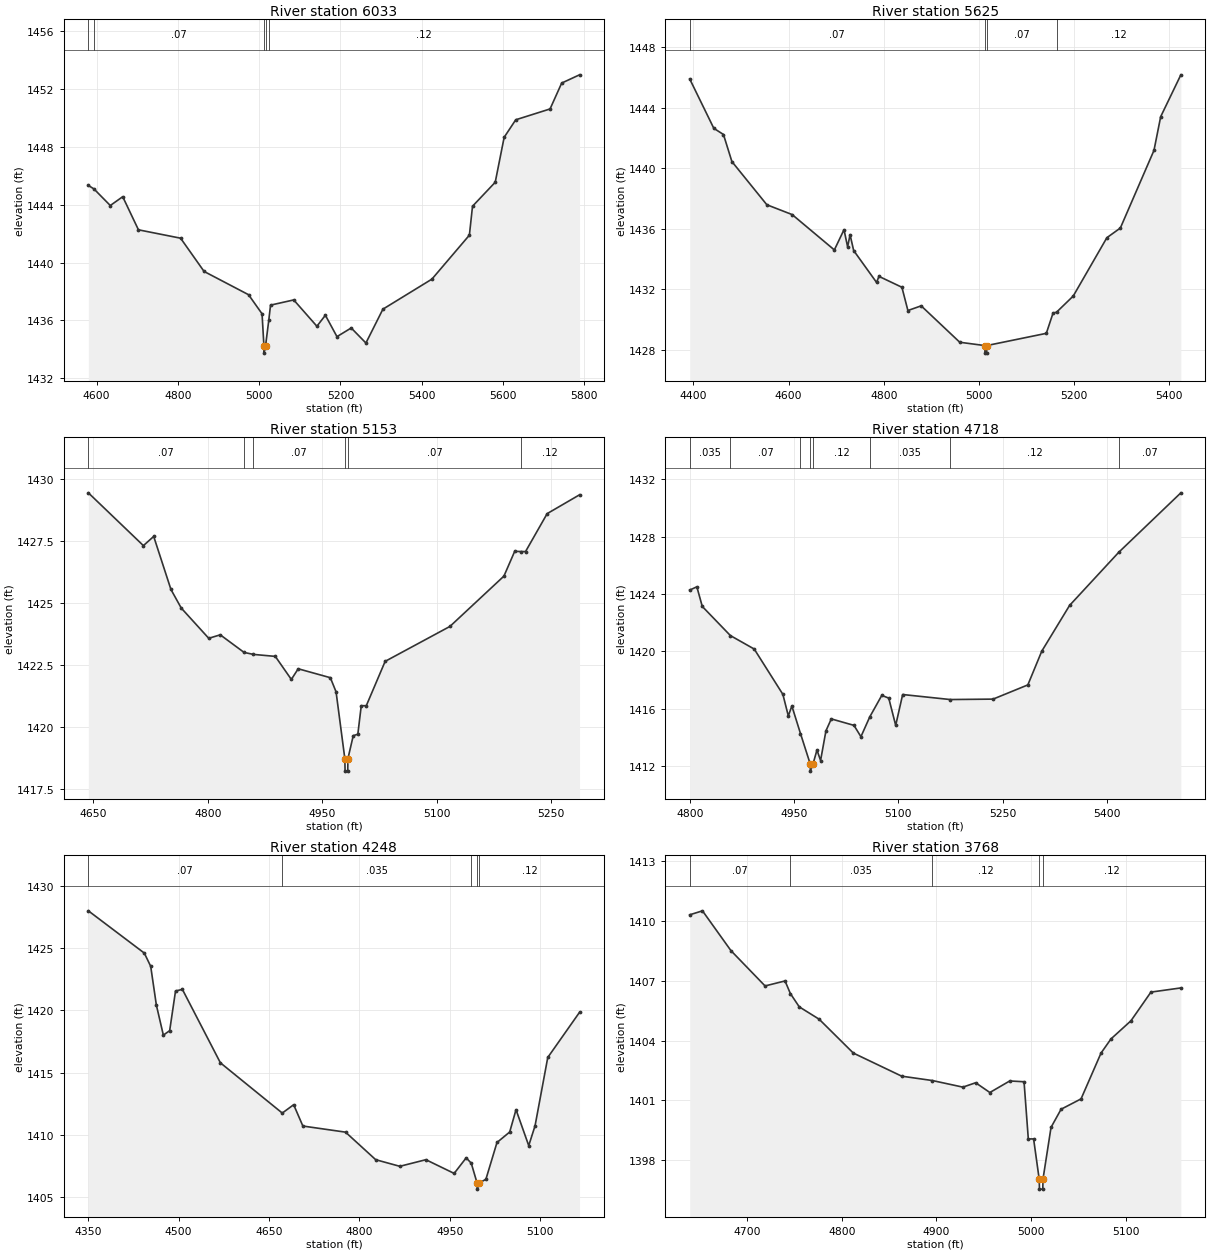
Type RM Length L Ch R = 1,6033,408,408,408
BEGIN DESCRIPTION:
Stream0016_DS 13.0
END DESCRIPTION:
XS GIS Cut Line= 3
      2110688.09     13910346.38      2110275.00     13910425.00
      2109676.45     13910938.45
#Sta/Elev= 30
  4579.5 1445.34  4593.2 1445.10  4633.5 1443.95  4664.1 1444.56  4702.8 1442.27
  4806.6 1441.69  4864.4 1439.39  4973.9 1437.78  5007.1 1436.46  5011.7 1434.24
  5012.0 1433.74  5015.7 1434.24  5023.7 1436.02  5028.0 1437.06  5085.1 1437.42
  5142.1 1435.60  5163.0 1436.36  5191.5 1434.88  5226.6 1435.48  5262.8 1434.44
  5304.6 1436.78  5425.3 1438.86  5517.5 1441.90  5525.2 1443.90  5581.1 1445.56
  5603.1 1448.67  5631.6 1449.88  5716.1 1450.63  5744.7 1452.42  5788.6 1452.99
#Mann=5,-1,0
  4579.5   0.035       0  4593.2    0.07       0  5011.7    0.05       0
  5015.7    0.07       0  5023.7    0.12       0
Bank Sta=5011.7,5015.7
Exp/Cntr=0.3,0.1

Type RM Length L Ch R = 1,5625,472,472,472
BEGIN DESCRIPTION:
Stream0016_DS 12.0
END DESCRIPTION:
XS GIS Cut Line= 3
      2110674.99     13910025.00      2110075.00     13910125.00
      2109775.02     13910424.98
#Sta/Elev= 30
  4392.1 1445.91  4442.8 1442.64  4463.1 1442.23  4480.8 1440.44  4554.3 1437.58
  4607.5 1436.93  4696.2 1434.59  4716.5 1435.93  4724.1 1434.79  4729.2 1435.60
  4736.8 1434.55  4784.9 1432.44  4790.0 1432.84  4838.2 1432.12  4850.8 1430.58
  4878.7 1430.89  4959.8 1428.48  5012.5 1428.26  5012.8 1427.76  5016.3 1427.76
  5016.5 1428.26  5141.8 1429.07  5155.9 1430.41  5163.3 1430.47  5198.4 1431.54
  5269.1 1435.40  5297.4 1436.04  5368.1 1441.18  5382.2 1443.41  5424.6 1446.18
#Mann=4,-1,0
  4392.1    0.07       0  5012.5    0.05       0  5016.5    0.07       0
  5163.3    0.12       0
Bank Sta=5012.5,5016.5
Exp/Cntr=0.3,0.1

Type RM Length L Ch R = 1,5153,435,435,435
BEGIN DESCRIPTION:
Stream0016_DS 11.0
END DESCRIPTION:
XS GIS Cut Line= 3
      2110224.99     13909924.99      2109925.00     13909725.00
      2109724.99     13909925.01
#Sta/Elev= 30
  4643.6 1429.44  4715.7 1427.31  4729.2 1427.68  4751.8 1425.54  4765.3 1424.79
  4801.3 1423.57  4816.4 1423.71  4847.6 1423.00  4859.9 1422.92  4888.5 1422.84
  4909.5 1421.91  4918.5 1422.34  4960.6 1421.98  4968.1 1421.41  4979.6 1418.71
  4979.9 1418.21  4983.4 1418.21  4983.6 1418.71  4990.6 1419.64  4996.6 1419.70
  5001.1 1420.85  5007.7 1420.85  5032.4 1422.64  5117.3 1424.05  5188.0 1426.08
  5202.1 1427.08  5210.5 1427.07  5216.3 1427.07  5244.6 1428.60  5287.0 1429.36
#Mann=6,-1,0
  4643.6    0.07       0  4847.6    0.12       0  4859.9    0.07       0
  4979.6    0.05       0  4983.6    0.07       0  5210.5    0.12       0
Bank Sta=4979.6,4983.6
Exp/Cntr=0.3,0.1

Type RM Length L Ch R = 1,4718,470,470,470
BEGIN DESCRIPTION:
Stream0016_DS 10.0
END DESCRIPTION:
XS GIS Cut Line= 3
      2110275.03     13909425.01      2110075.00     13909375.00
      2109574.99     13909375.00
#Sta/Elev= 30
  4800.0 1424.27  4810.3 1424.50  4818.1 1423.13  4858.5 1421.10  4892.8 1420.16
  4934.0 1417.00  4941.8 1415.50  4946.9 1416.19  4959.3 1414.27  4973.3 1412.15
  4973.5 1411.65  4977.3 1412.15  4983.0 1413.12  4988.2 1412.39  4995.9 1414.46
  5003.6 1415.29  5036.2 1414.84  5046.2 1414.05  5058.9 1415.43  5076.2 1416.93
  5086.2 1416.74  5096.2 1414.84  5106.2 1416.99  5174.7 1416.64  5236.2 1416.67
  5286.2 1417.66  5306.2 1420.01  5346.2 1423.20  5416.8 1426.90  5506.2 1431.05
#Mann=8,-1,0
  4800.0   0.035       0  4858.5    0.07       0  4959.3    0.12       0
  4973.3    0.05       0  4977.3    0.12       0  5058.9   0.035       0
  5174.7    0.12       0  5416.8    0.07       0
Bank Sta=4973.3,4977.3
Exp/Cntr=0.3,0.1

Type RM Length L Ch R = 1,4248,480,480,480
BEGIN DESCRIPTION:
Stream0016_DS 9.0
END DESCRIPTION:
XS GIS Cut Line= 4
      2110513.30     13909076.49      2110160.09     13908960.53
      2109875.00     13908975.00      2109725.03     13909024.99
#Sta/Elev= 30
  4350.2 1427.97  4443.1 1424.58  4453.7 1423.52  4463.1 1420.41  4474.7 1418.00
  4485.2 1418.36  4494.9 1421.54  4506.3 1421.67  4569.4 1415.78  4672.1 1411.75
  4691.0 1412.42  4706.3 1410.71  4777.1 1410.22  4827.2 1408.01  4867.2 1407.48
  4910.5 1408.01  4957.4 1406.91  4977.4 1408.16  4985.8 1407.73  4995.4 1406.15
  4995.7 1405.65  4999.4 1406.15  5010.1 1406.44  5028.5 1409.39  5049.6 1410.23
  5060.1 1412.02  5081.2 1409.14  5091.7 1410.73  5112.8 1416.21  5165.5 1419.83
#Mann=5,-1,0
  4350.2    0.07       0  4672.1   0.035       0  4985.8    0.12       0
  4995.4    0.05       0  4999.4    0.12       0
Bank Sta=4995.4,4999.4
Exp/Cntr=0.3,0.1

Type RM Length L Ch R = 1,3768,314,314,314
BEGIN DESCRIPTION:
Stream0016_DS 8.0
END DESCRIPTION:
XS GIS Cut Line= 3
      2110275.01     13908725.01      2109975.00     13908525.00
      2109824.98     13908575.01
#Sta/Elev= 30
  4639.4 1410.31  4652.9 1410.51  4683.0 1408.51  4719.0 1406.74  4740.1 1406.99
  4745.7 1406.36  4755.1 1405.69  4776.1 1405.07  4812.2 1403.37  4863.3 1402.21
  4895.8 1401.99  4927.9 1401.66  4941.4 1401.88  4956.4 1401.39  4977.4 1401.97
  4992.5 1401.93  4997.0 1399.06  5002.6 1399.06  5008.5 1397.04  5008.8 1396.54
  5012.3 1396.54  5012.5 1397.04  5021.0 1399.64  5031.6 1400.55  5052.7 1401.07
  5073.8 1403.37  5084.3 1404.08  5105.4 1404.99  5126.5 1406.43  5158.1 1406.64
#Mann=5,-1,0
  4639.4    0.07       0  4745.7   0.035       0  4895.8    0.12       0
  5008.5    0.05       0  5012.5    0.12       0
Bank Sta=5008.5,5012.5
Exp/Cntr=0.3,0.1

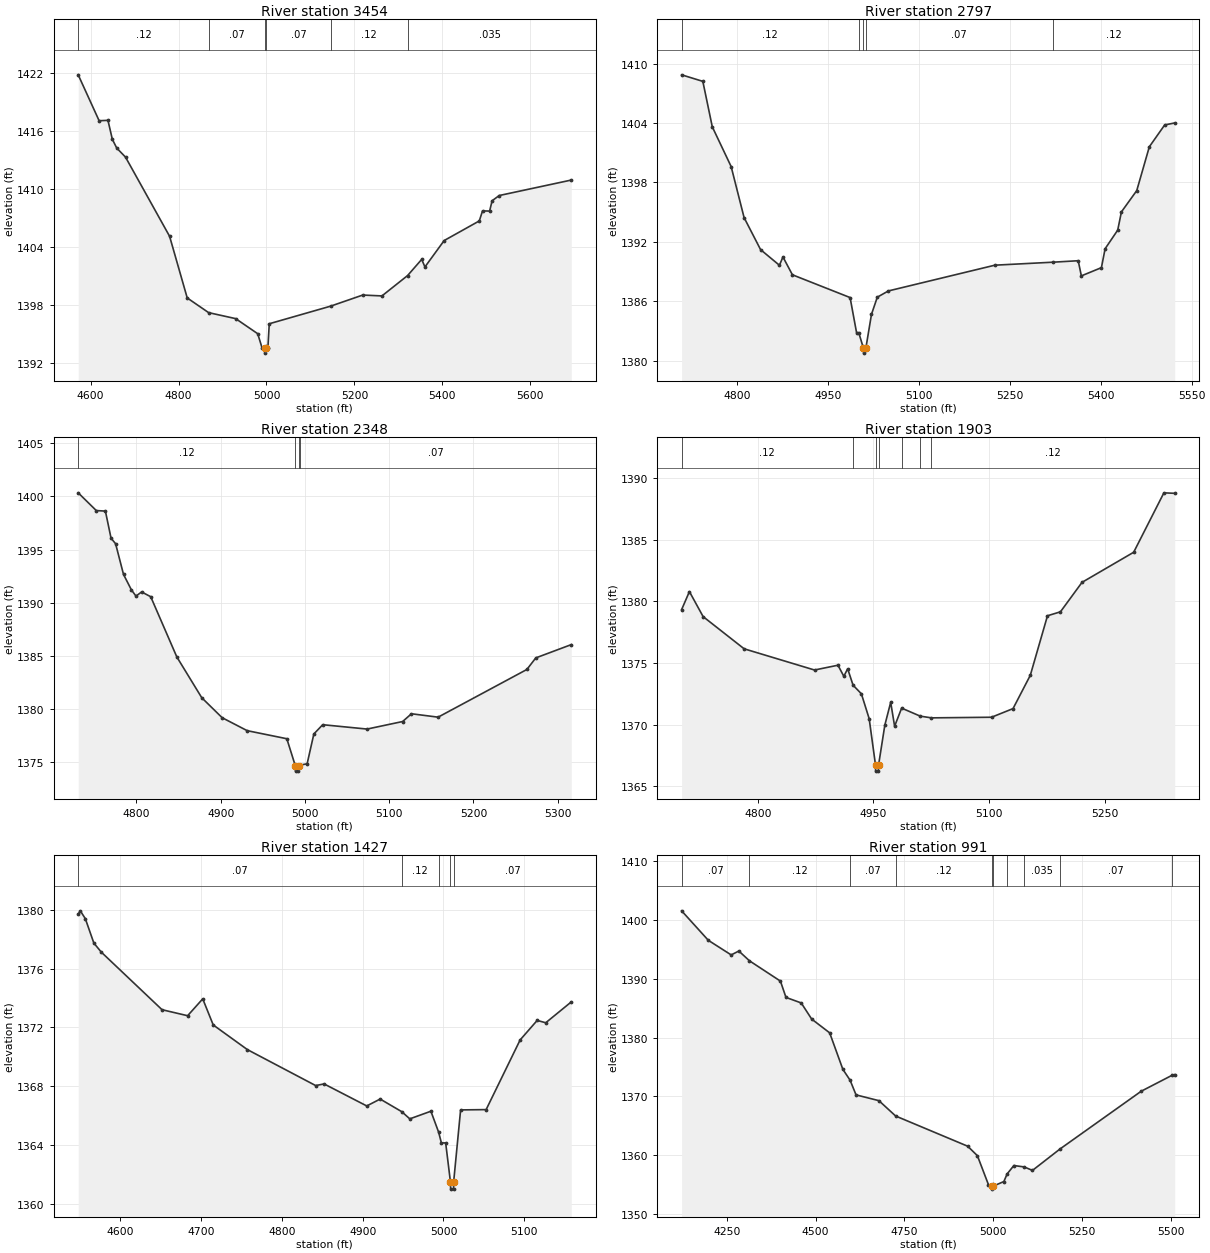
Type RM Length L Ch R = 1,3454,657,657,657
BEGIN DESCRIPTION:
Stream0016_DS 7.0
END DESCRIPTION:
XS GIS Cut Line= 3
      2110452.55     13908201.16      2110024.47     13908226.95
      2109416.34     13908558.51
#Sta/Elev= 30
  4571.7 1421.81  4619.3 1417.06  4639.4 1417.10  4649.4 1415.13  4659.4 1414.23
  4679.4 1413.29  4779.6 1405.10  4819.7 1398.72  4868.4 1397.20  4929.9 1396.58
  4980.0 1395.02  4990.0 1393.54  4995.8 1393.51  4996.0 1393.01  4999.8 1393.51
  5003.1 1393.51  5006.3 1396.05  5145.8 1397.87  5218.9 1399.02  5262.6 1398.93
  5321.0 1401.04  5353.0 1402.71  5360.4 1401.93  5404.1 1404.66  5484.0 1406.69
  5491.4 1407.73  5507.5 1407.71  5513.2 1408.78  5529.4 1409.32  5693.2 1410.92
#Mann=6,-1,0
  4571.7    0.12       0  4868.4    0.07       0  4995.8    0.05       0
  4999.8    0.07       0  5145.8    0.12       0  5321.0   0.035       0
Bank Sta=4995.8,4999.8
Exp/Cntr=0.3,0.1

Type RM Length L Ch R = 1,2797,449,449,449
BEGIN DESCRIPTION:
Stream0016_DS 6.0
END DESCRIPTION:
XS GIS Cut Line= 3
      2109975.04     13907574.98      2109725.00     13907725.00
      2109575.00     13908224.99
#Sta/Elev= 30
  4708.4 1408.86  4743.4 1408.20  4759.0 1403.61  4790.1 1399.60  4811.5 1394.44
  4838.7 1391.21  4869.8 1389.63  4875.6 1390.47  4891.2 1388.67  4986.4 1386.37
  4997.1 1382.82  5000.7 1382.82  5008.4 1381.26  5008.7 1380.76  5012.4 1381.26
  5021.7 1384.68  5031.3 1386.41  5049.6 1387.04  5225.3 1389.64  5320.7 1389.94
  5362.8 1390.09  5368.0 1388.56  5401.1 1389.39  5407.2 1391.30  5428.0 1393.18
  5434.1 1395.02  5459.4 1397.17  5480.2 1401.60  5505.5 1403.80  5522.0 1404.00
#Mann=5,-1,0
  4708.4    0.12       0  5000.7    0.07       0  5008.4    0.05       0
  5012.4    0.07       0  5320.7    0.12       0
Bank Sta=5008.4,5012.4
Exp/Cntr=0.3,0.1

Type RM Length L Ch R = 1,2348,445,445,445
BEGIN DESCRIPTION:
Stream0016_DS 5.0
END DESCRIPTION:
XS GIS Cut Line= 3
      2109724.96     13907275.02      2109475.00     13907375.00
      2109175.04     13907474.99
#Sta/Elev= 30
  4730.8 1400.34  4752.3 1398.67  4763.1 1398.62  4769.8 1396.07  4775.2 1395.55
  4784.6 1392.66  4794.0 1391.20  4799.4 1390.62  4806.1 1391.01  4816.9 1390.56
  4847.9 1384.89  4877.5 1381.05  4901.7 1379.17  4931.4 1377.95  4978.5 1377.19
  4988.6 1374.64  4988.8 1374.14  4992.3 1374.14  4992.6 1374.64  4994.3 1374.71
  5002.6 1374.83  5010.6 1377.64  5021.1 1378.51  5073.8 1378.10  5116.0 1378.81
  5126.5 1379.54  5158.1 1379.22  5263.5 1383.71  5274.1 1384.80  5316.2 1386.05
#Mann=4,-1,0
  4730.8    0.12       0  4988.6    0.05       0  4992.6    0.12       0
  4994.3    0.07       0
Bank Sta=4988.6,4992.6
Exp/Cntr=0.3,0.1

Type RM Length L Ch R = 1,1903,476,476,476
BEGIN DESCRIPTION:
Stream0016_DS 4.0
END DESCRIPTION:
XS GIS Cut Line= 3
      2109525.01     13907075.00      2109225.00     13907025.00
      2108924.96     13907175.02
#Sta/Elev= 30
  4701.1 1379.32  4711.2 1380.78  4729.0 1378.75  4782.2 1376.14  4873.5 1374.42
  4903.9 1374.81  4911.5 1373.91  4916.5 1374.52  4923.5 1373.19  4934.3 1372.49
  4944.4 1370.47  4952.6 1366.72  4952.8 1366.22  4956.3 1366.22  4956.6 1366.72
  4964.7 1369.95  4972.3 1371.80  4977.4 1369.86  4986.5 1371.33  5010.6 1370.68
  5025.2 1370.54  5103.1 1370.59  5131.0 1371.29  5153.4 1373.99  5175.7 1378.82
  5192.5 1379.14  5220.5 1381.53  5287.5 1383.97  5326.7 1388.79  5340.7 1388.75
#Mann=7,-1,0
  4701.1    0.12       0  4923.5    0.07       0  4952.6    0.05       0
  4956.6    0.07       0  4986.5    0.12       0  5010.6    0.07       0
  5025.2    0.12       0
Bank Sta=4952.6,4956.6
Exp/Cntr=0.3,0.1

Type RM Length L Ch R = 1,1427,436,436,436
BEGIN DESCRIPTION:
Stream0016_DS 3.0
END DESCRIPTION:
XS GIS Cut Line= 3
      2109553.33     13906770.54      2109125.00     13906625.00
      2108974.99     13906675.00
#Sta/Elev= 30
  4547.7 1379.72  4550.3 1379.95  4556.5 1379.42  4567.1 1377.75  4576.4 1377.13
  4651.5 1373.21  4683.2 1372.80  4701.9 1373.95  4714.9 1372.17  4757.2 1370.49
  4841.7 1368.04  4852.2 1368.15  4905.0 1366.65  4921.6 1367.12  4948.3 1366.26
  4958.3 1365.77  4984.4 1366.29  4994.0 1364.86  4997.4 1364.13  5002.7 1364.13
  5008.6 1361.48  5008.9 1360.98  5012.4 1360.98  5012.6 1361.48  5021.2 1366.38
  5052.8 1366.40  5094.9 1371.15  5116.0 1372.48  5126.6 1372.32  5158.2 1373.74
#Mann=5,-1,0
  4547.7    0.07       0  4948.3    0.12       0  4994.0    0.07       0
  5008.6    0.05       0  5012.6    0.07       0
Bank Sta=5008.6,5012.6
Exp/Cntr=0.3,0.1

Type RM Length L Ch R = 1,991,601,601,601
BEGIN DESCRIPTION:
Stream0016_DS 2.0
END DESCRIPTION:
XS GIS Cut Line= 3
      2109929.94     13906650.99      2109175.19     13906204.94
      2108920.04     13906646.64
#Sta/Elev= 30
  4123.3 1401.54  4198.4 1396.53  4262.7 1394.05  4284.2 1394.71  4314.1 1393.05
  4401.2 1389.60  4416.8 1386.83  4459.7 1385.89  4489.1 1383.15  4539.7 1380.81
  4576.8 1374.61  4597.1 1372.77  4613.9 1370.27  4678.2 1369.29  4725.3 1366.68
  4927.9 1361.55  4955.2 1359.94  4986.4 1355.00  4995.2 1354.76  4995.5 1354.26
  4999.2 1354.76  5029.7 1355.55  5038.8 1356.84  5057.8 1358.27  5086.8 1358.03
  5110.1 1357.44  5187.8 1361.09  5415.9 1370.89  5503.0 1373.61  5510.1 1373.72
#Mann=10,-1,0
  4123.3    0.07       0  4314.1    0.12       0  4597.1    0.07       0
  4725.3    0.12       0  4995.2    0.05       0  4999.2    0.12       0
  5038.8    0.07       0  5086.8   0.035       0  5187.8    0.07       0
  5503.0    0.12       0
Bank Sta=4995.2,4999.2
Exp/Cntr=0.3,0.1

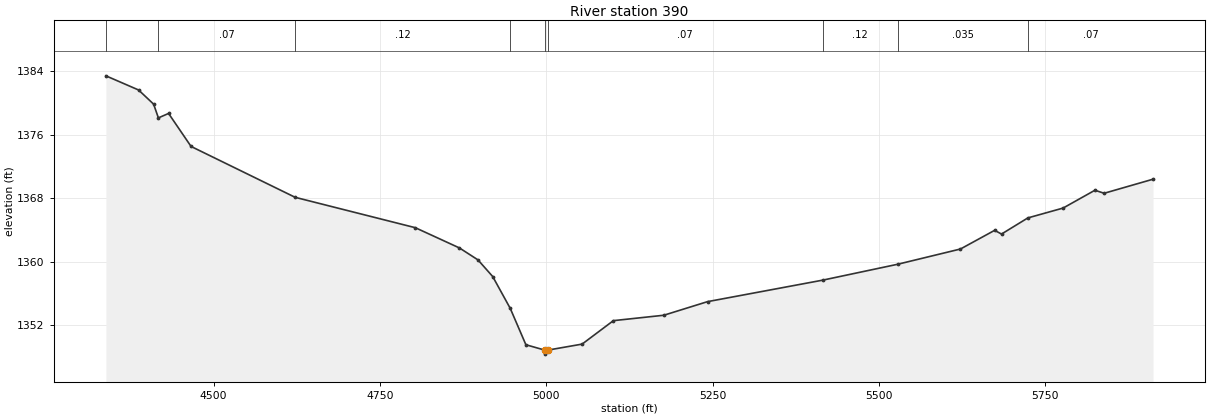
Type RM Length L Ch R = 1,390,0,0,0
BEGIN DESCRIPTION:
Stream0016_DS 1.0
END DESCRIPTION:
XS GIS Cut Line= 5
      2109718.65     13905936.10      2109186.66     13905660.71
      2109119.10     13905647.41      2108948.28     13906057.58
      2108839.84     13906506.45
#Sta/Elev= 30
  4338.1 1383.39  4387.2 1381.61  4409.8 1379.83  4417.0 1378.10  4432.3 1378.66
  4466.1 1374.51  4622.6 1368.11  4803.2 1364.29  4869.6 1361.74  4897.4 1360.24
  4919.5 1358.15  4945.9 1354.14  4969.4 1349.57  4998.0 1348.89  4998.2 1348.39
  5002.0 1348.89  5053.9 1349.65  5100.9 1352.60  5176.7 1353.28  5242.4 1354.99
  5415.9 1357.70  5528.1 1359.69  5622.6 1361.61  5674.0 1363.96  5684.3 1363.49
  5723.9 1365.52  5776.9 1366.76  5824.7 1369.00  5838.6 1368.62  5912.1 1370.39
#Mann=9,-1,0
  4338.1    0.12       0  4417.0    0.07       0  4622.6    0.12       0
  4945.9    0.07       0  4998.0    0.05       0  5002.0    0.07       0
  5415.9    0.12       0  5528.1   0.035       0  5723.9    0.07       0
Bank Sta=4998,5002
Exp/Cntr=0.3,0.1

Chan Stop Cuts=-1