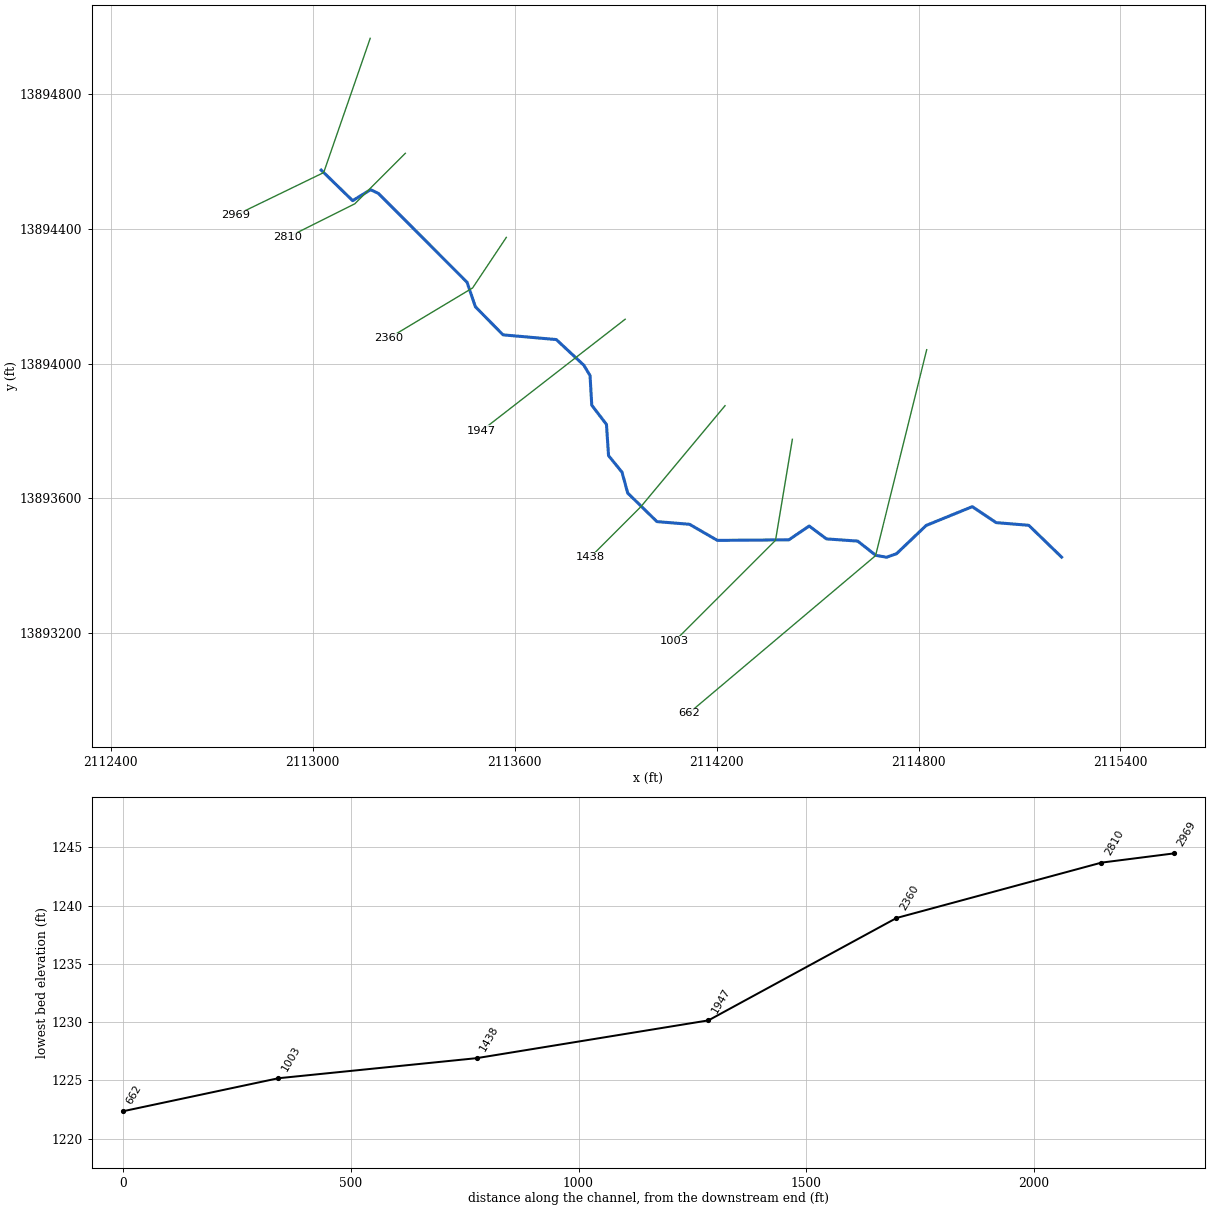
--- Stream0017_DS.prj (project) ---

Proj Title=Stream0017_DS Base Level Engineering
Current Plan=p01
Default Exp/Contr=0.3,0.1
English Units
Geom File=g01
Flow File=f01
Plan File=p01
BEGIN DESCRIPTION:
Stream0017_DS
END DESCRIPTION:

--- Stream0017_DS.p01 (plan) ---

Plan Title=Multiple Run
Short Identifier=Multiple
Geom File=g01
Flow File=f01
Subcritical Flow
K Sum by GR= 0
Std Step Tol= 0.01
Critical Tol= 0.01
Num of Std Step Trials= 20
Max Error Tol= 0.3
Flow Tol Ratio= 0.001
Split Flow NTrial= 30
Split Flow Tol= 0.02
Split Flow Ratio= 0.02
Log Output Level= 0
Friction Slope Method= 1
Unsteady Friction Slope Method= 2
Unsteady Bridges Friction Slope Method= 1
Parabolic Critical Depth
Global Vel Dist=  1 , 1 , 1
Global Log Level= 0
CheckData=True
Encroach Param= -1, 0, 0, 0
BEGIN DESCRIPTION:
Multiple Run
END DESCRIPTION:

--- Stream0017_DS.f01 (steady flow) ---

Flow Title=Multiple
Number of Profiles=7
Profile Names=10-year,25-year,50-year,1pct_min,100-year,1pct_plu,500-year
River Rch & RM= Stream0017_DS,Reach-1,2969
     884    1467    2011    1337    2668    5323    4638
Boundary for River Rch & Prof#=Stream0017_DS,Reach-1,1
Up Type=0
Dn Type=3
Dn Slope=0.005
Boundary for River Rch & Prof#=Stream0017_DS,Reach-1,2
Up Type=0
Dn Type=3
Dn Slope=0.005
Boundary for River Rch & Prof#=Stream0017_DS,Reach-1,3
Up Type=0
Dn Type=3
Dn Slope=0.005
Boundary for River Rch & Prof#=Stream0017_DS,Reach-1,4
Up Type=0
Dn Type=3
Dn Slope=0.005
Boundary for River Rch & Prof#=Stream0017_DS,Reach-1,5
Up Type=0
Dn Type=3
Dn Slope=0.005
Boundary for River Rch & Prof#=Stream0017_DS,Reach-1,6
Up Type=0
Dn Type=3
Dn Slope=0.005
Boundary for River Rch & Prof#=Stream0017_DS,Reach-1,7
Up Type=0
Dn Type=3
Dn Slope=0.005

--- Stream0017_DS.g01 (geometry) ---

Geom Title=Existing Conditions

River Reach=Stream0017_DS,Reach-1
Reach XY= 30
      2113025.00     13894575.00      2113118.33     13894484.17
      2113171.67     13894516.85      2113195.00     13894505.63
      2113458.35     13894241.67      2113483.15     13894168.93
      2113565.18     13894085.47      2113723.54     13894071.46
      2113805.39     13893995.20      2113823.84     13893964.53
      2113828.86     13893876.60      2113872.65     13893819.03
      2113878.82     13893726.58      2113918.86     13893677.17
      2113935.75     13893615.29      2114022.56     13893530.52
      2114119.43     13893522.53      2114202.15     13893474.72
      2114414.56     13893476.38      2114475.00     13893517.44
      2114526.50     13893479.09      2114619.03     13893472.62
      2114672.83     13893430.35      2114704.87     13893424.61
      2114734.67     13893435.21      2114822.71     13893519.16
      2114959.60     13893574.92      2115030.56     13893527.50
      2115127.45     13893519.54      2115225.00     13893425.00

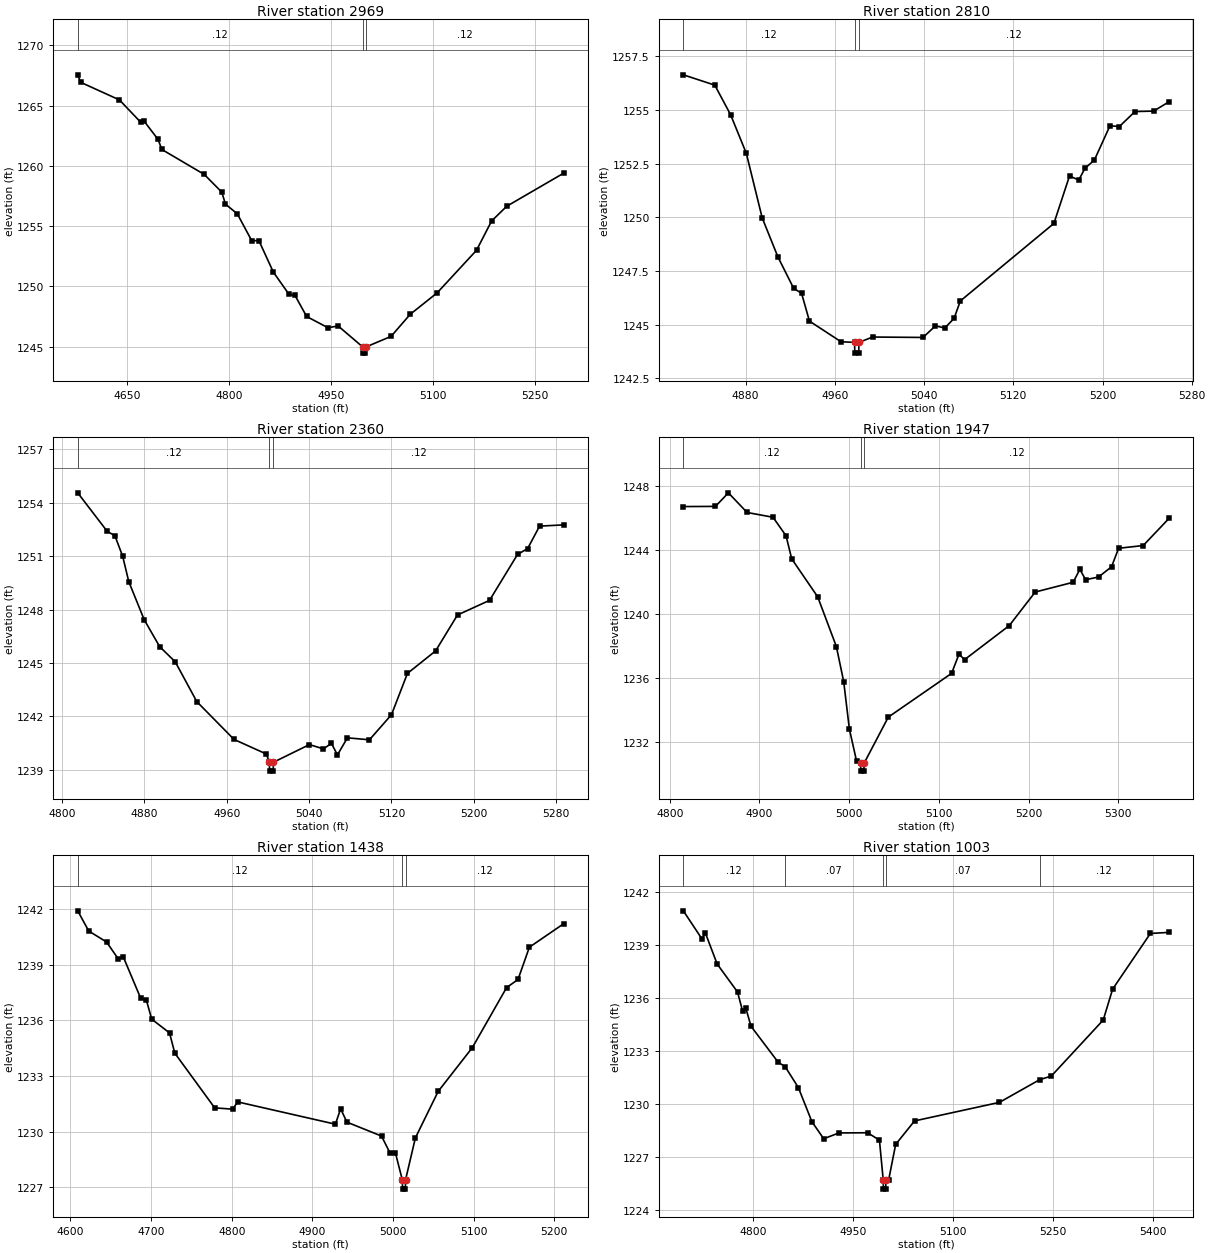
Type RM Length L Ch R = 1,2969,159,159,159
BEGIN DESCRIPTION:
Stream0017_DS 6.0
END DESCRIPTION:
XS GIS Cut Line= 3
      2113170.56     13894966.56      2113032.29     13894567.65
      2112769.90     13894440.43
#Sta/Elev= 30
  4577.8 1267.55  4582.1 1266.93  4639.1 1265.47  4670.3 1263.62  4675.6 1263.69
  4695.9 1262.19  4701.4 1261.36  4763.7 1259.29  4789.5 1257.82  4794.8 1256.83
  4812.3 1256.02  4833.5 1253.79  4844.0 1253.80  4865.2 1251.19  4888.3 1249.34
  4897.0 1249.26  4914.1 1247.51  4945.3 1246.58  4960.5 1246.72  4996.8 1244.97
  4997.0 1244.47  5000.5 1244.47  5000.8 1244.97  5038.2 1245.86  5066.3 1247.69
  5105.9 1249.47  5163.7 1253.00  5185.9 1255.43  5208.1 1256.65  5291.6 1259.39
#Mann=3,-1,0
  4577.8    0.12       0  4996.8    0.05       0  5000.8    0.12       0
Bank Sta=4996.8,5000.8
Exp/Cntr=0.3,0.1

Type RM Length L Ch R = 1,2810,450,450,450
BEGIN DESCRIPTION:
Stream0017_DS 5.0
END DESCRIPTION:
XS GIS Cut Line= 3
      2113274.97     13894624.97      2113125.00     13894475.00
      2112925.00     13894375.00
#Sta/Elev= 30
  4824.1 1256.64  4852.3 1256.16  4866.5 1254.78  4880.6 1252.98  4894.8 1249.98
  4908.9 1248.16  4923.1 1246.69  4930.1 1246.47  4937.2 1245.17  4965.5 1244.21
  4977.6 1244.18  4977.9 1243.68  4981.4 1243.68  4981.6 1244.18  4993.8 1244.43
  5039.0 1244.41  5050.2 1244.95  5058.6 1244.85  5066.9 1245.30  5072.5 1246.11
  5156.4 1249.72  5170.4 1251.93  5178.7 1251.74  5184.3 1252.29  5192.7 1252.67
  5206.7 1254.27  5215.1 1254.23  5229.1 1254.93  5245.8 1254.95  5259.8 1255.39
#Mann=3,-1,0
  4824.1    0.12       0  4977.6    0.05       0  4981.6    0.12       0
Bank Sta=4977.6,4981.6
Exp/Cntr=0.3,0.1

Type RM Length L Ch R = 1,2360,413,413,413
BEGIN DESCRIPTION:
Stream0017_DS 4.0
END DESCRIPTION:
XS GIS Cut Line= 3
      2113575.01     13894375.02      2113475.00     13894225.00
      2113225.04     13894075.03
#Sta/Elev= 30
  4815.3 1254.56  4843.9 1252.40  4851.4 1252.15  4858.9 1251.01  4864.9 1249.57
  4879.9 1247.43  4894.9 1245.92  4910.0 1245.07  4931.0 1242.83  4967.1 1240.71
  4998.5 1239.89  5001.4 1239.43  5001.6 1238.93  5005.1 1238.93  5005.4 1239.43
  5040.3 1240.42  5053.9 1240.18  5061.7 1240.49  5067.5 1239.84  5077.2 1240.80
  5098.6 1240.69  5120.0 1242.10  5135.5 1244.42  5162.8 1245.68  5184.1 1247.70
  5215.2 1248.52  5242.4 1251.10  5252.2 1251.43  5263.8 1252.69  5287.1 1252.76
#Mann=3,-1,0
  4815.3    0.12       0  5001.4    0.05       0  5005.4    0.12       0
Bank Sta=5001.4,5005.4
Exp/Cntr=0.3,0.1

Type RM Length L Ch R = 1,1947,509,509,509
BEGIN DESCRIPTION:
Stream0017_DS 3.1
END DESCRIPTION:
XS GIS Cut Line= 2
      2113928.24     13894131.93      2113500.43     13893799.65
#Sta/Elev= 30
  4815.1 1246.71  4850.9 1246.72  4865.3 1247.57  4886.2 1246.34  4915.1 1246.04
  4929.6 1244.88  4935.9 1243.44  4964.9 1241.06  4985.7 1237.95  4993.9 1235.75
  5000.2 1232.79  5008.3 1230.76  5012.7 1230.65  5012.9 1230.15  5016.4 1230.15
  5016.7 1230.65  5043.6 1233.53  5114.2 1236.27  5122.4 1237.47  5128.7 1237.13
  5178.5 1239.26  5207.4 1241.36  5249.7 1241.97  5257.2 1242.78  5263.6 1242.13
  5278.0 1242.30  5292.5 1242.94  5300.4 1244.10  5327.8 1244.27  5356.8 1245.98
#Mann=3,-1,0
  4815.1    0.12       0  5012.7    0.05       0  5016.7    0.12       0
Bank Sta=5012.7,5016.7
Exp/Cntr=0.3,0.1

Type RM Length L Ch R = 1,1438,435,435,435
BEGIN DESCRIPTION:
Stream0017_DS 3.0
END DESCRIPTION:
XS GIS Cut Line= 3
      2114224.99     13893874.99      2113975.00     13893575.00
      2113825.02     13893425.02
#Sta/Elev= 30
  4609.0 1241.91  4622.7 1240.82  4644.8 1240.23  4659.1 1239.33  4665.6 1239.42
  4687.1 1237.20  4694.2 1237.09  4700.8 1236.07  4722.9 1235.33  4729.4 1234.24
  4778.9 1231.29  4801.0 1231.22  4807.5 1231.61  4928.6 1230.41  4935.1 1231.24
  4942.9 1230.52  4985.8 1229.77  4996.2 1228.87  5003.0 1228.87  5011.6 1227.41
  5011.9 1226.91  5015.4 1226.91  5015.6 1227.41  5027.8 1229.67  5056.1 1232.18
  5098.5 1234.54  5140.9 1237.77  5155.1 1238.21  5169.2 1239.95  5211.6 1241.21
#Mann=3,-1,0
  4609.0    0.12       0  5011.6    0.05       0  5015.6    0.12       0
Bank Sta=5011.6,5015.6
Exp/Cntr=0.3,0.1

Type RM Length L Ch R = 1,1003,341,341,341
BEGIN DESCRIPTION:
Stream0017_DS 2.0
END DESCRIPTION:
XS GIS Cut Line= 3
      2114425.01     13893775.05      2114375.00     13893475.00
      2114075.03     13893175.03
#Sta/Elev= 30
  4695.3 1240.94  4723.2 1239.35  4728.3 1239.69  4746.0 1237.93  4776.5 1236.35
  4784.1 1235.27  4789.1 1235.42  4796.7 1234.41  4837.3 1232.38  4848.1 1232.11
  4867.7 1230.94  4888.0 1229.01  4905.7 1228.04  4928.5 1228.37  4971.6 1228.38
  4989.3 1227.96  4995.0 1225.69  4995.2 1225.19  4998.7 1225.19  4999.0 1225.69
  5003.0 1225.69  5013.6 1227.72  5041.9 1229.05  5169.2 1230.10  5229.3 1231.38
  5247.0 1231.59  5324.8 1234.76  5338.9 1236.51  5395.5 1239.66  5423.7 1239.72
#Mann=5,-1,0
  4695.3    0.12       0  4848.1    0.07       0  4995.0    0.05       0
  4999.0    0.07       0  5229.3    0.12       0
Bank Sta=4995,4999
Exp/Cntr=0.3,0.1

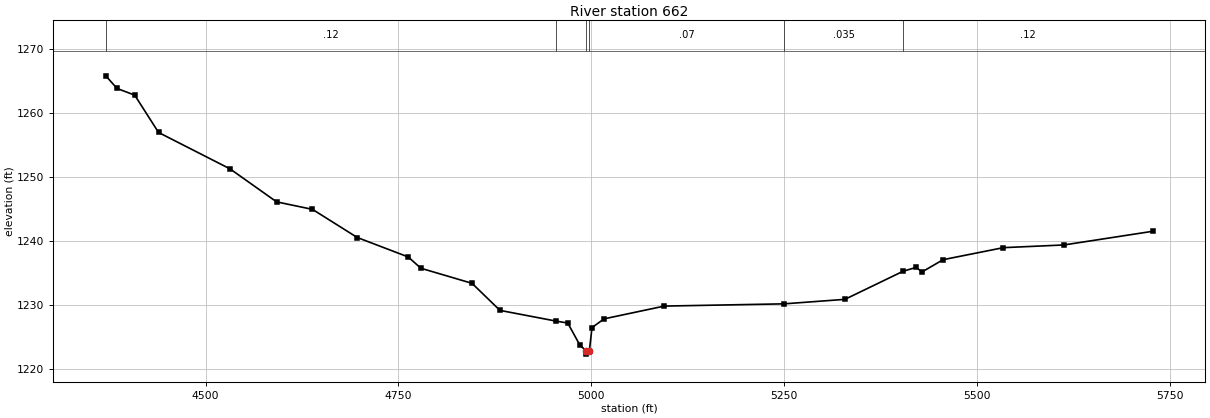
Type RM Length L Ch R = 1,662,0,0,0
BEGIN DESCRIPTION:
Stream0017_DS 1.0
END DESCRIPTION:
XS GIS Cut Line= 3
      2114824.20     13894041.38      2114672.29     13893429.41
      2114116.76     13892960.68
#Sta/Elev= 30
  4370.6 1265.75  4385.2 1263.78  4408.1 1262.74  4439.0 1256.92  4531.7 1251.24
  4592.0 1246.10  4638.5 1244.93  4696.6 1240.54  4762.6 1237.51  4779.0 1235.75
  4845.3 1233.40  4881.5 1229.18  4954.6 1227.50  4969.4 1227.21  4985.1 1223.76
  4993.4 1222.86  4993.6 1222.36  4997.4 1222.86  5000.8 1226.50  5016.5 1227.86
  5094.5 1229.85  5249.8 1230.20  5328.6 1230.90  5404.0 1235.28  5420.9 1235.88
  5428.6 1235.18  5456.0 1237.09  5534.0 1238.96  5612.5 1239.38  5728.0 1241.52
#Mann=6,-1,0
  4370.6    0.12       0  4954.6    0.07       0  4993.4    0.05       0
  4997.4    0.07       0  5249.8   0.035       0  5404.0    0.12       0
Bank Sta=4993.4,4997.4
Exp/Cntr=0.3,0.1

Chan Stop Cuts=-1