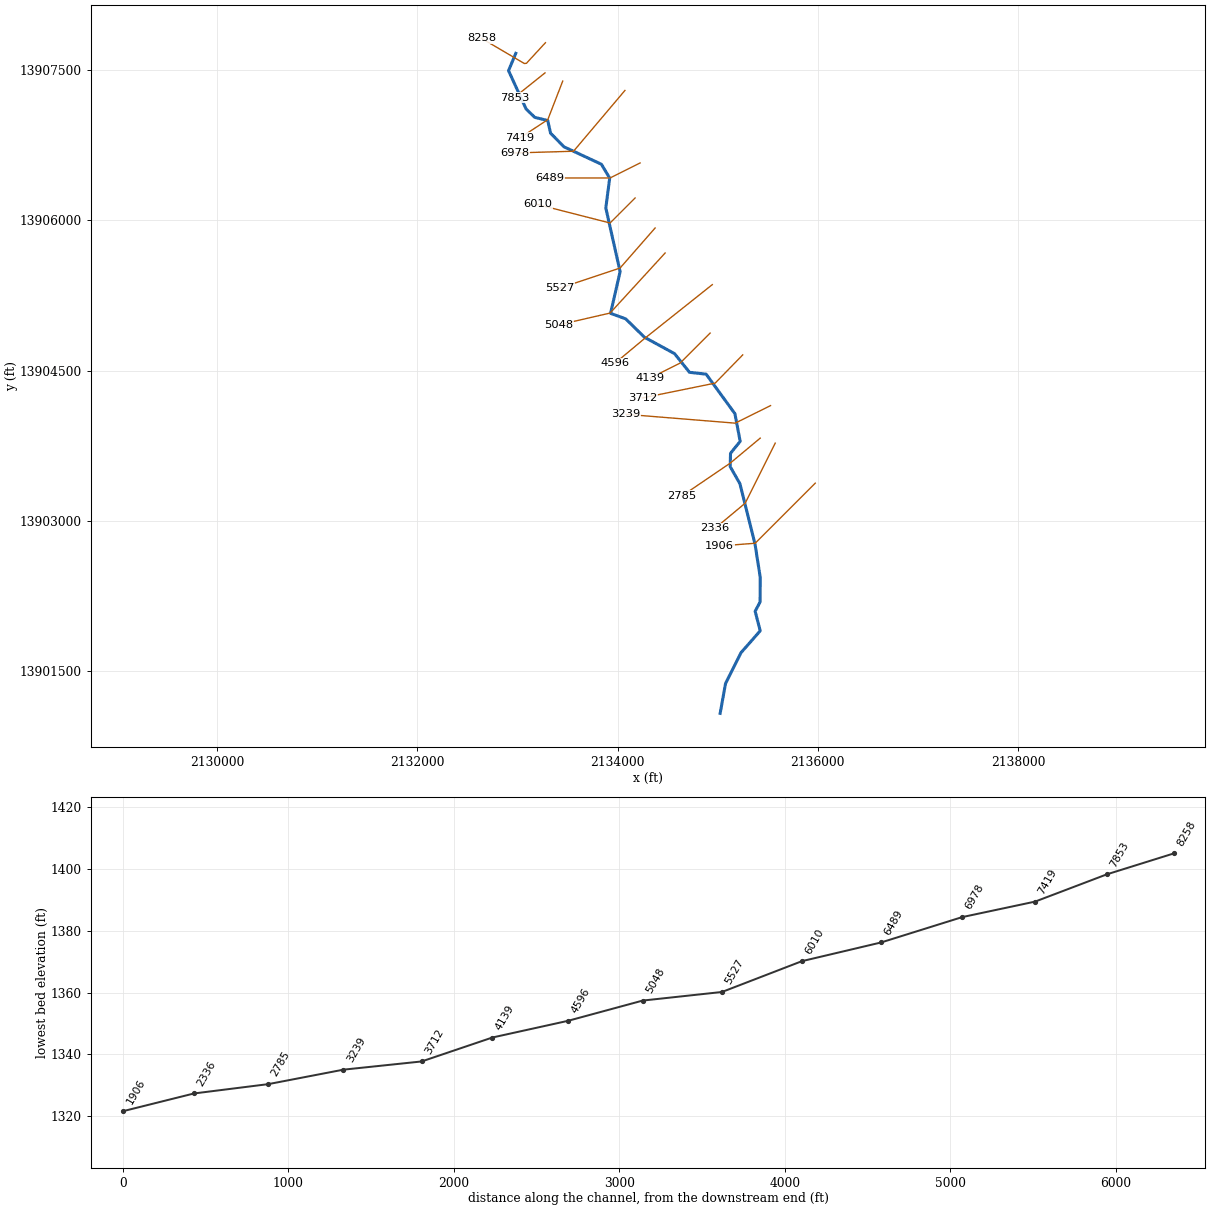
--- Stream0039_DS.prj (project) ---

Proj Title=Stream0039_DS Base Level Engineering
Current Plan=p01
Default Exp/Contr=0.3,0.1
English Units
Geom File=g01
Flow File=f01
Plan File=p01
BEGIN DESCRIPTION:
Stream0039_DS
END DESCRIPTION:

--- Stream0039_DS.p01 (plan) ---

Plan Title=Multiple Run
Short Identifier=Multiple
Geom File=g01
Flow File=f01
Subcritical Flow
K Sum by GR= 0
Std Step Tol= 0.01
Critical Tol= 0.01
Num of Std Step Trials= 20
Max Error Tol= 0.3
Flow Tol Ratio= 0.001
Split Flow NTrial= 30
Split Flow Tol= 0.02
Split Flow Ratio= 0.02
Log Output Level= 0
Friction Slope Method= 1
Unsteady Friction Slope Method= 2
Unsteady Bridges Friction Slope Method= 1
Parabolic Critical Depth
Global Vel Dist=  1 , 1 , 1
Global Log Level= 0
CheckData=True
Encroach Param= -1, 0, 0, 0
BEGIN DESCRIPTION:
Multiple Run
END DESCRIPTION:

--- Stream0039_DS.f01 (steady flow) ---

Flow Title=Multiple
Number of Profiles=7
Profile Names=10-year,25-year,50-year,1pct_min,100-year,1pct_plu,500-year
River Rch & RM= Stream0039_DS,Reach-1,8258
     499     808    1090     716    1429    2852    2422
River Rch & RM= Stream0039_DS,Reach-1,7853
     874    1463    2019    1352    2698    5382    4759
River Rch & RM= Stream0039_DS,Reach-1,4139
    1170    1988    2768    1868    3728    7438    6685
Boundary for River Rch & Prof#=Stream0039_DS,Reach-1,1
Up Type=0
Dn Type=3
Dn Slope=0.005
Boundary for River Rch & Prof#=Stream0039_DS,Reach-1,2
Up Type=0
Dn Type=3
Dn Slope=0.005
Boundary for River Rch & Prof#=Stream0039_DS,Reach-1,3
Up Type=0
Dn Type=3
Dn Slope=0.005
Boundary for River Rch & Prof#=Stream0039_DS,Reach-1,4
Up Type=0
Dn Type=3
Dn Slope=0.005
Boundary for River Rch & Prof#=Stream0039_DS,Reach-1,5
Up Type=0
Dn Type=3
Dn Slope=0.005
Boundary for River Rch & Prof#=Stream0039_DS,Reach-1,6
Up Type=0
Dn Type=3
Dn Slope=0.005
Boundary for River Rch & Prof#=Stream0039_DS,Reach-1,7
Up Type=0
Dn Type=3
Dn Slope=0.005

--- Stream0039_DS.g01 (geometry) ---

Geom Title=Existing Conditions

River Reach=Stream0039_DS,Reach-1
Reach XY= 30
      2132983.02     13907670.06      2132910.43     13907497.38
      2133085.51     13907115.19      2133172.56     13907030.52
      2133302.33     13906999.01      2133330.53     13906872.58
      2133465.32     13906735.76      2133838.66     13906561.74
      2133921.25     13906423.45      2133882.56     13906125.00
      2134025.44     13905488.82      2133929.97     13905072.42
      2134081.17     13905017.14      2134268.95     13904833.16
      2134569.39     13904669.41      2134718.81     13904482.82
      2134884.82     13904464.53      2135172.64     13904069.48
      2135225.06     13903793.29      2135128.54     13903673.53
      2135125.49     13903540.22      2135222.64     13903369.48
      2135373.78     13902764.50      2135425.45     13902435.19
      2135424.30     13902188.91      2135374.72     13902095.18
      2135425.35     13901899.81      2135233.16     13901681.05
      2135078.83     13901373.42      2135025.00     13901075.00

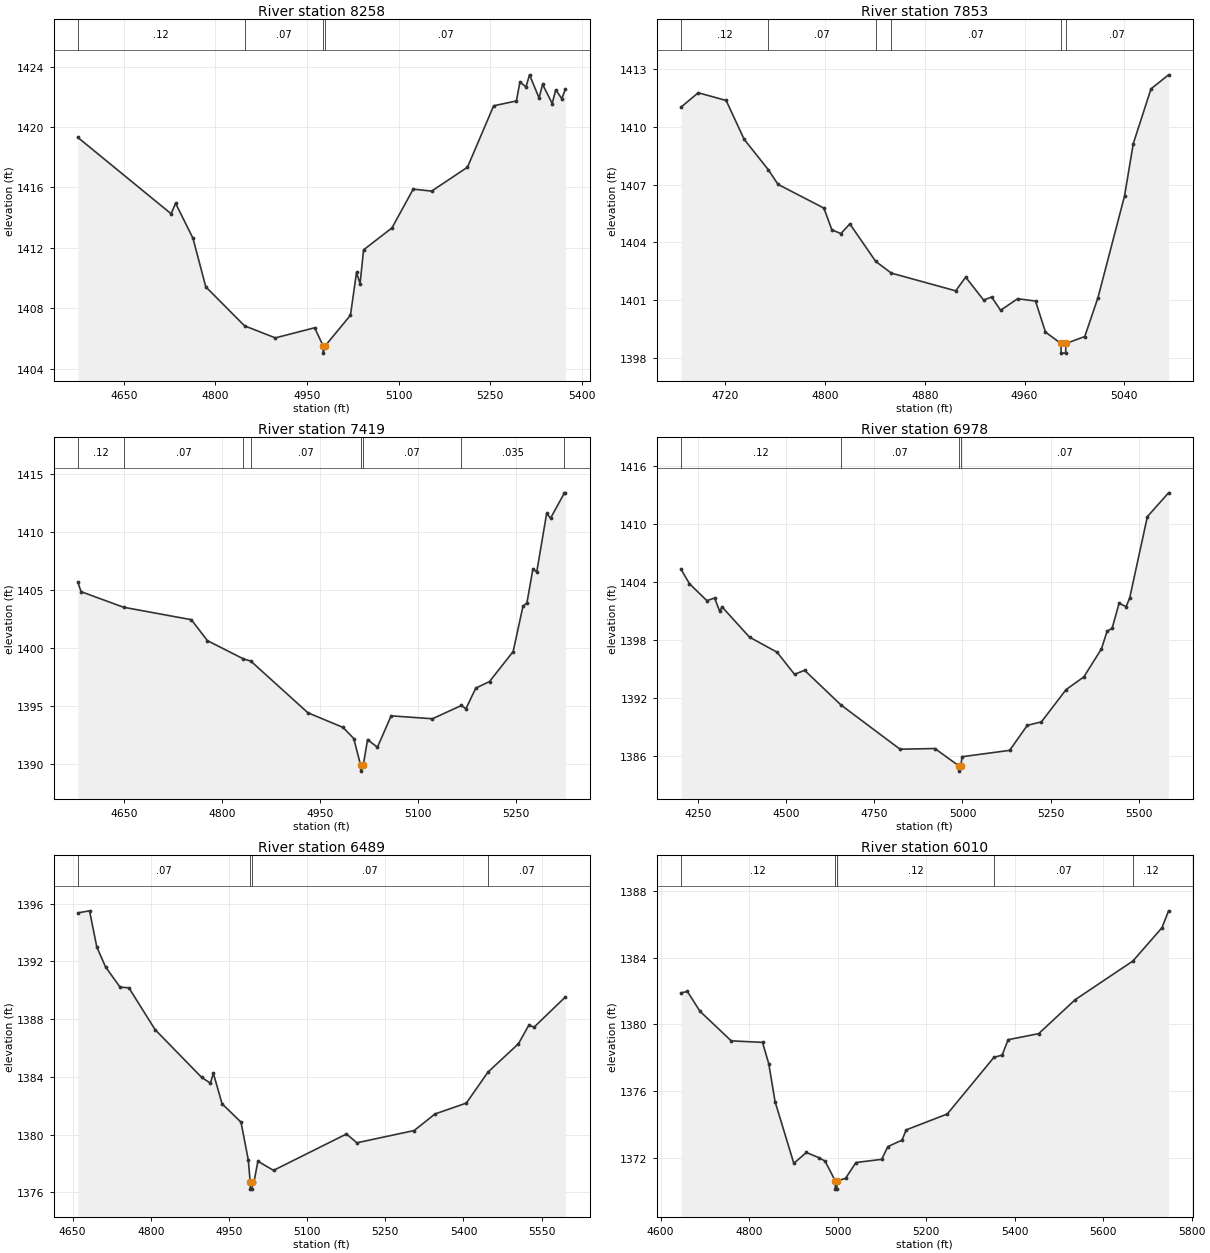
Type RM Length L Ch R = 1,8258,405,405,405
BEGIN DESCRIPTION:
Stream0039_DS 16.0
END DESCRIPTION:
XS GIS Cut Line= 4
      2133279.29     13907776.61      2133089.25     13907570.55
      2133068.60     13907568.64      2132640.24     13907820.16
#Sta/Elev= 30
  4575.0 1419.31  4727.5 1414.26  4734.9 1414.95  4763.3 1412.64  4784.3 1409.42
  4847.7 1406.84  4898.1 1406.04  4962.5 1406.71  4976.1 1405.53  4976.4 1405.03
  4980.1 1405.53  5021.1 1407.54  5031.0 1410.37  5036.8 1409.63  5042.6 1411.87
  5089.0 1413.32  5123.8 1415.89  5154.0 1415.76  5212.6 1417.34  5255.5 1421.41
  5292.7 1421.73  5298.5 1422.98  5308.4 1422.66  5314.2 1423.46  5329.8 1421.93
  5335.6 1422.83  5351.3 1421.56  5357.1 1422.47  5367.0 1421.88  5372.8 1422.50
#Mann=4,-1,0
  4575.0    0.12       0  4847.7    0.07       0  4976.1    0.05       0
  4980.1    0.07       0
Bank Sta=4976.1,4980.1
Exp/Cntr=0.3,0.1

Type RM Length L Ch R = 1,7853,434,434,434
BEGIN DESCRIPTION:
Stream0039_DS 15.0
END DESCRIPTION:
XS GIS Cut Line= 3
      2133275.03     13907475.03      2133025.00     13907275.00
      2132975.01     13907225.01
#Sta/Elev= 30
  4684.6 1411.02  4698.3 1411.76  4720.7 1411.36  4735.1 1409.35  4754.5 1407.77
  4762.3 1407.01  4799.1 1405.78  4805.5 1404.65  4812.7 1404.46  4819.9 1404.96
  4840.6 1403.02  4853.1 1402.41  4904.8 1401.49  4912.8 1402.20  4927.2 1401.01
  4933.6 1401.17  4940.8 1400.48  4954.4 1401.08  4968.8 1400.96  4976.8 1399.35
  4989.2 1398.76  4989.4 1398.26  4992.9 1398.26  4993.2 1398.76  5008.3 1399.12
  5018.9 1401.14  5040.2 1406.41  5047.2 1409.12  5061.4 1411.96  5075.5 1412.69
#Mann=6,-1,0
  4684.6    0.12       0  4754.5    0.07       0  4840.6    0.12       0
  4853.1    0.07       0  4989.2    0.05       0  4993.2    0.07       0
Bank Sta=4989.2,4993.2
Exp/Cntr=0.3,0.1

Type RM Length L Ch R = 1,7419,441,441,441
BEGIN DESCRIPTION:
Stream0039_DS 14.0
END DESCRIPTION:
XS GIS Cut Line= 3
      2133452.16     13907393.32      2133302.85     13907007.88
      2133024.98     13906824.99
#Sta/Elev= 30
  4579.8 1405.64  4584.6 1404.85  4649.6 1403.51  4753.4 1402.44  4778.0 1400.64
  4832.9 1399.08  4844.5 1398.88  4931.9 1394.44  4985.5 1393.19  5002.0 1392.23
  5012.5 1389.93  5012.8 1389.43  5016.5 1389.93  5023.1 1392.14  5038.2 1391.48
  5059.2 1394.18  5122.4 1393.93  5166.7 1395.07  5173.7 1394.79  5188.7 1396.56
  5209.8 1397.13  5245.9 1399.70  5261.0 1403.60  5267.0 1403.88  5276.1 1406.77
  5282.1 1406.56  5297.2 1411.57  5303.2 1411.16  5324.5 1413.34  5325.8 1413.34
#Mann=8,-1,0
  4579.8    0.12       0  4649.6    0.07       0  4832.9    0.12       0
  4844.5    0.07       0  5012.5    0.05       0  5016.5    0.07       0
  5166.7   0.035       0  5324.5    0.07       0
Bank Sta=5012.5,5016.5
Exp/Cntr=0.3,0.1

Type RM Length L Ch R = 1,6978,489,489,489
BEGIN DESCRIPTION:
Stream0039_DS 13.0
END DESCRIPTION:
XS GIS Cut Line= 3
      2134073.72     13907299.59      2133559.80     13906691.91
      2132974.99     13906675.00
#Sta/Elev= 30
  4203.0 1405.29  4226.4 1403.82  4275.9 1402.06  4297.9 1402.33  4312.2 1400.96
  4318.7 1401.42  4396.7 1398.28  4474.8 1396.72  4524.2 1394.43  4552.8 1394.85
  4655.8 1391.26  4823.1 1386.68  4921.9 1386.75  4991.4 1384.91  4991.6 1384.41
  4995.4 1384.91  4998.7 1385.90  5133.7 1386.56  5183.7 1389.15  5223.7 1389.51
  5293.8 1392.86  5343.8 1394.16  5393.8 1397.07  5409.9 1398.91  5423.8 1399.18
  5443.8 1401.79  5463.8 1401.44  5473.8 1402.34  5523.9 1410.76  5583.9 1413.22
#Mann=4,-1,0
  4203.0    0.12       0  4655.8    0.07       0  4991.4    0.05       0
  4995.4    0.07       0
Bank Sta=4991.4,4995.4
Exp/Cntr=0.3,0.1

Type RM Length L Ch R = 1,6489,479,479,479
BEGIN DESCRIPTION:
Stream0039_DS 12.0
END DESCRIPTION:
XS GIS Cut Line= 3
      2134224.97     13906574.98      2133925.00     13906425.00
      2133324.97     13906425.00
#Sta/Elev= 30
  4660.1 1395.36  4682.4 1395.50  4696.4 1392.99  4713.2 1391.61  4741.1 1390.21
  4757.9 1390.17  4808.2 1387.27  4897.6 1383.96  4914.4 1383.56  4920.0 1384.25
  4936.8 1382.13  4973.1 1380.86  4987.1 1378.24  4990.7 1376.72  4990.9 1376.22
  4994.4 1376.22  4994.7 1376.72  4998.0 1376.72  5005.5 1378.15  5035.5 1377.52
  5175.5 1380.04  5195.5 1379.43  5305.5 1380.28  5345.5 1381.43  5405.5 1382.18
  5447.1 1384.33  5505.5 1386.29  5525.5 1387.58  5535.5 1387.44  5595.5 1389.53
#Mann=4,-1,0
  4660.1    0.07       0  4990.7    0.05       0  4994.7    0.07       0
  5447.1    0.07       0
Bank Sta=4990.7,4994.7
Exp/Cntr=0.3,0.1

Type RM Length L Ch R = 1,6010,483,483,483
BEGIN DESCRIPTION:
Stream0039_DS 11.0
END DESCRIPTION:
XS GIS Cut Line= 3
      2134175.03     13906225.03      2133925.00     13905975.00
      2133200.60     13906160.17
#Sta/Elev= 30
  4646.5 1381.89  4660.7 1381.97  4689.0 1380.79  4759.7 1379.02  4830.4 1378.93
  4844.5 1377.65  4858.7 1375.39  4901.1 1371.70  4929.4 1372.35  4957.7 1372.04
  4971.8 1371.83  4994.6 1370.66  4994.8 1370.16  4998.3 1370.16  4998.6 1370.66
  5017.9 1370.80  5041.4 1371.75  5099.6 1371.94  5113.6 1372.70  5145.6 1373.09
  5154.9 1373.70  5247.8 1374.65  5353.1 1378.03  5371.7 1378.17  5385.4 1379.09
  5454.3 1379.45  5536.8 1381.48  5667.2 1383.79  5732.9 1385.78  5747.8 1386.79
#Mann=5,-1,0
  4646.5    0.12       0  4994.6    0.05       0  4998.6    0.12       0
  5353.1    0.07       0  5667.2    0.12       0
Bank Sta=4994.6,4998.6
Exp/Cntr=0.3,0.1

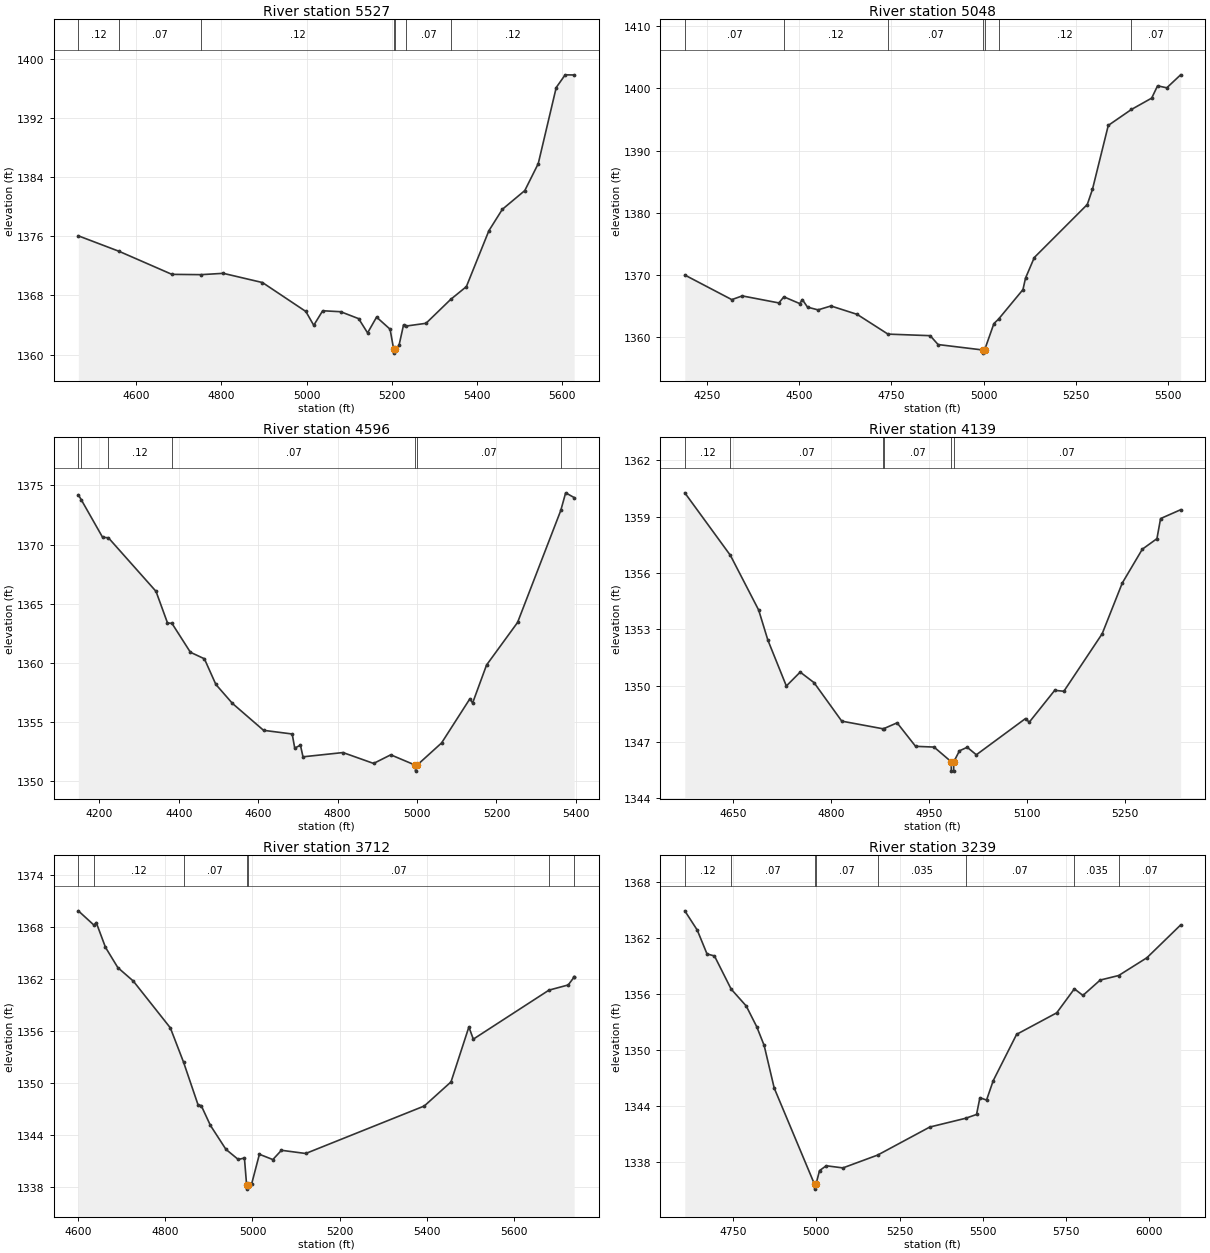
Type RM Length L Ch R = 1,5527,479,479,479
BEGIN DESCRIPTION:
Stream0039_DS 10.0
END DESCRIPTION:
XS GIS Cut Line= 3
      2134374.98     13905924.98      2134025.00     13905525.00
      2133425.03     13905325.01
#Sta/Elev= 30
  4464.4 1376.08  4560.1 1373.98  4684.1 1370.86  4752.5 1370.82  4804.6 1371.00
  4896.7 1369.75  4998.5 1365.83  5017.0 1363.96  5038.0 1365.93  5080.2 1365.80
  5122.4 1364.86  5143.4 1362.93  5164.5 1365.07  5196.2 1363.43  5204.7 1360.69
  5204.9 1360.19  5208.7 1360.69  5217.2 1361.25  5227.8 1364.01  5234.2 1363.86
  5280.5 1364.23  5338.3 1367.46  5375.3 1369.20  5428.1 1376.77  5459.7 1379.67
  5512.4 1382.21  5544.0 1385.86  5586.2 1396.17  5607.2 1397.89  5628.3 1397.87
#Mann=7,-1,0
  4464.4    0.12       0  4560.1    0.07       0  4752.5    0.12       0
  5204.7    0.05       0  5208.7    0.12       0  5234.2    0.07       0
  5338.3    0.12       0
Bank Sta=5204.7,5208.7
Exp/Cntr=0.3,0.1

Type RM Length L Ch R = 1,5048,452,452,452
BEGIN DESCRIPTION:
Stream0039_DS 9.0
END DESCRIPTION:
XS GIS Cut Line= 3
      2134475.02     13905675.02      2133925.00     13905075.00
      2133408.47     13904956.14
#Sta/Elev= 30
  4189.8 1369.98  4317.2 1366.02  4345.5 1366.62  4444.8 1365.49  4458.4 1366.47
  4501.5 1365.38  4508.3 1366.04  4522.5 1364.81  4550.9 1364.37  4586.0 1365.00
  4656.9 1363.65  4740.5 1360.47  4854.9 1360.22  4876.4 1358.79  4998.4 1357.91
  4998.6 1357.41  5002.4 1357.91  5027.7 1362.17  5040.2 1362.88  5106.4 1367.63
  5113.4 1369.49  5137.2 1372.80  5280.8 1381.33  5294.9 1383.79  5337.7 1394.06
  5400.3 1396.62  5455.3 1398.45  5471.3 1400.43  5496.3 1400.11  5533.8 1402.20
#Mann=7,-1,0
  4189.8    0.07       0  4458.4    0.12       0  4740.5    0.07       0
  4998.4    0.05       0  5002.4    0.07       0  5040.2    0.12       0
  5400.3    0.07       0
Bank Sta=4998.4,5002.4
Exp/Cntr=0.3,0.1

Type RM Length L Ch R = 1,4596,457,457,457
BEGIN DESCRIPTION:
Stream0039_DS 8.0
END DESCRIPTION:
XS GIS Cut Line= 3
      2134946.56     13905359.05      2134275.00     13904825.00
      2133975.03     13904575.02
#Sta/Elev= 30
  4147.1 1374.21  4154.4 1373.80  4208.2 1370.62  4222.8 1370.58  4342.7 1366.05
  4371.6 1363.38  4382.9 1363.34  4429.3 1360.90  4464.5 1360.35  4493.4 1358.18
  4535.0 1356.58  4613.5 1354.30  4685.6 1353.99  4692.0 1352.80  4706.4 1353.04
  4712.8 1352.06  4813.5 1352.42  4890.6 1351.50  4933.8 1352.23  4995.9 1351.35
  4996.2 1350.85  4999.9 1351.35  5061.7 1353.23  5133.3 1356.98  5139.8 1356.60
  5175.0 1359.82  5253.1 1363.42  5361.9 1372.89  5374.2 1374.38  5395.6 1373.98
#Mann=7,-1,0
  4147.1    0.12       0  4154.4    0.07       0  4222.8    0.12       0
  4382.9    0.07       0  4995.9    0.05       0  4999.9    0.07       0
  5361.9    0.12       0
Bank Sta=4995.9,4999.9
Exp/Cntr=0.3,0.1

Type RM Length L Ch R = 1,4139,427,427,427
BEGIN DESCRIPTION:
Stream0039_DS 7.0
END DESCRIPTION:
XS GIS Cut Line= 3
      2134925.02     13904875.02      2134625.00     13904575.00
      2134325.01     13904425.00
#Sta/Elev= 30
  4575.5 1360.26  4645.4 1356.93  4688.7 1354.02  4702.8 1352.42  4731.1 1349.98
  4752.3 1350.72  4773.5 1350.16  4816.0 1348.11  4879.6 1347.70  4880.3 1347.71
  4900.8 1348.02  4929.1 1346.77  4957.4 1346.73  4983.7 1345.95  4983.9 1345.45
  4987.4 1345.45  4987.7 1345.95  4996.3 1346.53  5008.2 1346.72  5022.2 1346.32
  5097.6 1348.25  5103.2 1348.05  5142.3 1349.75  5156.3 1349.70  5215.0 1352.76
  5245.8 1355.46  5276.5 1357.26  5298.9 1357.82  5304.5 1358.89  5335.2 1359.36
#Mann=6,-1,0
  4575.5    0.12       0  4645.4    0.07       0  4879.6    0.12       0
  4880.3    0.07       0  4983.7    0.05       0  4987.7    0.07       0
Bank Sta=4983.7,4987.7
Exp/Cntr=0.3,0.1

Type RM Length L Ch R = 1,3712,473,473,473
BEGIN DESCRIPTION:
Stream0039_DS 6.0
END DESCRIPTION:
XS GIS Cut Line= 3
      2135250.78     13904657.20      2134975.00     13904375.00
      2134248.62     13904226.90
#Sta/Elev= 30
  4601.0 1369.81  4636.8 1368.16  4642.0 1368.46  4663.2 1365.60  4691.5 1363.26
  4726.9 1361.71  4811.8 1356.31  4842.0 1352.36  4875.3 1347.43  4882.5 1347.35
  4903.6 1345.06  4939.1 1342.30  4967.4 1341.13  4981.5 1341.30  4986.5 1338.21
  4986.8 1337.71  4990.5 1338.21  4998.1 1338.32  5015.8 1341.73  5046.6 1341.12
  5066.3 1342.19  5121.9 1341.82  5393.6 1347.30  5454.8 1350.08  5495.7 1356.41
  5505.9 1355.01  5679.1 1360.66  5723.3 1361.26  5736.1 1362.12  5736.9 1362.19
#Mann=7,-1,0
  4601.0    0.07       0  4636.8    0.12       0  4842.0    0.07       0
  4986.5    0.05       0  4990.5    0.07       0  5679.1   0.035       0
  5736.1    0.07       0
Bank Sta=4986.5,4990.5
Exp/Cntr=0.3,0.1

Type RM Length L Ch R = 1,3239,454,454,454
BEGIN DESCRIPTION:
Stream0039_DS 5.0
END DESCRIPTION:
XS GIS Cut Line= 3
      2135528.52     13904150.23      2135175.00     13903975.00
      2134084.15     13904063.44
#Sta/Elev= 30
  4605.1 1364.95  4642.5 1362.88  4671.8 1360.32  4694.2 1360.10  4744.3 1356.54
  4789.5 1354.73  4821.1 1352.50  4843.4 1350.49  4873.6 1345.91  4994.9 1335.55
  4995.1 1335.05  4998.9 1335.55  5009.7 1337.04  5029.8 1337.56  5079.9 1337.33
  5184.3 1338.71  5340.8 1341.72  5448.2 1342.66  5481.2 1343.07  5491.3 1344.87
  5511.3 1344.62  5531.4 1346.71  5601.6 1351.68  5722.0 1353.99  5775.0 1356.57
  5800.7 1355.86  5852.5 1357.51  5908.0 1358.00  5992.9 1359.91  6094.1 1363.43
#Mann=8,-1,0
  4605.1    0.12       0  4744.3    0.07       0  4994.9    0.05       0
  4998.9    0.07       0  5184.3   0.035       0  5448.2    0.07       0
  5775.0   0.035       0  5908.0    0.07       0
Bank Sta=4994.9,4998.9
Exp/Cntr=0.3,0.1

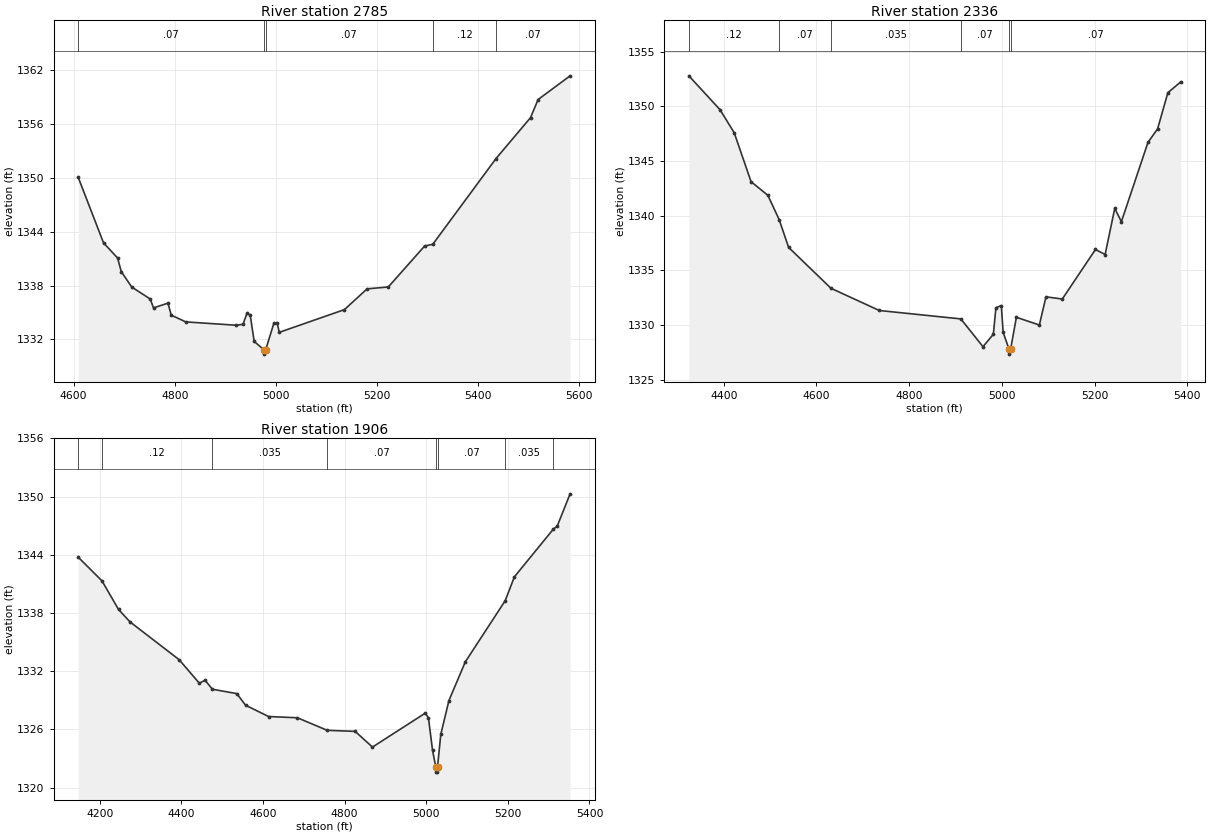
Type RM Length L Ch R = 1,2785,449,449,449
BEGIN DESCRIPTION:
Stream0039_DS 4.0
END DESCRIPTION:
XS GIS Cut Line= 3
      2135425.03     13903825.02      2135125.00     13903575.00
      2134643.13     13903247.46
#Sta/Elev= 30
  4608.9 1350.08  4659.1 1342.77  4687.0 1341.07  4694.2 1339.56  4715.0 1337.84
  4751.5 1336.51  4758.0 1335.52  4786.6 1336.05  4793.1 1334.71  4821.8 1333.96
  4921.3 1333.59  4935.0 1333.69  4942.8 1334.90  4949.3 1334.73  4957.1 1331.79
  4976.0 1330.87  4976.2 1330.37  4980.0 1330.87  4996.2 1333.83  5002.5 1333.83
  5006.9 1332.80  5135.7 1335.33  5180.5 1337.64  5222.5 1337.85  5294.3 1342.41
  5310.5 1342.61  5435.6 1352.16  5503.8 1356.71  5518.8 1358.73  5582.1 1361.37
#Mann=5,-1,0
  4608.9    0.07       0  4976.0    0.05       0  4980.0    0.07       0
  5310.5    0.12       0  5435.6    0.07       0
Bank Sta=4976,4980
Exp/Cntr=0.3,0.1

Type RM Length L Ch R = 1,2336,430,430,430
BEGIN DESCRIPTION:
Stream0039_DS 3.0
END DESCRIPTION:
XS GIS Cut Line= 3
      2135575.01     13903775.01      2135275.00     13903175.00
      2134975.03     13902925.03
#Sta/Elev= 30
  4324.8 1352.80  4391.9 1349.71  4422.6 1347.60  4459.0 1343.12  4495.3 1341.87
  4519.7 1339.64  4540.0 1337.11  4631.4 1333.37  4735.7 1331.34  4911.6 1330.57
  4959.3 1328.03  4981.7 1329.17  4987.2 1331.59  4998.9 1331.79  5002.8 1329.34
  5015.1 1327.85  5015.4 1327.35  5019.1 1327.85  5031.4 1330.72  5080.9 1330.01
  5095.2 1332.59  5130.4 1332.39  5202.0 1336.92  5222.8 1336.46  5243.6 1340.68
  5257.9 1339.46  5315.2 1346.71  5336.0 1347.95  5358.2 1351.26  5386.1 1352.25
#Mann=6,-1,0
  4324.8    0.12       0  4519.7    0.07       0  4631.4   0.035       0
  4911.6    0.07       0  5015.1    0.05       0  5019.1    0.07       0
Bank Sta=5015.1,5019.1
Exp/Cntr=0.3,0.1

Type RM Length L Ch R = 1,1906,0,0,0
BEGIN DESCRIPTION:
Stream0039_DS 2.0
END DESCRIPTION:
XS GIS Cut Line= 3
      2135974.97     13903374.97      2135375.00     13902775.00
      2135019.05     13902747.54
#Sta/Elev= 30
  4147.1 1343.76  4205.7 1341.30  4246.1 1338.36  4274.3 1337.08  4394.5 1333.19
  4444.0 1330.77  4458.2 1331.06  4476.2 1330.14  4536.0 1329.69  4557.2 1328.50
  4613.8 1327.33  4684.5 1327.20  4757.2 1325.91  4825.9 1325.80  4868.3 1324.18
  4998.1 1327.69  5005.6 1327.16  5015.6 1323.83  5023.7 1322.10  5023.9 1321.60
  5027.4 1321.60  5027.7 1322.10  5035.7 1325.48  5055.7 1328.98  5095.9 1332.97
  5193.5 1339.26  5216.2 1341.73  5310.9 1346.61  5321.1 1346.96  5352.6 1350.28
#Mann=8,-1,0
  4147.1    0.07       0  4205.7    0.12       0  4476.2   0.035       0
  4757.2    0.07       0  5023.7    0.05       0  5027.7    0.07       0
  5193.5   0.035       0  5310.9    0.07       0
Bank Sta=5023.7,5027.7
Exp/Cntr=0.3,0.1

Chan Stop Cuts=-1