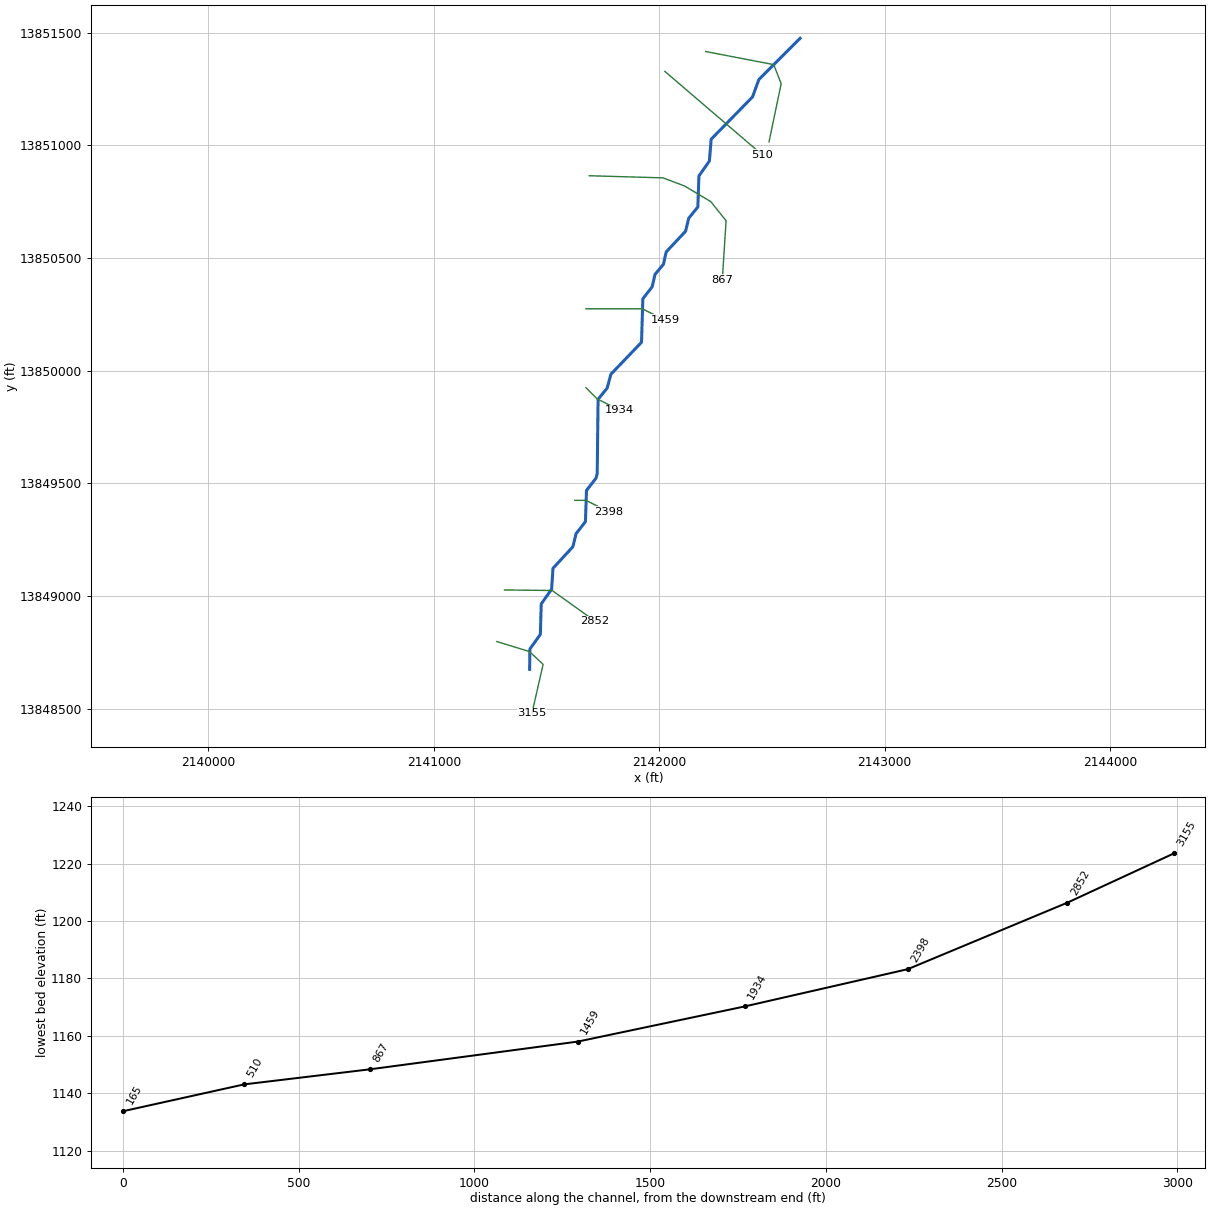
--- Stream0071_DS.prj (project) ---

Proj Title=Stream0071_DS Base Level Engineering
Current Plan=p01
Default Exp/Contr=0.3,0.1
English Units
Geom File=g01
Flow File=f01
Plan File=p01
BEGIN DESCRIPTION:
Stream0071_DS
END DESCRIPTION:

--- Stream0071_DS.p01 (plan) ---

Plan Title=Multiple Run
Short Identifier=Multiple
Geom File=g01
Flow File=f01
Subcritical Flow
K Sum by GR= 0
Std Step Tol= 0.01
Critical Tol= 0.01
Num of Std Step Trials= 20
Max Error Tol= 0.3
Flow Tol Ratio= 0.001
Split Flow NTrial= 30
Split Flow Tol= 0.02
Split Flow Ratio= 0.02
Log Output Level= 0
Friction Slope Method= 1
Unsteady Friction Slope Method= 2
Unsteady Bridges Friction Slope Method= 1
Parabolic Critical Depth
Global Vel Dist=  1 , 1 , 1
Global Log Level= 0
CheckData=True
Encroach Param= -1, 0, 0, 0
BEGIN DESCRIPTION:
Multiple Run
END DESCRIPTION:

--- Stream0071_DS.f01 (steady flow) ---

Flow Title=Multiple
Number of Profiles=7
Profile Names=10-year,25-year,50-year,1pct_min,100-year,1pct_plu,500-year
River Rch & RM= Stream0071_DS,Reach-1,3155
     981    1655    2293    1541    3076    6137    5471
Boundary for River Rch & Prof#=Stream0071_DS,Reach-1,1
Up Type=0
Dn Type=3
Dn Slope=0.005
Boundary for River Rch & Prof#=Stream0071_DS,Reach-1,2
Up Type=0
Dn Type=3
Dn Slope=0.005
Boundary for River Rch & Prof#=Stream0071_DS,Reach-1,3
Up Type=0
Dn Type=3
Dn Slope=0.005
Boundary for River Rch & Prof#=Stream0071_DS,Reach-1,4
Up Type=0
Dn Type=3
Dn Slope=0.005
Boundary for River Rch & Prof#=Stream0071_DS,Reach-1,5
Up Type=0
Dn Type=3
Dn Slope=0.005
Boundary for River Rch & Prof#=Stream0071_DS,Reach-1,6
Up Type=0
Dn Type=3
Dn Slope=0.005
Boundary for River Rch & Prof#=Stream0071_DS,Reach-1,7
Up Type=0
Dn Type=3
Dn Slope=0.005

--- Stream0071_DS.g01 (geometry) ---

Geom Title=Existing Conditions

River Reach=Stream0071_DS,Reach-1
Reach XY= 30
      2141425.00     13848675.00      2141426.19     13848765.42
      2141472.64     13848830.52      2141476.39     13848965.33
      2141522.53     13849030.57      2141528.62     13849123.50
      2141616.84     13849218.95      2141631.14     13849277.17
      2141672.64     13849330.52      2141677.27     13849469.06
      2141719.25     13849522.67      2141724.79     13849543.27
      2141728.75     13849873.45      2141768.86     13849922.83
      2141785.76     13849984.68      2141921.46     13850126.46
      2141927.35     13850319.48      2141968.88     13850372.82
      2141981.08     13850427.20      2142018.90     13850472.81
      2142030.85     13850527.29      2142116.84     13850618.95
      2142131.14     13850677.17      2142171.24     13850726.56
      2142176.23     13850864.49      2142222.53     13850930.57
      2142230.52     13851027.43      2142414.22     13851215.32
      2142441.65     13851291.67      2142625.00     13851475.00

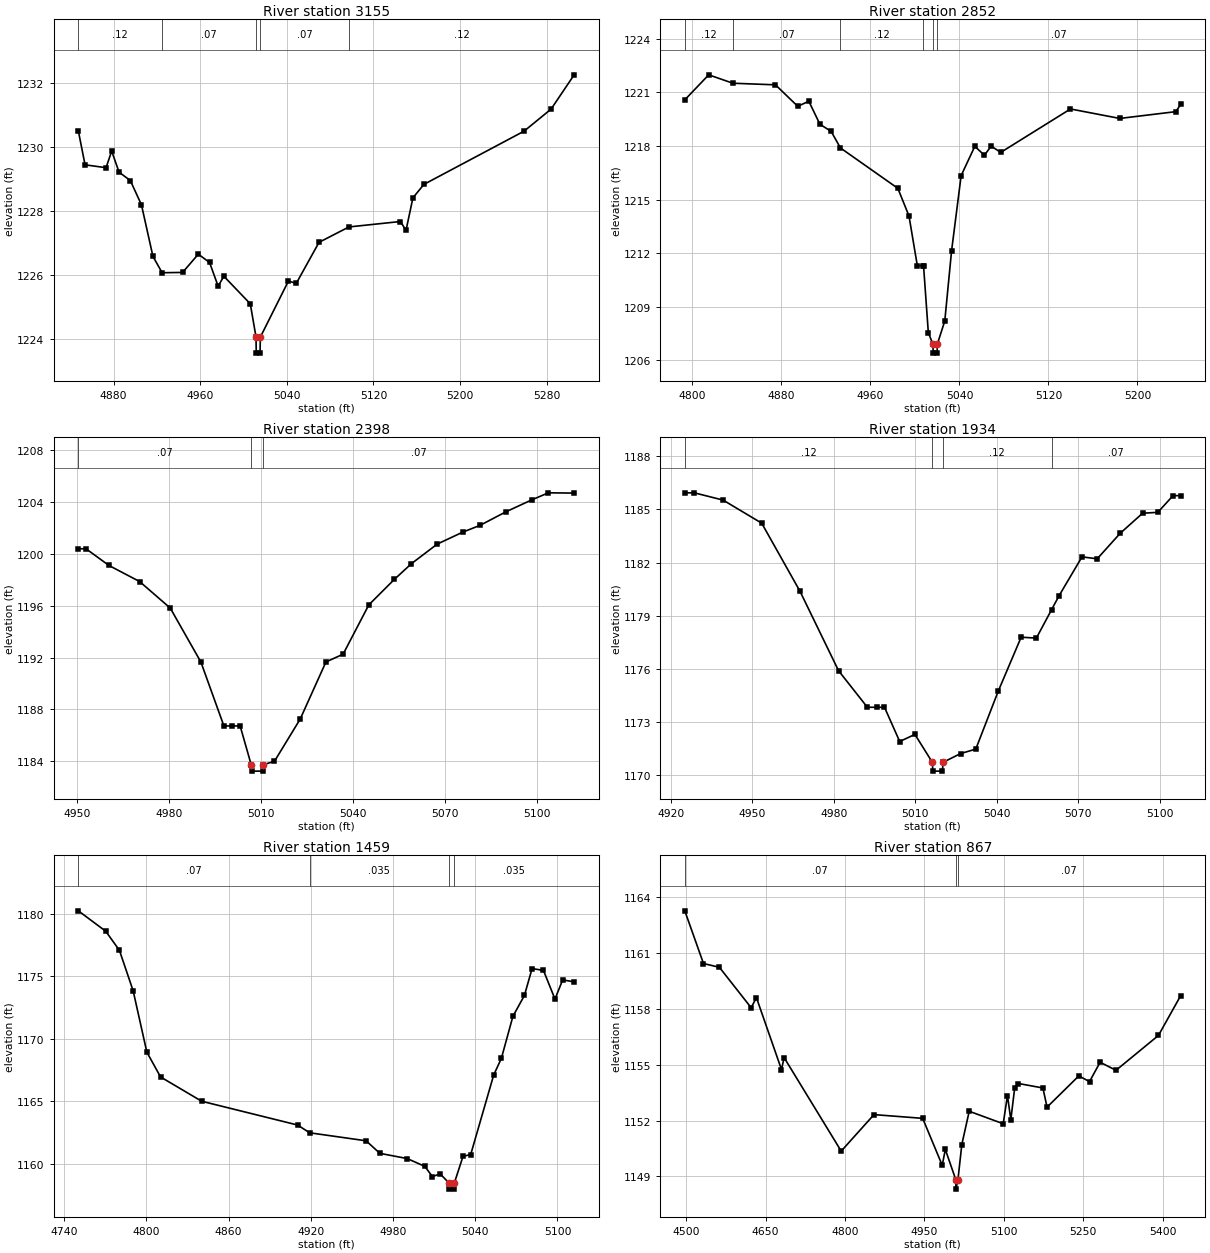
Type RM Length L Ch R = 1,3155,303,303,303
BEGIN DESCRIPTION:
Stream0071_DS 5.0
END DESCRIPTION:
XS GIS Cut Line= 4
      2141279.08     13848798.55      2141424.17     13848754.17
      2141484.80     13848697.17      2141435.12     13848479.82
#Sta/Elev= 30
  4847.5 1230.51  4853.7 1229.45  4873.1 1229.36  4878.3 1229.88  4885.1 1229.22
  4895.5 1228.96  4905.8 1228.20  4916.4 1226.59  4924.9 1226.08  4943.8 1226.09
  4958.3 1226.66  4968.7 1226.40  4976.6 1225.66  4981.9 1225.97  5006.3 1225.11
  5011.6 1224.07  5011.8 1223.57  5015.3 1223.57  5015.6 1224.07  5041.5 1225.82
  5048.8 1225.75  5069.8 1227.03  5097.4 1227.51  5145.0 1227.68  5150.1 1227.40
  5156.5 1228.42  5166.7 1228.84  5259.1 1230.50  5284.1 1231.19  5305.4 1232.26
#Mann=5,-1,0
  4847.5    0.12       0  4924.9    0.07       0  5011.6    0.05       0
  5015.6    0.07       0  5097.4    0.12       0
Bank Sta=5011.6,5015.6
Exp/Cntr=0.3,0.1

Type RM Length L Ch R = 1,2852,454,454,454
BEGIN DESCRIPTION:
Stream0071_DS 4.0
END DESCRIPTION:
XS GIS Cut Line= 3
      2141313.48     13849027.45      2141525.00     13849025.00
      2141715.60     13848888.96
#Sta/Elev= 30
  4793.1 1220.58  4814.6 1221.98  4836.3 1221.51  4874.6 1221.42  4894.6 1220.22
  4904.6 1220.50  4914.6 1219.21  4924.6 1218.82  4933.0 1217.89  4984.6 1215.63
  4994.6 1214.09  5002.1 1211.31  5006.9 1211.31  5007.7 1211.31  5012.0 1207.56
  5016.1 1206.91  5016.4 1206.41  5019.9 1206.41  5020.1 1206.91  5026.8 1208.21
  5032.9 1212.13  5041.5 1216.34  5053.8 1217.98  5062.4 1217.48  5068.5 1217.99
  5077.1 1217.64  5139.8 1220.07  5184.1 1219.54  5234.5 1219.92  5238.8 1220.32
#Mann=6,-1,0
  4793.1    0.12       0  4836.3    0.07       0  4933.0    0.12       0
  5006.9    0.07       0  5016.1    0.05       0  5020.1    0.07       0
Bank Sta=5016.1,5020.1
Exp/Cntr=0.3,0.1

Type RM Length L Ch R = 1,2398,464,464,464
BEGIN DESCRIPTION:
Stream0071_DS 3.0
END DESCRIPTION:
XS GIS Cut Line= 3
      2141624.97     13849425.00      2141675.00     13849425.00
      2141774.97     13849375.02
#Sta/Elev= 27
  4950.3 1200.40  4952.8 1200.40  4960.3 1199.11  4970.3 1197.87  4980.3 1195.82
  4990.3 1191.65  4997.8 1186.72  5000.3 1186.72  5003.1 1186.72  5006.7 1183.73
  5007.0 1183.23  5010.5 1183.23  5010.7 1183.73  5014.3 1183.99  5022.7 1187.25
  5031.1 1191.66  5036.7 1192.26  5045.1 1196.07  5053.4 1198.03  5059.0 1199.25
  5067.4 1200.76  5075.8 1201.69  5081.4 1202.21  5089.8 1203.25  5098.2 1204.17
  5103.7 1204.72  5112.1 1204.70
#Mann=3,-1,0
  4950.3    0.07       0  5006.7    0.05       0  5010.7    0.07       0
Bank Sta=5006.7,5010.7
Exp/Cntr=0.3,0.1

Type RM Length L Ch R = 1,1934,475,475,475
BEGIN DESCRIPTION:
Stream0071_DS 2.0
END DESCRIPTION:
XS GIS Cut Line= 3
      2141675.00     13849925.00      2141725.00     13849875.00
      2141824.98     13849825.01
#Sta/Elev= 29
  4925.2 1185.93  4928.7 1185.93  4939.3 1185.52  4953.5 1184.22  4967.6 1180.38
  4981.8 1175.90  4992.4 1173.84  4995.9 1173.84  4998.7 1173.84  5004.3 1171.91
  5009.9 1172.31  5016.3 1170.74  5016.5 1170.24  5020.0 1170.24  5020.3 1170.74
  5026.7 1171.23  5032.3 1171.48  5040.6 1174.76  5049.0 1177.79  5054.6 1177.74
  5060.2 1179.34  5063.0 1180.14  5071.4 1182.32  5077.0 1182.21  5085.4 1183.64
  5093.7 1184.78  5099.3 1184.83  5104.9 1185.77  5107.7 1185.77
#Mann=4,-1,0
  4925.2    0.12       0  5016.3    0.05       0  5020.3    0.12       0
  5060.2    0.07       0
Bank Sta=5016.3,5020.3
Exp/Cntr=0.3,0.1

Type RM Length L Ch R = 1,1459,592,592,592
BEGIN DESCRIPTION:
Stream0071_DS 1.0
END DESCRIPTION:
XS GIS Cut Line= 3
      2141675.00     13850275.00      2141925.00     13850275.00
      2142025.00     13850225.00
#Sta/Elev= 30
  4750.4 1180.22  4770.4 1178.59  4780.4 1177.06  4790.4 1173.83  4800.4 1168.93
  4810.4 1166.95  4840.4 1165.01  4910.4 1163.11  4919.2 1162.49  4960.4 1161.85
  4970.4 1160.85  4990.4 1160.43  5003.2 1159.81  5008.8 1158.99  5014.4 1159.21
  5020.8 1158.49  5021.0 1157.99  5024.5 1157.99  5024.8 1158.49  5031.1 1160.61
  5036.7 1160.75  5053.5 1167.11  5059.1 1168.44  5067.5 1171.79  5075.9 1173.46
  5081.5 1175.61  5089.8 1175.46  5098.2 1173.17  5103.8 1174.70  5112.2 1174.55
#Mann=4,-1,0
  4750.4    0.07       0  4919.2   0.035       0  5020.8   0.035       0
  5024.8   0.035       0
Bank Sta=5020.8,5024.8
Exp/Cntr=0.3,0.1

Type RM Length L Ch R = 1,867,357,357,357
BEGIN DESCRIPTION:
Stream0071_DS 0.2
END DESCRIPTION:
XS GIS Cut Line= 6
      2141689.73     13850865.34      2142016.92     13850855.89
      2142112.57     13850819.76      2142228.63     13850750.61
      2142296.68     13850665.62      2142279.88     13850403.21
#Sta/Elev= 30
  4497.5 1163.26  4532.8 1160.43  4562.8 1160.23  4622.8 1158.06  4632.8 1158.60
  4680.1 1154.74  4685.1 1155.38  4792.9 1150.36  4854.8 1152.32  4946.8 1152.12
  4983.7 1149.60  4989.6 1150.45  5009.4 1148.82  5009.6 1148.32  5013.4 1148.82
  5020.7 1150.71  5034.7 1152.50  5098.9 1151.83  5106.9 1153.34  5113.3 1152.05
  5120.6 1153.75  5127.7 1153.99  5173.9 1153.75  5181.7 1152.72  5241.8 1154.40
  5261.9 1154.09  5281.9 1155.13  5312.0 1154.70  5392.1 1156.57  5434.0 1158.70
#Mann=3,-1,0
  4497.5    0.07       0  5009.4    0.05       0  5013.4    0.07       0
Bank Sta=5009.4,5013.4
Exp/Cntr=0.3,0.1

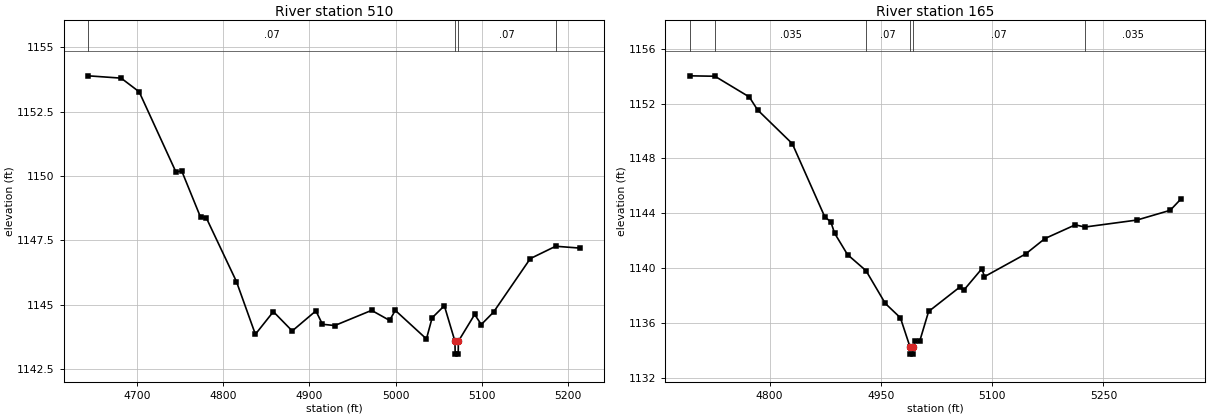
Type RM Length L Ch R = 1,510,345,345,345
BEGIN DESCRIPTION:
Stream0071_DS 0.1
END DESCRIPTION:
XS GIS Cut Line= 2
      2142025.02     13851328.21      2142458.47     13850957.28
#Sta/Elev= 30
  4643.2 1153.89  4681.3 1153.80  4702.2 1153.27  4745.0 1150.15  4751.6 1150.20
  4773.5 1148.40  4780.1 1148.38  4815.2 1145.90  4837.2 1143.85  4858.1 1144.73
  4880.0 1143.98  4907.5 1144.76  4915.1 1144.24  4929.4 1144.19  4972.2 1144.78
  4993.1 1144.39  4999.7 1144.78  5035.9 1143.67  5042.5 1144.49  5056.7 1144.96
  5069.0 1143.58  5069.3 1143.08  5072.8 1143.08  5073.0 1143.58  5091.9 1144.62
  5099.6 1144.23  5113.8 1144.71  5156.5 1146.79  5186.0 1147.27  5213.7 1147.20
#Mann=4,-1,0
  4643.2    0.07       0  5069.0    0.05       0  5073.0    0.07       0
  5186.0   0.035       0
Bank Sta=5069,5073
Exp/Cntr=0.3,0.1

Type RM Length L Ch R = 1,165,0,0,0
BEGIN DESCRIPTION:
Stream0071_DS 0.0
END DESCRIPTION:
XS GIS Cut Line= 4
      2142206.14     13851416.49      2142508.30     13851358.35
      2142541.00     13851273.39      2142487.11     13851015.70
#Sta/Elev= 30
  4692.3 1154.02  4726.3 1153.99  4772.6 1152.48  4783.7 1151.54  4830.6 1149.07
  4874.4 1143.73  4882.5 1143.37  4887.6 1142.54  4905.0 1140.98  4929.9 1139.81
  4955.9 1137.42  4976.3 1136.37  4989.4 1134.22  4989.7 1133.72  4993.2 1133.72
  4993.4 1134.22  4995.8 1134.68  5002.4 1134.68  5014.3 1136.83  5056.1 1138.60
  5061.5 1138.37  5086.1 1139.95  5089.6 1139.37  5145.2 1141.03  5171.1 1142.15
  5212.0 1143.15  5224.9 1142.99  5295.1 1143.50  5339.9 1144.21  5354.3 1145.03
#Mann=6,-1,0
  4692.3    0.07       0  4726.3   0.035       0  4929.9    0.07       0
  4989.4    0.05       0  4993.4    0.07       0  5224.9   0.035       0
Bank Sta=4989.4,4993.4
Exp/Cntr=0.3,0.1

Chan Stop Cuts=-1