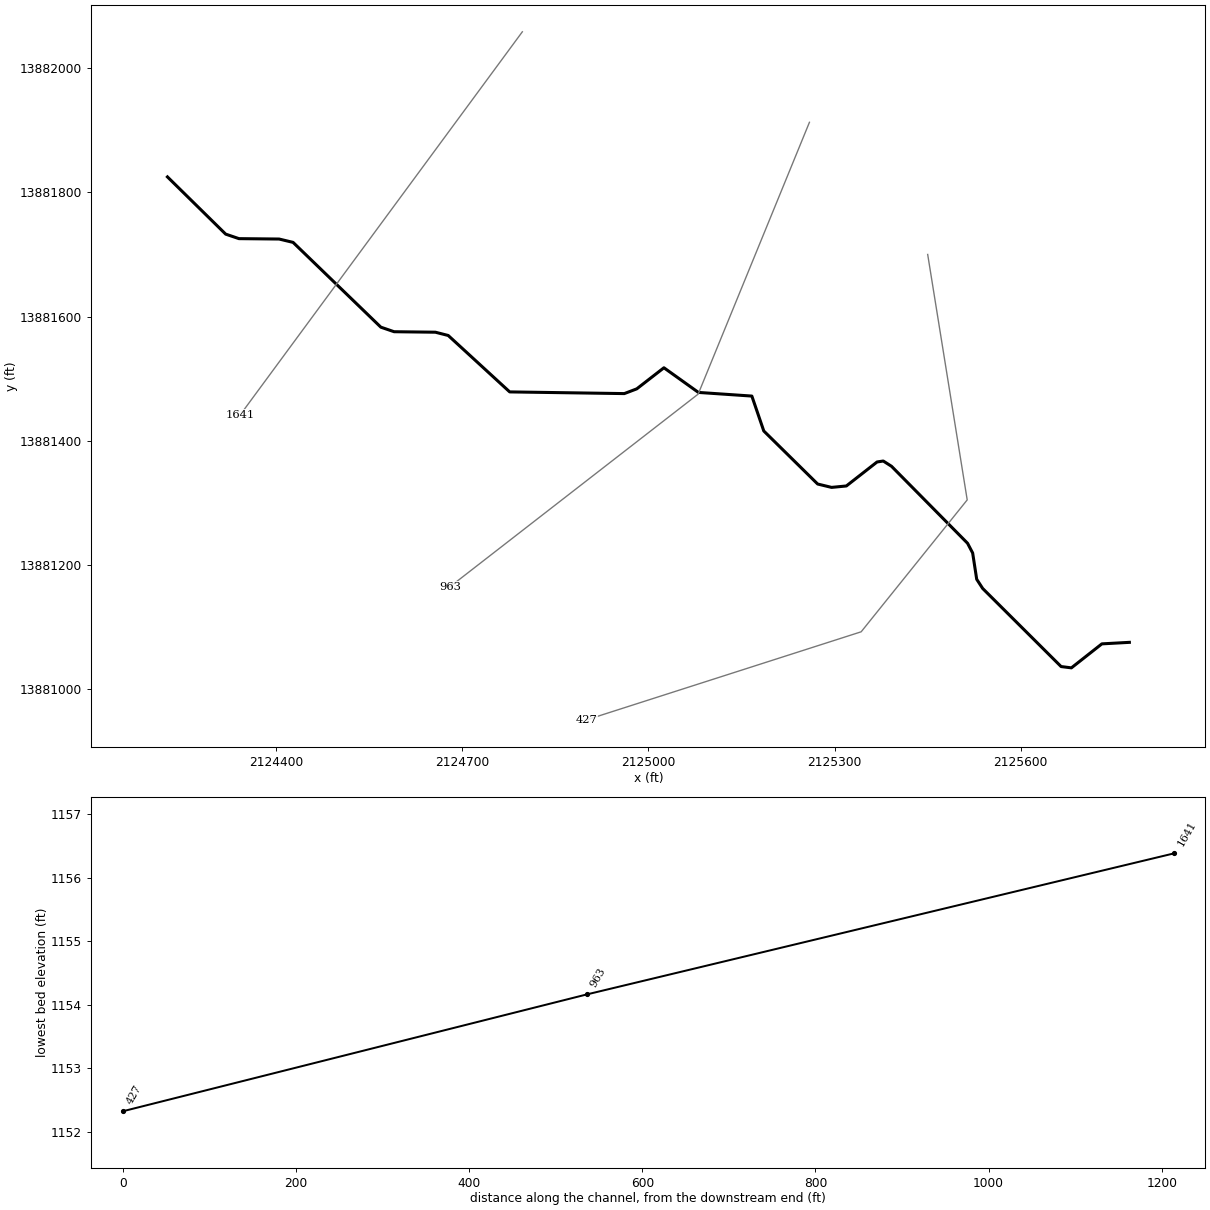
--- Stream0072_DS.prj (project) ---

Proj Title=Stream0072_DS Base Level Engineering
Current Plan=p01
Default Exp/Contr=0.3,0.1
English Units
Geom File=g01
Flow File=f01
Plan File=p01
BEGIN DESCRIPTION:
Stream0072_DS
END DESCRIPTION:

--- Stream0072_DS.p01 (plan) ---

Plan Title=Multiple Run
Short Identifier=Multiple
Geom File=g01
Flow File=f01
Subcritical Flow
K Sum by GR= 0
Std Step Tol= 0.01
Critical Tol= 0.01
Num of Std Step Trials= 20
Max Error Tol= 0.3
Flow Tol Ratio= 0.001
Split Flow NTrial= 30
Split Flow Tol= 0.02
Split Flow Ratio= 0.02
Log Output Level= 0
Friction Slope Method= 1
Unsteady Friction Slope Method= 2
Unsteady Bridges Friction Slope Method= 1
Parabolic Critical Depth
Global Vel Dist=  1 , 1 , 1
Global Log Level= 0
CheckData=True
Encroach Param= -1, 0, 0, 0
BEGIN DESCRIPTION:
Multiple Run
END DESCRIPTION:

--- Stream0072_DS.f01 (steady flow) ---

Flow Title=Multiple
Number of Profiles=7
Profile Names=10-year,25-year,50-year,1pct_min,100-year,1pct_plu,500-year
River Rch & RM= Stream0072_DS,Reach-1,1641
     189     283     361     224     448     894     679
Boundary for River Rch & Prof#=Stream0072_DS,Reach-1,1
Up Type=0
Dn Type=3
Dn Slope=0.005
Boundary for River Rch & Prof#=Stream0072_DS,Reach-1,2
Up Type=0
Dn Type=3
Dn Slope=0.005
Boundary for River Rch & Prof#=Stream0072_DS,Reach-1,3
Up Type=0
Dn Type=3
Dn Slope=0.005
Boundary for River Rch & Prof#=Stream0072_DS,Reach-1,4
Up Type=0
Dn Type=3
Dn Slope=0.005
Boundary for River Rch & Prof#=Stream0072_DS,Reach-1,5
Up Type=0
Dn Type=3
Dn Slope=0.005
Boundary for River Rch & Prof#=Stream0072_DS,Reach-1,6
Up Type=0
Dn Type=3
Dn Slope=0.005
Boundary for River Rch & Prof#=Stream0072_DS,Reach-1,7
Up Type=0
Dn Type=3
Dn Slope=0.005

--- Stream0072_DS.g01 (geometry) ---

Geom Title=Existing Conditions

River Reach=Stream0072_DS,Reach-1
Reach XY= 30
      2124225.00     13881825.00      2124318.80     13881732.79
      2124340.21     13881725.51      2124404.95     13881724.87
      2124427.43     13881719.48      2124568.83     13881582.86
      2124590.22     13881575.53      2124656.71     13881574.74
      2124677.42     13881569.46      2124776.47     13881478.55
      2124961.14     13881475.83      2124981.19     13881483.45
      2125025.00     13881517.44      2125080.57     13881477.71
      2125166.66     13881471.84      2125185.89     13881415.60
      2125272.70     13881330.11      2125295.16     13881324.68
      2125318.95     13881326.99      2125368.45     13881365.67
      2125378.41     13881367.18      2125391.70     13881358.70
      2125514.22     13881234.68      2125522.47     13881218.95
      2125528.98     13881176.65      2125538.63     13881161.79
      2125664.96     13881035.99      2125681.58     13881033.90
      2125730.67     13881072.56      2125775.00     13881075.00

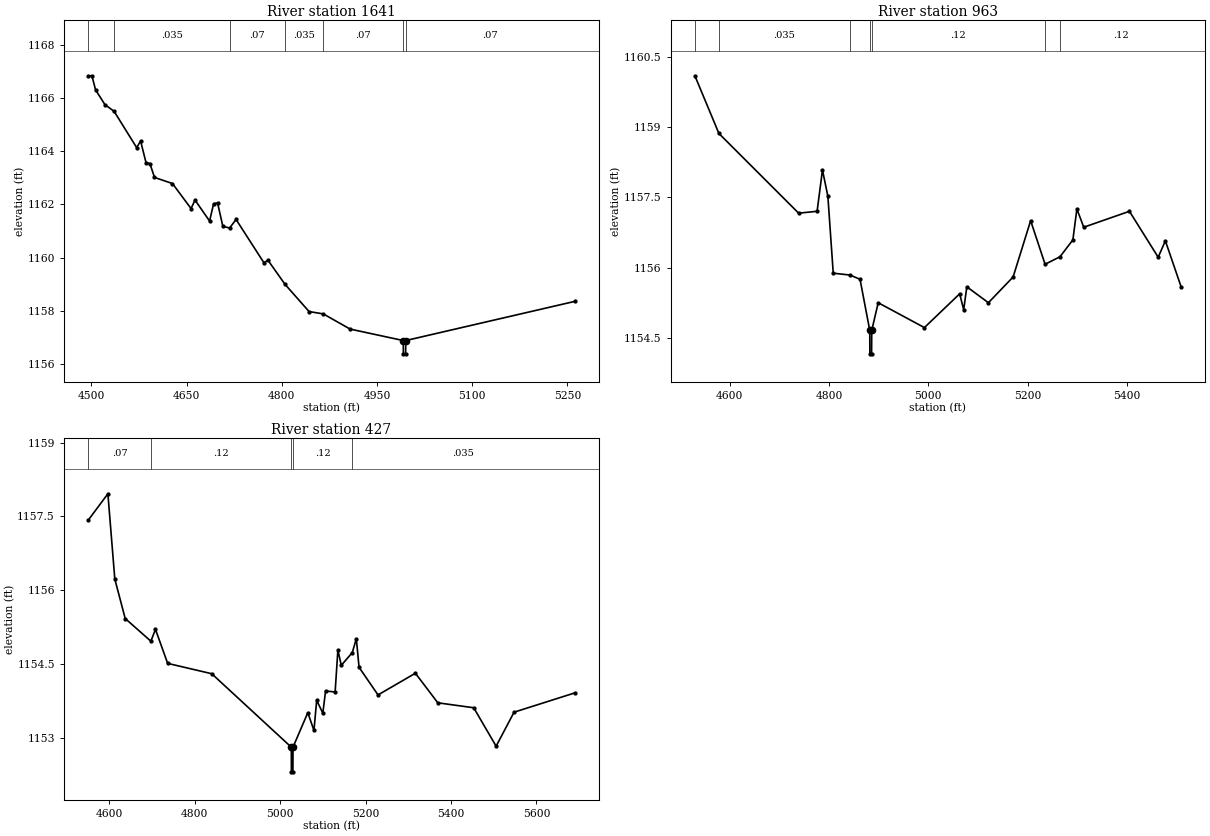
Type RM Length L Ch R = 1,1641,678,678,678
BEGIN DESCRIPTION:
Stream0072_DS 3.0
END DESCRIPTION:
XS GIS Cut Line= 2
      2124796.86     13882058.82      2124342.61     13881442.04
#Sta/Elev= 30
  4495.3 1166.83  4500.8 1166.83  4506.6 1166.30  4521.2 1165.75  4535.9 1165.49
  4571.3 1164.13  4577.5 1164.38  4586.0 1163.57  4592.2 1163.53  4599.4 1163.01
  4627.7 1162.78  4657.0 1161.84  4663.2 1162.16  4686.2 1161.37  4692.5 1162.02
  4698.8 1162.05  4707.1 1161.17  4717.8 1161.11  4727.9 1161.43  4771.9 1159.80
  4778.1 1159.90  4805.1 1158.99  4842.9 1157.97  4865.4 1157.88  4907.6 1157.31
  4991.3 1156.88  4991.5 1156.38  4995.0 1156.38  4995.3 1156.88  5261.3 1158.35
#Mann=7,-1,0
  4495.3    0.07       0  4535.9   0.035       0  4717.8    0.07       0
  4805.1   0.035       0  4865.4    0.07       0  4991.3    0.05       0
  4995.3    0.07       0
Bank Sta=4991.3,4995.3
Exp/Cntr=0.3,0.1

Type RM Length L Ch R = 1,963,536,536,536
BEGIN DESCRIPTION:
Stream0072_DS 2.0
END DESCRIPTION:
XS GIS Cut Line= 3
      2125259.46     13881912.98      2125080.17     13881475.00
      2124680.01     13881164.43
#Sta/Elev= 30
  4529.5 1160.09  4577.9 1158.86  4738.6 1157.16  4775.8 1157.20  4786.6 1158.08
  4797.5 1157.52  4808.3 1155.88  4842.2 1155.84  4862.3 1155.75  4881.9 1154.66
  4882.1 1154.16  4885.6 1154.16  4885.9 1154.66  4898.9 1155.25  4992.0 1154.72
  5063.1 1155.44  5071.2 1155.10  5077.5 1155.59  5121.0 1155.25  5170.8 1155.80
  5206.1 1157.00  5235.2 1156.07  5265.2 1156.23  5291.2 1156.59  5299.3 1157.25
  5313.1 1156.86  5405.2 1157.20  5463.1 1156.22  5477.6 1156.57  5509.3 1155.59
#Mann=7,-1,0
  4529.5    0.07       0  4577.9   0.035       0  4842.2    0.12       0
  4881.9    0.05       0  4885.9    0.12       0  5235.2   0.035       0
  5265.2    0.12       0
Bank Sta=4881.9,4885.9
Exp/Cntr=0.3,0.1

Type RM Length L Ch R = 1,427,0,0,0
BEGIN DESCRIPTION:
Stream0072_DS 1.0
END DESCRIPTION:
XS GIS Cut Line= 4
      2125450.00     13881700.01      2125513.68     13881304.54
      2125342.81     13881092.00      2124899.99     13880950.00
#Sta/Elev= 30
  4551.2 1157.43  4596.8 1157.96  4613.0 1156.23  4637.3 1155.43  4697.4 1154.97
  4708.2 1155.21  4736.7 1154.52  4839.9 1154.31  5026.2 1152.82  5026.4 1152.32
  5029.9 1152.32  5030.2 1152.82  5064.8 1153.52  5079.2 1153.16  5085.6 1153.77
  5100.0 1153.51  5106.4 1153.96  5128.8 1153.94  5135.2 1154.79  5143.2 1154.48
  5169.0 1154.74  5178.4 1155.02  5184.8 1154.44  5229.2 1153.88  5316.7 1154.32
  5369.2 1153.72  5453.2 1153.62  5505.7 1152.84  5547.7 1153.53  5689.5 1153.92
#Mann=5,-1,0
  4551.2    0.07       0  4697.4    0.12       0  5026.2    0.05       0
  5030.2    0.12       0  5169.0   0.035       0
Bank Sta=5026.2,5030.2
Exp/Cntr=0.3,0.1

Chan Stop Cuts=-1