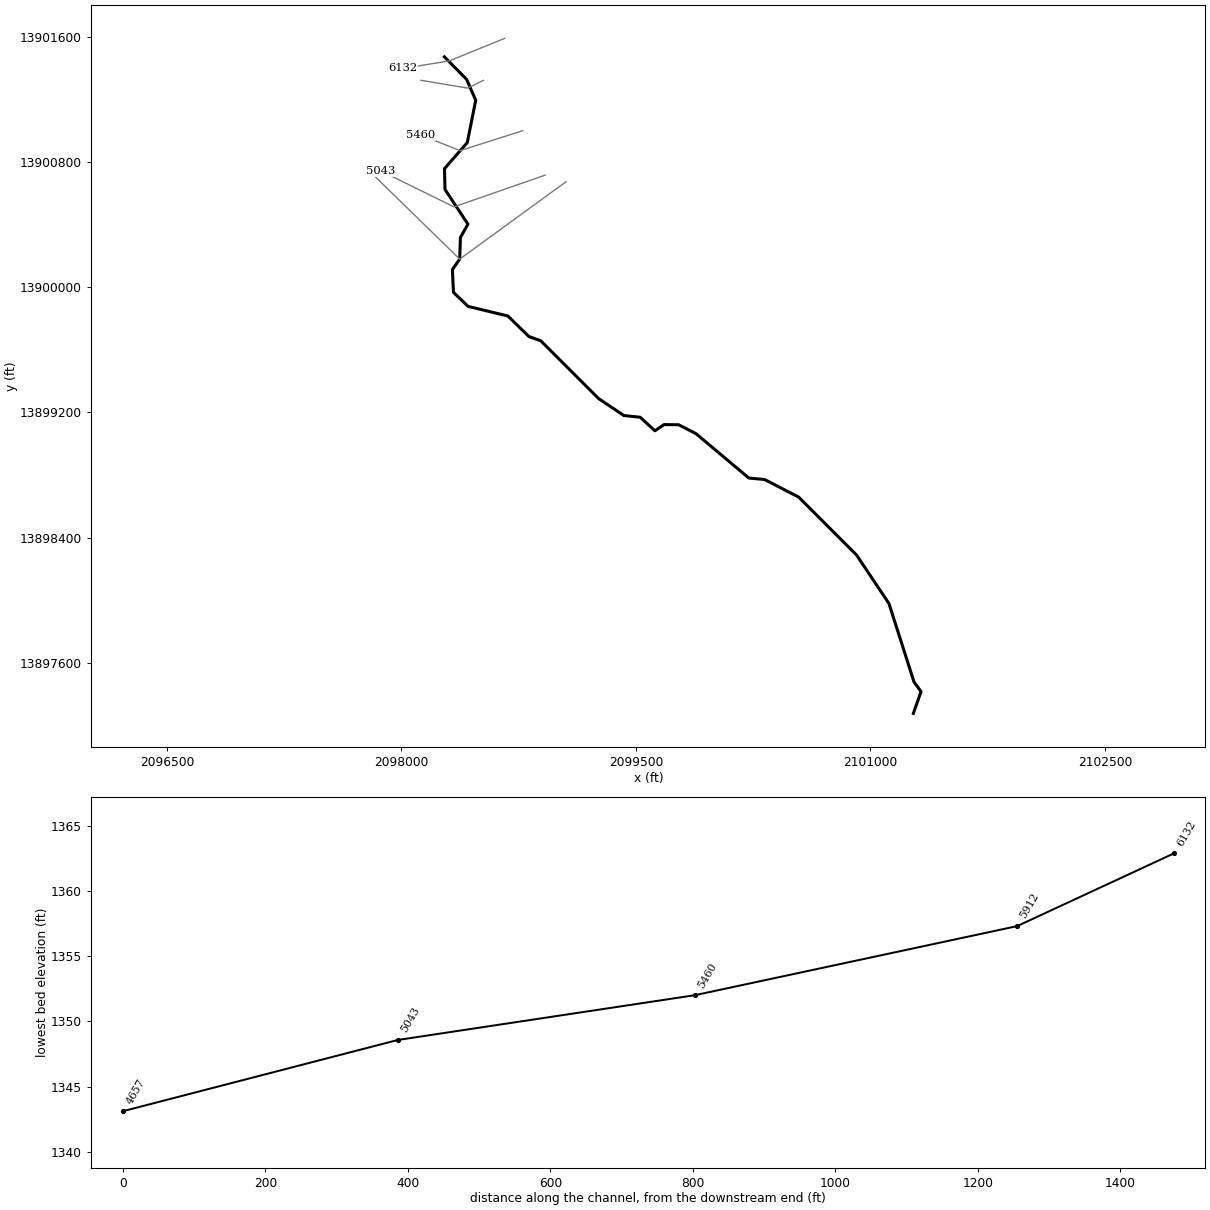
--- Stream0073_DS.prj (project) ---

Proj Title=Stream0073_DS Base Level Engineering
Current Plan=p01
Default Exp/Contr=0.3,0.1
English Units
Geom File=g01
Flow File=f01
Plan File=p01
Y Axis Title=Elevation
X Axis Title(PF)=Main Channel Distance
X Axis Title(XS)=Station
BEGIN DESCRIPTION:
Stream0073_DS
END DESCRIPTION:
DSS Export Rating Curves= 0
DSS Export Rating Curve Sorted= 0
DSS Export Volume Flow Curves= 0
DXF OffsetX= 0
DXF OffsetY= 0
DXF ScaleX= 1
DXF ScaleY= 10

--- Stream0073_DS.p01 (plan) ---

Plan Title=Multiple Run
Short Identifier=Multiple
Geom File=g01
Flow File=f01
Subcritical Flow
K Sum by GR= 0
Std Step Tol= 0.01
Critical Tol= 0.01
Num of Std Step Trials= 20
Max Error Tol= 0.3
Flow Tol Ratio= 0.001
Split Flow NTrial= 30
Split Flow Tol= 0.02
Split Flow Ratio= 0.02
Log Output Level= 0
Friction Slope Method= 1
Unsteady Friction Slope Method= 2
Unsteady Bridges Friction Slope Method= 1
Parabolic Critical Depth
Global Vel Dist=  1 , 1 , 1
Global Log Level= 0
CheckData=True
Encroach Param= -1, 0, 0, 0
BEGIN DESCRIPTION:
Multiple Run
END DESCRIPTION:

--- Stream0073_DS.f01 (steady flow) ---

Flow Title=Multiple
Number of Profiles=7
Profile Names=10-year,25-year,50-year,1pct_min,100-year,1pct_plu,500-year
River Rch & RM= Stream0073_DS,Reach-1,6132
     400     633     841     544    1086    2166    1783
River Rch & RM= Stream0073_DS,Reach-1,5912
     822    1359    1858    1232    2458    4904    4253
Boundary for River Rch & Prof#=Stream0073_DS,Reach-1,1
Up Type=0
Dn Type=3
Dn Slope=0.005
Boundary for River Rch & Prof#=Stream0073_DS,Reach-1,2
Up Type=0
Dn Type=3
Dn Slope=0.005
Boundary for River Rch & Prof#=Stream0073_DS,Reach-1,3
Up Type=0
Dn Type=3
Dn Slope=0.005
Boundary for River Rch & Prof#=Stream0073_DS,Reach-1,4
Up Type=0
Dn Type=3
Dn Slope=0.005
Boundary for River Rch & Prof#=Stream0073_DS,Reach-1,5
Up Type=0
Dn Type=3
Dn Slope=0.005
Boundary for River Rch & Prof#=Stream0073_DS,Reach-1,6
Up Type=0
Dn Type=3
Dn Slope=0.005
Boundary for River Rch & Prof#=Stream0073_DS,Reach-1,7
Up Type=0
Dn Type=3
Dn Slope=0.005

--- Stream0073_DS.g01 (geometry) ---

Geom Title=Existing Conditions
Program Version=4.10

River Reach=Stream0073_DS   ,Reach-1
Reach XY= 30
        2098275.       13901475.      2098416.87     13901331.06
      2098475.32     13901197.84      2098421.39      13900926.5
      2098275.37     13900759.84      2098278.74     13900626.56
      2098425.39     13900404.87       2098377.3     13900319.07
      2098372.73     13900180.94      2098326.21     13900114.49
       2098332.8     13899968.79      2098426.48     13899878.61
      2098681.17     13899817.14      2098815.32     13899685.78
      2098891.67     13899658.35      2099261.79     13899288.63
      2099422.58     13899180.54      2099527.43     13899169.45
      2099621.59     13899082.81      2099680.48     13899122.51
      2099773.41     13899121.32      2099884.68     13899064.24
      2100222.58     13898780.54      2100323.41     13898771.17
      2100541.68     13898658.36      2100911.37     13898288.21
      2101119.16     13897977.29      2101278.89     13897476.58
      2101324.27     13897414.32        2101275.       13897275.

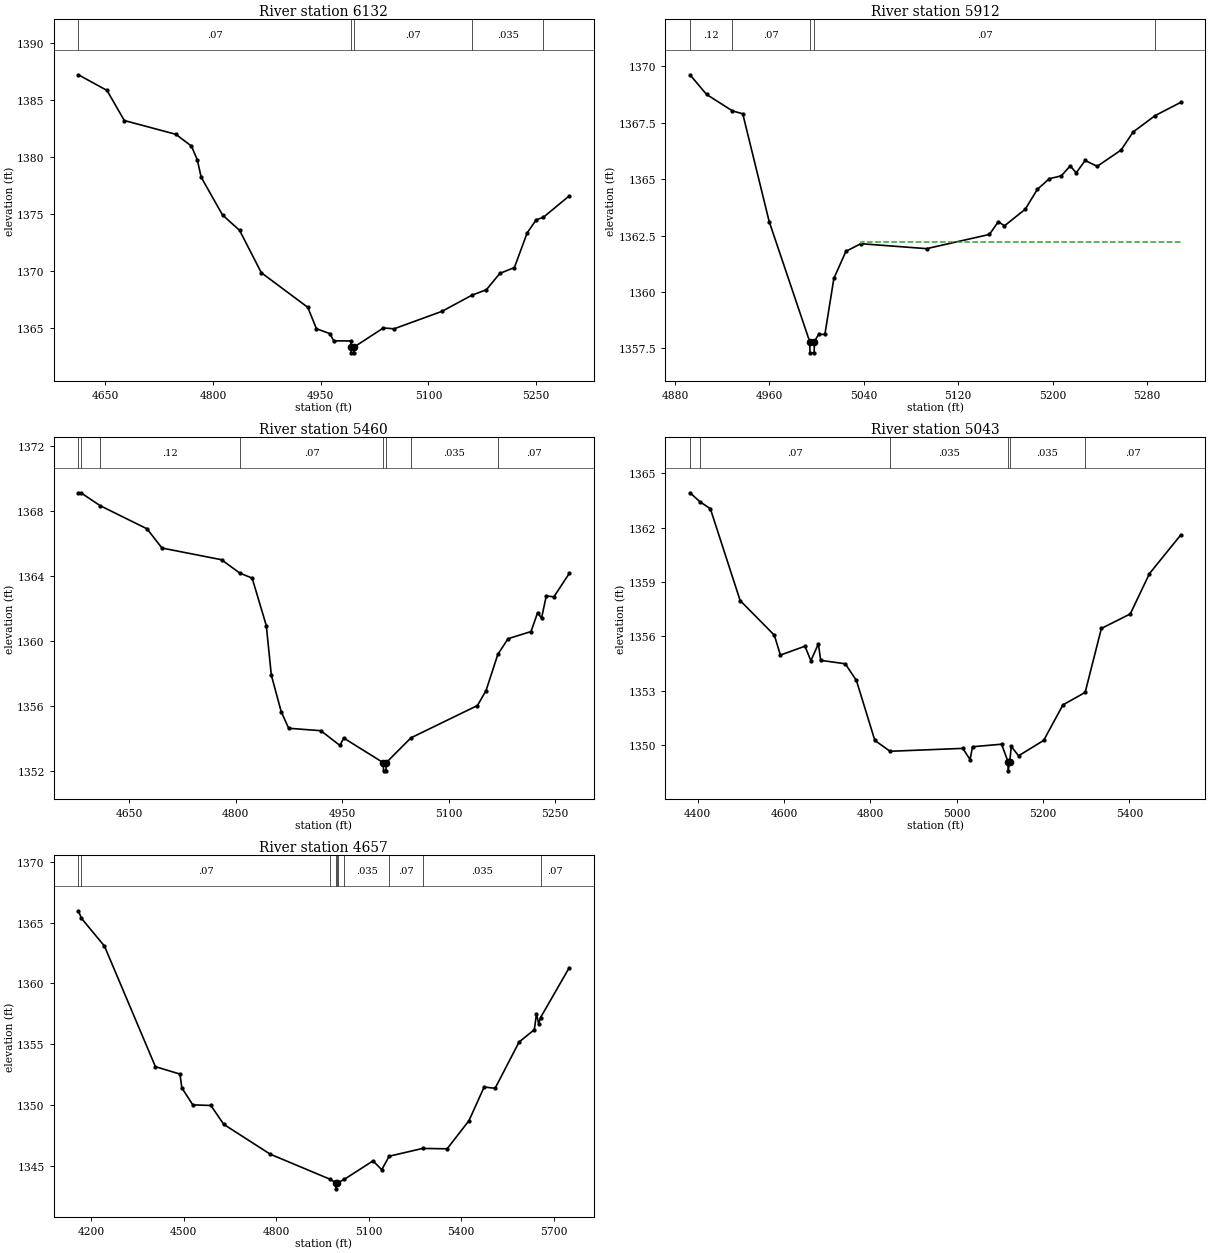
Type RM Length L Ch R = 1 ,6132    ,220,220,220
BEGIN DESCRIPTION:
Stream0073_DS 5.0
END DESCRIPTION:
XS GIS Cut Line= 3
      2098660.73     13901593.46      2098305.96     13901448.88
       2098009.6     13901401.05
#Sta/Elev= 30
  4612.7 1387.19  4652.5 1385.82  4676.6 1383.19  4748.5 1381.98  4770.1 1380.95
  4778.2 1379.75  4783.6 1378.23  4813.3 1374.93  4837.1 1373.58  4867.3 1369.88
    4932 1366.85    4944 1364.98  4962.7 1364.55  4968.1 1363.92  4992.1 1363.91
  4992.3 1363.37  4992.6 1362.87  4996.1 1362.87  4996.3 1363.37  5037.3 1365.05
    5052 1364.97  5118.8  1366.5  5160.4 1367.91  5180.6 1368.39  5199.4 1369.82
  5219.6 1370.33  5237.3 1373.35    5250 1374.51  5259.8 1374.72    5296  1376.6
#Mann= 5 ,-1 , 0
  4612.7     .07       0  4992.3     .05       0  4996.3     .07       0
  5160.4    .035       0  5259.8     .07       0
Bank Sta=4992.3,4996.3
XS Rating Curve= 0 ,0
Exp/Cntr=0.3,0.1

Type RM Length L Ch R = 1 ,5912    ,452,452,452
BEGIN DESCRIPTION:
Stream0073_DS 4.0
END DESCRIPTION:
XS GIS Cut Line= 3
        2098525.       13901325.        2098425.       13901275.
      2098125.04     13901324.99
#Sta/Elev= 30
  4892.8 1369.63  4906.8 1368.76  4928.7 1368.03  4937.5  1367.9  4959.9 1363.12
  4994.2  1357.8  4994.5  1357.3    4998  1357.3  4998.2  1357.8  5001.8 1358.12
  5007.1 1358.12  5014.7  1360.6  5024.9  1361.8  5037.5 1362.14  5093.3 1361.92
  5146.5 1362.55  5154.1 1363.12  5159.2 1362.93  5176.9 1363.67  5187.1 1364.55
  5197.2 1365.02  5207.4 1365.15    5215 1365.59    5220 1365.28  5227.6 1365.83
  5237.8 1365.57    5258 1366.29  5268.2 1367.09  5286.9 1367.82  5308.7 1368.41
#Mann= 5 ,-1 , 0
  4892.8     .12       0  4928.7     .07       0  4994.2     .05       0
  4998.2     .07       0  5286.9    .035       0
#XS Ineff= 2 , 0
       0                 5038.05       0  1362.2
Permanent Ineff=
       F       F
Bank Sta=4994.2,4998.2
XS Rating Curve= 0 ,0
Exp/Cntr=0.3,0.1

Type RM Length L Ch R = 1 ,5460    ,417,417,417
BEGIN DESCRIPTION:
Stream0073_DS 3.0
END DESCRIPTION:
XS GIS Cut Line= 3
      2098777.14     13901002.92        2098375.       13900875.
      2098124.96     13900975.02
#Sta/Elev= 30
  4578.6 1369.12  4582.1 1369.12  4609.1 1368.33  4675.3  1366.9  4696.3 1365.72
  4780.2    1365  4805.8 1364.18  4823.3 1363.87  4843.2 1360.95  4850.3  1357.9
  4864.2 1355.65  4874.7 1354.63    4920 1354.48    4947 1353.57  4952.2 1354.03
    5008 1352.51  5008.3 1352.01  5011.8 1352.01    5012 1352.51  5046.9 1354.04
  5140.6 1356.03  5152.7 1356.95  5169.3 1359.18  5183.7 1360.14    5216 1360.58
  5225.4 1361.75  5230.8  1361.4  5237.5 1362.77  5248.3 1362.72  5269.9 1364.16
#Mann= 8 ,-1 , 0
  4578.6     .12       0  4582.1     .07       0  4609.1     .12       0
  4805.8     .07       0    5008     .05       0    5012     .07       0
  5046.9    .035       0  5169.3     .07       0
Bank Sta=5008,5012
XS Rating Curve= 0 ,0
Exp/Cntr=0.3,0.1

Type RM Length L Ch R = 1 ,5043    ,386,386,386
BEGIN DESCRIPTION:
Stream0073_DS 2.0
END DESCRIPTION:
XS GIS Cut Line= 3
      2098919.54     13900718.21      2098335.79     13900515.32
      2097869.75     13900744.64
#Sta/Elev= 30
    4382 1363.93  4405.3 1363.43  4429.2 1363.05  4498.2 1357.98  4577.4 1356.07
  4591.5 1354.97  4648.4 1355.46  4662.1 1354.66  4679.5 1355.59  4684.8 1354.68
  4741.8 1354.49  4767.6 1353.57  4810.3 1350.26  4845.5 1349.66  5014.1 1349.82
    5031  1349.2  5036.6 1349.91    5104 1350.05  5118.9 1349.08  5119.1 1348.58
  5122.9 1349.08  5126.4 1349.93  5143.3 1349.41  5201.5 1350.26  5246.1 1352.22
  5297.6 1352.91  5335.2 1356.44  5402.1 1357.24  5446.7 1359.47  5519.4 1361.61
#Mann= 6 ,-1 , 0
    4382     .12       0  4405.3     .07       0  4845.5    .035       0
  5118.9    .035       0  5122.9    .035       0  5297.6     .07       0
Bank Sta=5118.9,5122.9
XS Rating Curve= 0 ,0
Exp/Cntr=0.3,0.1

Type RM Length L Ch R = 1 ,4657    ,0,0,0
BEGIN DESCRIPTION:
Stream0073_DS 1.0
END DESCRIPTION:
XS GIS Cut Line= 3
      2099053.15     13900676.24      2098372.73     13900180.94
      2097835.07     13900705.56
#Sta/Elev= 30
  4158.4 1365.97  4168.3 1365.35  4242.9 1363.07  4408.3 1353.16  4487.9 1352.55
    4494 1351.42  4529.6 1350.02  4588.3 1349.97    4630 1348.42  4780.7 1345.97
  4974.8 1343.91  4993.5 1343.62  4993.8 1343.12  4997.5 1343.62    5000 1343.62
  5021.8 1343.91  5114.4 1345.42  5142.7 1344.69  5166.7  1345.8  5275.2 1346.44
  5354.9 1346.41  5425.6 1348.72    5475 1351.49  5510.5 1351.38  5588.2 1355.18
  5637.8  1356.2  5644.8  1357.5  5651.9 1356.69  5658.1  1357.2  5751.2  1361.3
#Mann= 10 ,-1 , 0
  4158.4    .035       0  4168.3     .07       0  4974.8    .035       0
  4993.5     .05       0  4997.5    .035       0    5000     .07       0
  5021.8    .035       0  5166.7     .07       0  5275.2    .035       0
  5658.1     .07       0
Bank Sta=4993.5,4997.5
XS Rating Curve= 0 ,0
Exp/Cntr=0.3,0.1

Chan Stop Cuts=-1
Use User Specified Reach Order=0
Composite Channel Slope=5