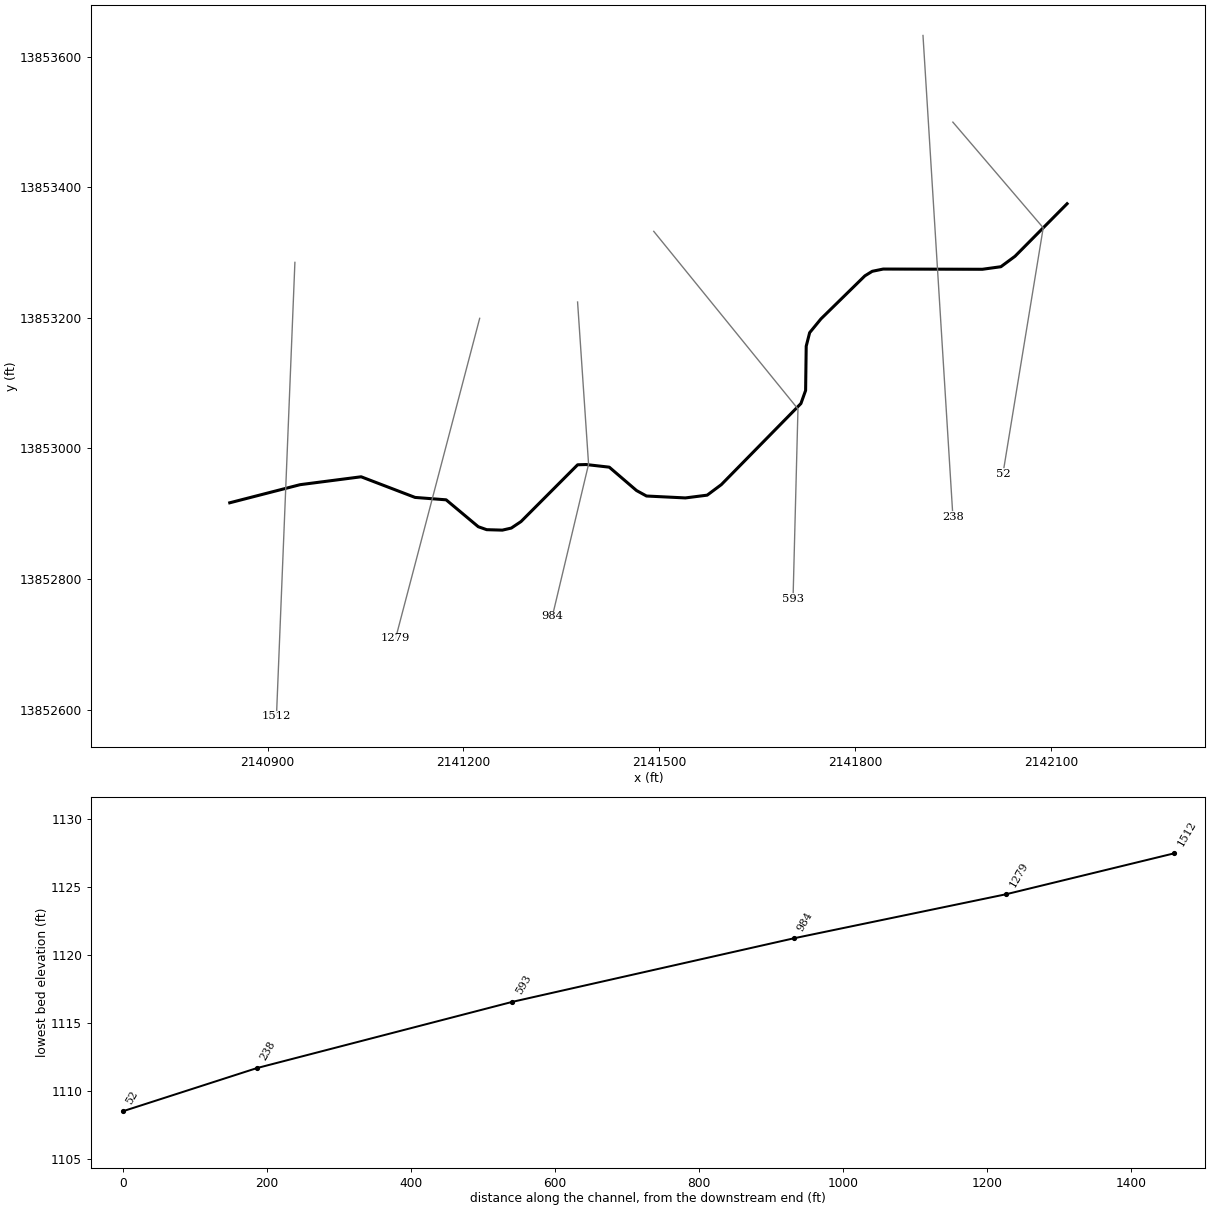
--- Stream0076_DS.prj (project) ---

Proj Title=Stream0076_DS Base Level Engineering
Current Plan=p01
Default Exp/Contr=0.3,0.1
English Units
Geom File=g01
Flow File=f01
Plan File=p01
BEGIN DESCRIPTION:
Stream0076_DS
END DESCRIPTION:

--- Stream0076_DS.p01 (plan) ---

Plan Title=Multiple Run
Short Identifier=Multiple
Geom File=g01
Flow File=f01
Subcritical Flow
K Sum by GR= 0
Std Step Tol= 0.01
Critical Tol= 0.01
Num of Std Step Trials= 20
Max Error Tol= 0.3
Flow Tol Ratio= 0.001
Split Flow NTrial= 30
Split Flow Tol= 0.02
Split Flow Ratio= 0.02
Log Output Level= 0
Friction Slope Method= 1
Unsteady Friction Slope Method= 2
Unsteady Bridges Friction Slope Method= 1
Parabolic Critical Depth
Global Vel Dist=  1 , 1 , 1
Global Log Level= 0
CheckData=True
Encroach Param= -1, 0, 0, 0
BEGIN DESCRIPTION:
Multiple Run
END DESCRIPTION:

--- Stream0076_DS.f01 (steady flow) ---

Flow Title=Multiple
Number of Profiles=7
Profile Names=10-year,25-year,50-year,1pct_min,100-year,1pct_plu,500-year
River Rch & RM= Stream0076_DS,Reach-1,1512
     476     769    1034     676    1350    2693    2270
Boundary for River Rch & Prof#=Stream0076_DS,Reach-1,1
Up Type=0
Dn Type=3
Dn Slope=0.005
Boundary for River Rch & Prof#=Stream0076_DS,Reach-1,2
Up Type=0
Dn Type=3
Dn Slope=0.005
Boundary for River Rch & Prof#=Stream0076_DS,Reach-1,3
Up Type=0
Dn Type=3
Dn Slope=0.005
Boundary for River Rch & Prof#=Stream0076_DS,Reach-1,4
Up Type=0
Dn Type=3
Dn Slope=0.005
Boundary for River Rch & Prof#=Stream0076_DS,Reach-1,5
Up Type=0
Dn Type=3
Dn Slope=0.005
Boundary for River Rch & Prof#=Stream0076_DS,Reach-1,6
Up Type=0
Dn Type=3
Dn Slope=0.005
Boundary for River Rch & Prof#=Stream0076_DS,Reach-1,7
Up Type=0
Dn Type=3
Dn Slope=0.005

--- Stream0076_DS.g01 (geometry) ---

Geom Title=Existing Conditions

River Reach=Stream0076_DS,Reach-1
Reach XY= 30
      2140841.94     13852916.75      2140949.73     13852944.51
      2141043.29     13852956.61      2141125.94     13852924.98
      2141173.51     13852921.31      2141222.76     13852880.09
      2141235.68     13852875.56      2141259.67     13852874.87
      2141273.39     13852878.03      2141288.25     13852888.00
      2141375.00     13852975.00      2141387.96     13852975.38
      2141423.49     13852971.35      2141465.26     13852935.52
      2141480.51     13852927.14      2141540.09     13852924.22
      2141573.51     13852928.46      2141595.16     13852944.58
      2141717.14     13853068.83      2141724.33     13853088.91
      2141725.25     13853156.72      2141730.52     13853177.44
      2141747.85     13853198.58      2141815.17     13853264.53
      2141826.45     13853271.47      2141843.21     13853274.91
      2141995.18     13853274.57      2142023.56     13853278.48
      2142045.21     13853294.50      2142125.00     13853375.00

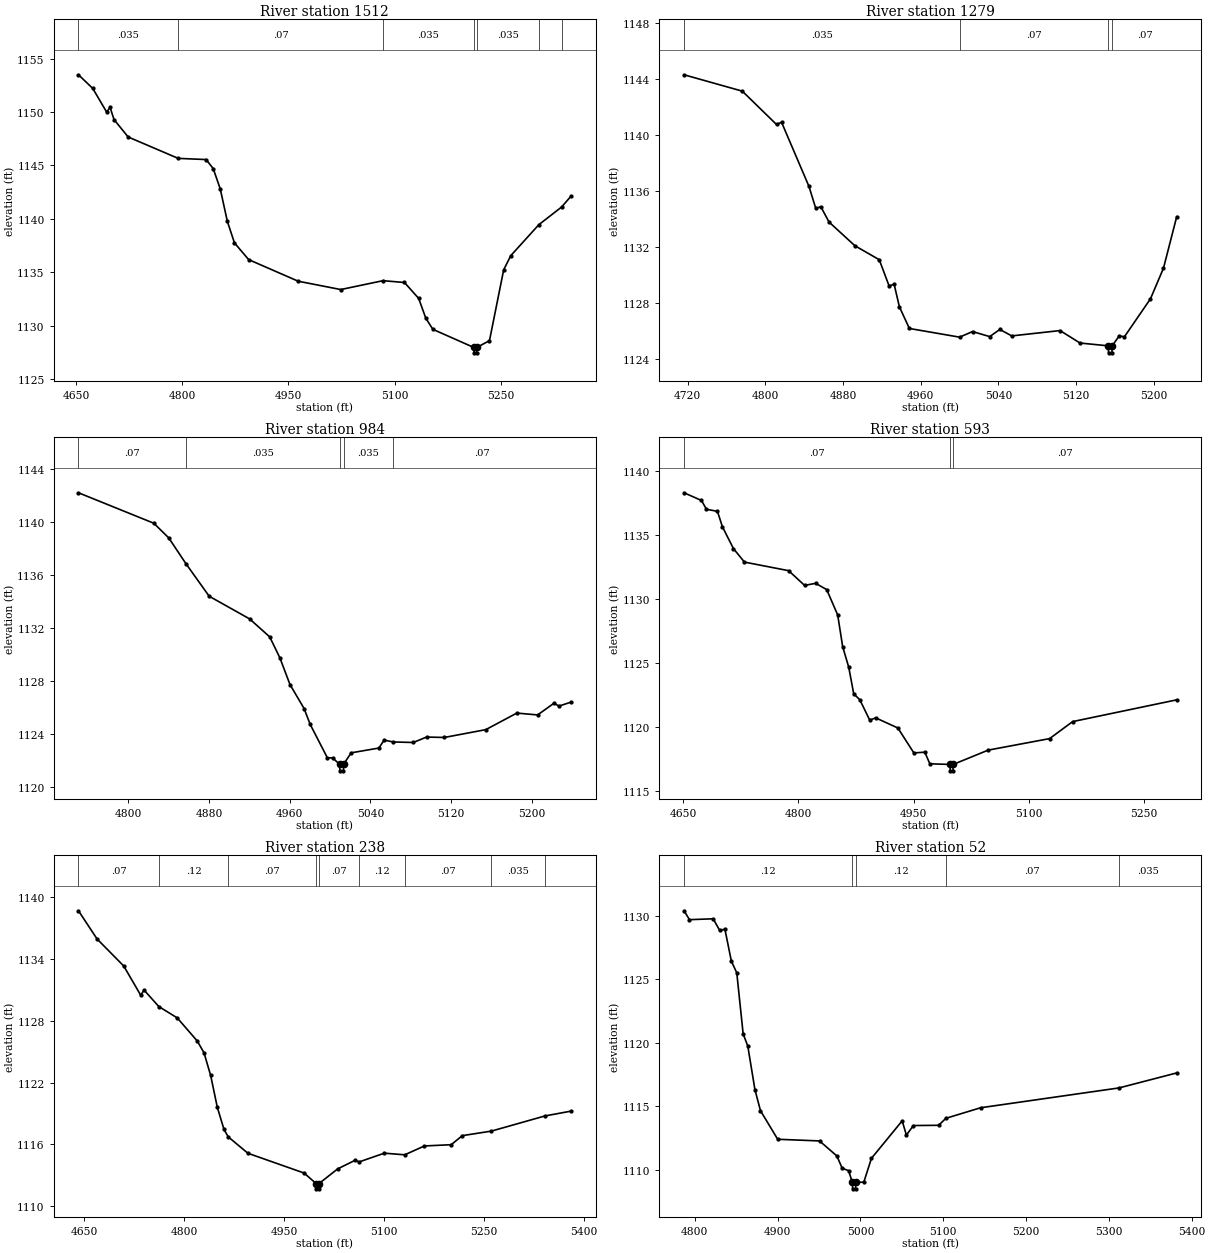
Type RM Length L Ch R = 1,1512,233,233,233
BEGIN DESCRIPTION:
Stream 0076 5.0
END DESCRIPTION:
XS GIS Cut Line= 2
      2140941.79     13853285.16      2140913.55     13852589.73
#Sta/Elev= 30
  4653.4 1153.48  4673.6 1152.20  4693.1 1150.00  4698.1 1150.42  4703.6 1149.29
  4723.6 1147.66  4794.3 1145.66  4833.7 1145.55  4843.7 1144.71  4853.7 1142.80
  4863.7 1139.77  4873.7 1137.76  4893.8 1136.19  4963.8 1134.17  5023.9 1133.39
  5083.6 1134.22  5113.9 1134.05  5134.0 1132.56  5144.0 1130.72  5154.0 1129.67
  5212.0 1127.97  5212.3 1127.47  5215.8 1127.47  5216.0 1127.97  5234.0 1128.61
  5254.1 1135.24  5264.1 1136.56  5303.8 1139.46  5335.9 1141.11  5349.4 1142.14
#Mann=7,-1,0
  4653.4   0.035       0  4794.3    0.07       0  5083.6   0.035       0
  5212.0    0.05       0  5216.0   0.035       0  5303.8    0.07       0
  5335.9   0.035       0
Bank Sta=5212,5216
Exp/Cntr=0.3,0.1

Type RM Length L Ch R = 1,1279,295,295,295
BEGIN DESCRIPTION:
Stream 0076 4.0
END DESCRIPTION:
XS GIS Cut Line= 2
      2141224.91     13853199.39      2141096.04     13852708.84
#Sta/Elev= 30
  4716.4 1144.33  4776.4 1143.16  4811.6 1140.78  4816.8 1140.94  4845.0 1136.36
  4852.0 1134.79  4857.2 1134.91  4865.7 1133.81  4892.3 1132.12  4917.4 1131.12
  4927.5 1129.25  4932.7 1129.37  4938.1 1127.76  4948.4 1126.21  5000.1 1125.59
  5013.4 1125.99  5031.1 1125.63  5041.5 1126.14  5053.8 1125.68  5103.5 1126.06
  5124.1 1125.17  5153.2 1124.97  5153.4 1124.47  5156.9 1124.47  5157.2 1124.97
  5164.5 1125.69  5169.7 1125.61  5196.6 1128.33  5210.0 1130.52  5223.6 1134.19
#Mann=4,-1,0
  4716.4   0.035       0  5000.1    0.07       0  5153.2   0.035       0
  5157.2    0.07       0
Bank Sta=5153.2,5157.2
Exp/Cntr=0.3,0.1

Type RM Length L Ch R = 1,984,391,391,391
BEGIN DESCRIPTION:
Stream 0076 3.0
END DESCRIPTION:
XS GIS Cut Line= 3
      2141374.93     13853224.41      2141391.78     13852975.86
      2141336.22     13852742.61
#Sta/Elev= 30
  4750.4 1142.22  4825.2 1139.92  4840.0 1138.81  4857.0 1136.87  4880.1 1134.41
  4920.2 1132.70  4940.2 1131.34  4950.3 1129.75  4960.3 1127.74  4974.3 1125.93
  4980.3 1124.74  4997.4 1122.21  5002.5 1122.21  5009.5 1121.73  5009.8 1121.23
  5013.3 1121.23  5013.5 1121.73  5021.0 1122.59  5048.5 1122.95  5053.7 1123.55
  5062.7 1123.41  5082.6 1123.37  5095.8 1123.78  5113.5 1123.75  5154.6 1124.34
  5185.4 1125.59  5206.0 1125.45  5222.2 1126.33  5227.3 1126.12  5239.3 1126.42
#Mann=5,-1,0
  4750.4    0.07       0  4857.0   0.035       0  5009.5   0.035       0
  5013.5   0.035       0  5062.7    0.07       0
Bank Sta=5009.5,5013.5
Exp/Cntr=0.3,0.1

Type RM Length L Ch R = 1,593,355,355,355
BEGIN DESCRIPTION:
Stream 0076 2.0
END DESCRIPTION:
XS GIS Cut Line= 3
      2141491.65     13853332.68      2141712.62     13853060.54
      2141705.07     13852769.59
#Sta/Elev= 30
  4651.0 1138.30  4673.7 1137.70  4680.2 1137.01  4694.5 1136.85  4701.0 1135.64
  4715.4 1133.93  4729.7 1132.88  4787.2 1132.21  4808.0 1131.06  4822.4 1131.22
  4836.8 1130.73  4851.1 1128.75  4857.6 1126.27  4865.5 1124.66  4872.0 1122.58
  4879.9 1122.12  4892.8 1120.53  4900.7 1120.70  4929.5 1119.91  4950.3 1117.96
  4964.6 1118.02  4971.1 1117.11  4997.5 1117.06  4997.7 1116.56  5001.2 1116.56
  5001.5 1117.06  5047.1 1118.18  5127.1 1119.08  5157.1 1120.41  5292.6 1122.11
#Mann=3,-1,0
  4651.0    0.07       0  4997.5    0.05       0  5001.5    0.07       0
Bank Sta=4997.5,5001.5
Exp/Cntr=0.3,0.1

Type RM Length L Ch R = 1,238,186,186,186
BEGIN DESCRIPTION:
Stream 0076 1.0
END DESCRIPTION:
XS GIS Cut Line= 2
      2141904.19     13853632.79      2141950.02     13852895.42
#Sta/Elev= 30
  4641.5 1138.66  4669.3 1135.93  4709.4 1133.30  4734.8 1130.47  4739.8 1130.97
  4762.0 1129.37  4789.6 1128.27  4819.6 1126.03  4829.7 1124.89  4839.7 1122.69
  4849.7 1119.59  4859.7 1117.45  4866.1 1116.73  4895.6 1115.14  4979.9 1113.22
  4998.0 1112.19  4998.2 1111.69  5001.7 1111.69  5002.0 1112.19  5030.0 1113.62
  5056.3 1114.46  5062.3 1114.30  5100.2 1115.15  5130.7 1114.99  5160.3 1115.85
  5200.4 1115.97  5217.1 1116.85  5260.7 1117.29  5341.0 1118.76  5380.3 1119.23
#Mann=9,-1,0
  4641.5    0.07       0  4762.0    0.12       0  4866.1    0.07       0
  4998.0    0.05       0  5002.0    0.07       0  5062.3    0.12       0
  5130.7    0.07       0  5260.7   0.035       0  5341.0    0.07       0
Bank Sta=4998,5002
Exp/Cntr=0.3,0.1

Type RM Length L Ch R = 1,52,0,0,0
BEGIN DESCRIPTION:
Stream 0076 0.0
END DESCRIPTION:
XS GIS Cut Line= 3
      2141949.97     13853500.03      2142088.41     13853338.15
      2142026.68     13852961.27
#Sta/Elev= 30
  4787.0 1130.40  4793.6 1129.70  4822.2 1129.77  4829.9 1128.87  4836.4 1128.94
  4844.1 1126.45  4850.7 1125.51  4858.4 1120.71  4864.0 1119.75  4872.6 1116.33
  4879.3 1114.67  4900.1 1112.42  4950.6 1112.29  4971.5 1111.11  4978.0 1110.14
  4985.7 1109.95  4990.3 1109.02  4990.6 1108.52  4994.1 1108.52  4994.3 1109.02
  5004.1 1109.05  5013.3 1110.92  5050.4 1113.87  5055.5 1112.75  5064.0 1113.50
  5094.4 1113.52  5103.2 1114.07  5145.1 1114.90  5312.2 1116.46  5381.9 1117.64
#Mann=5,-1,0
  4787.0    0.12       0  4990.3    0.05       0  4994.3    0.12       0
  5103.2    0.07       0  5312.2   0.035       0
Bank Sta=4990.3,4994.3
Exp/Cntr=0.3,0.1

Chan Stop Cuts=-1