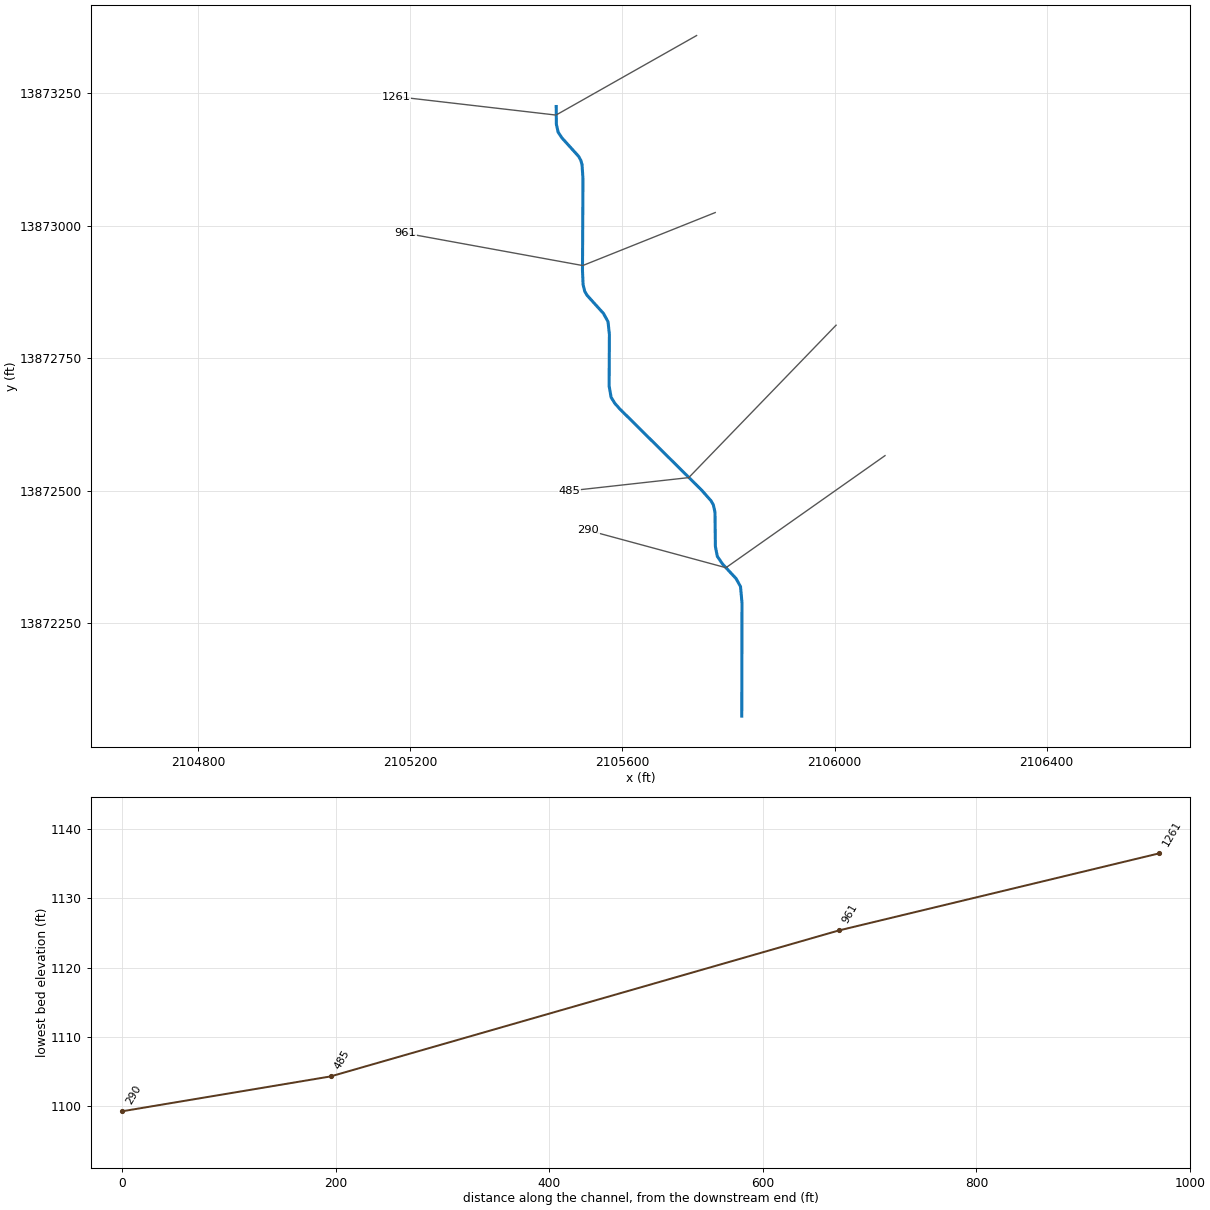
--- Stream0107_DS.prj (project) ---

Proj Title=Stream0107_DS Base Level Engineering
Current Plan=p01
Default Exp/Contr=0.3,0.1
English Units
Geom File=g01
Flow File=f01
Plan File=p01
BEGIN DESCRIPTION:
Stream0107_DS
END DESCRIPTION:

--- Stream0107_DS.p01 (plan) ---

Plan Title=Multiple Run
Short Identifier=Multiple
Geom File=g01
Flow File=f01
Subcritical Flow
K Sum by GR= 0
Std Step Tol= 0.01
Critical Tol= 0.01
Num of Std Step Trials= 20
Max Error Tol= 0.3
Flow Tol Ratio= 0.001
Split Flow NTrial= 30
Split Flow Tol= 0.02
Split Flow Ratio= 0.02
Log Output Level= 0
Friction Slope Method= 1
Unsteady Friction Slope Method= 2
Unsteady Bridges Friction Slope Method= 1
Parabolic Critical Depth
Global Vel Dist=  1 , 1 , 1
Global Log Level= 0
CheckData=True
Encroach Param= -1, 0, 0, 0
BEGIN DESCRIPTION:
Multiple Run
END DESCRIPTION:

--- Stream0107_DS.f01 (steady flow) ---

Flow Title=Multiple
Number of Profiles=7
Profile Names=10-year,25-year,50-year,1pct_min,100-year,1pct_plu,500-year
River Rch & RM= Stream0107_DS,Reach-1,1261
     326     510     672     432     862    1720    1395
Boundary for River Rch & Prof#=Stream0107_DS,Reach-1,1
Up Type=0
Dn Type=3
Dn Slope=0.005
Boundary for River Rch & Prof#=Stream0107_DS,Reach-1,2
Up Type=0
Dn Type=3
Dn Slope=0.005
Boundary for River Rch & Prof#=Stream0107_DS,Reach-1,3
Up Type=0
Dn Type=3
Dn Slope=0.005
Boundary for River Rch & Prof#=Stream0107_DS,Reach-1,4
Up Type=0
Dn Type=3
Dn Slope=0.005
Boundary for River Rch & Prof#=Stream0107_DS,Reach-1,5
Up Type=0
Dn Type=3
Dn Slope=0.005
Boundary for River Rch & Prof#=Stream0107_DS,Reach-1,6
Up Type=0
Dn Type=3
Dn Slope=0.005
Boundary for River Rch & Prof#=Stream0107_DS,Reach-1,7
Up Type=0
Dn Type=3
Dn Slope=0.005

--- Stream0107_DS.g01 (geometry) ---

Geom Title=Existing Conditions

River Reach=Stream0107_DS,Reach-1
Reach XY= 30
      2105475.00     13873225.00      2105475.28     13873191.46
      2105478.65     13873176.51      2105486.06     13873165.44
      2105517.11     13873131.16      2105521.40     13873123.51
      2105523.73     13873115.38      2105525.45     13873088.82
      2105524.55     13872915.72      2105525.68     13872888.92
      2105528.78     13872876.57      2105533.14     13872868.94
      2105564.14     13872834.64      2105572.73     13872819.06
      2105575.32     13872795.13      2105574.82     13872697.65
      2105578.54     13872676.47      2105585.48     13872665.20
      2105594.61     13872654.84      2105748.82     13872501.87
      2105767.14     13872481.17      2105771.39     13872473.50
      2105774.48     13872459.78      2105775.25     13872395.10
      2105778.86     13872376.60      2105788.83     13872361.87
      2105814.15     13872334.65      2105822.63     13872319.47
      2105825.44     13872288.82      2105825.00     13872075.00

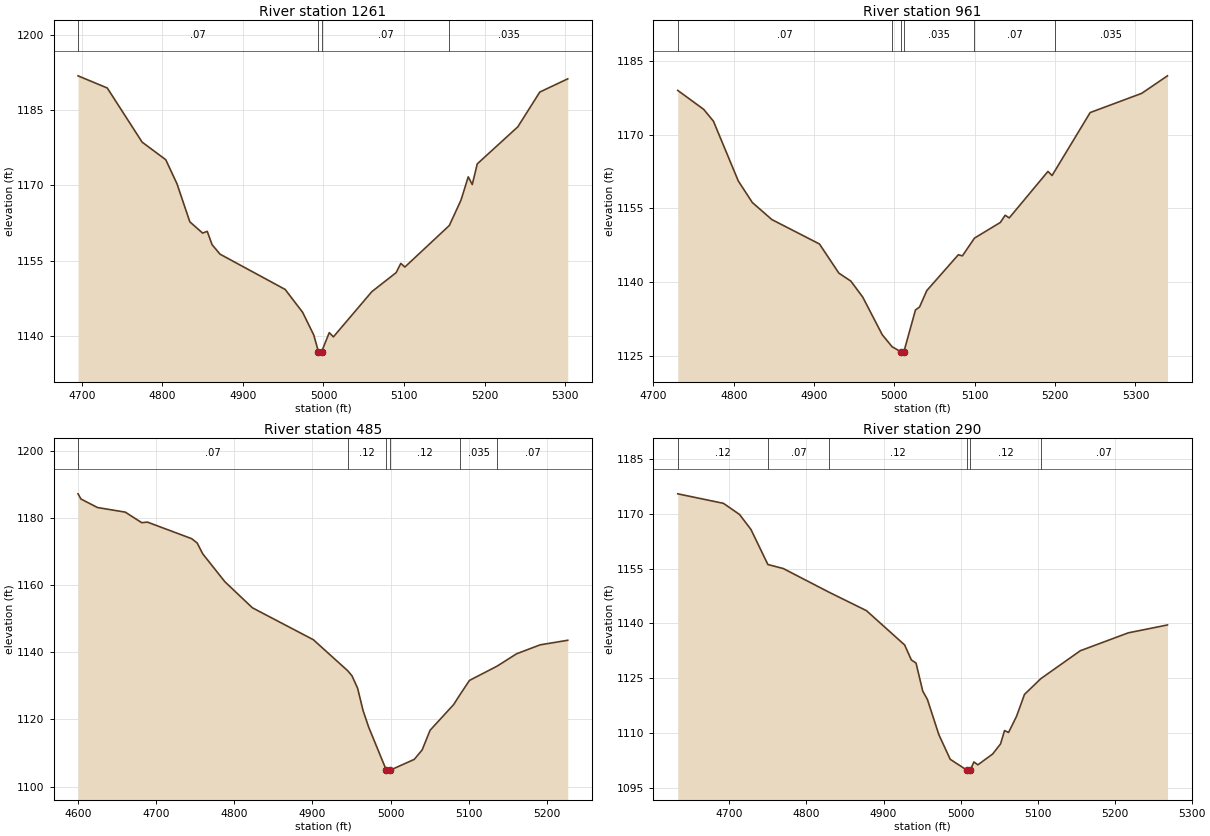
Type RM Length L Ch R = 1,1261,300,300,300
BEGIN DESCRIPTION:
Stream0107_DS 3.0
END DESCRIPTION:
XS GIS Cut Line= 3
      2105739.80     13873358.88      2105474.59     13873208.86
      2105173.40     13873243.75
#Sta/Elev= 30
  4695.3 1191.81  4731.6 1189.39  4774.9 1178.62  4804.2 1175.13  4818.2 1170.32
  4834.1 1162.77  4850.0 1160.53  4855.7 1160.88  4861.7 1158.23  4871.6 1156.34
  4952.4 1149.33  4974.1 1144.78  4988.0 1140.24  4993.7 1136.96  4994.0 1136.46
  4997.7 1136.96  5007.2 1140.74  5012.3 1139.89  5060.0 1148.88  5090.2 1152.67
  5096.0 1154.51  5101.0 1153.78  5156.2 1162.04  5170.7 1167.09  5179.7 1171.72
  5184.7 1170.19  5190.9 1174.30  5241.2 1181.66  5268.5 1188.58  5303.2 1191.21
#Mann=4,-1,0
  4695.3    0.07       0  4993.7    0.05       0  4997.7    0.07       0
  5156.2   0.035       0
Bank Sta=4993.7,4997.7
Exp/Cntr=0.3,0.1

Type RM Length L Ch R = 1,961,476,476,476
BEGIN DESCRIPTION:
Stream0107_DS 2.0
END DESCRIPTION:
XS GIS Cut Line= 3
      2105774.95     13873024.98      2105525.00     13872925.00
      2105190.34     13872986.10
#Sta/Elev= 30
  4730.4 1179.04  4762.7 1175.18  4774.8 1172.77  4805.7 1160.61  4823.2 1156.21
  4847.5 1152.74  4906.7 1147.77  4930.9 1141.83  4945.8 1140.21  4960.6 1136.95
  4984.8 1129.31  4997.1 1126.85  5007.8 1125.84  5008.0 1125.34  5011.8 1125.84
  5026.2 1134.33  5031.3 1134.94  5040.3 1138.28  5079.5 1145.57  5084.6 1145.35
  5099.6 1148.96  5131.8 1152.15  5137.8 1153.62  5142.9 1153.08  5191.1 1162.55
  5196.2 1161.71  5200.3 1162.82  5243.6 1174.53  5307.7 1178.44  5339.8 1182.01
#Mann=6,-1,0
  4730.4    0.07       0  4997.1   0.035       0  5007.8   0.035       0
  5011.8   0.035       0  5099.6    0.07       0  5200.3   0.035       0
Bank Sta=5007.8,5011.8
Exp/Cntr=0.3,0.1

Type RM Length L Ch R = 1,485,195,195,195
BEGIN DESCRIPTION:
Stream0107_DS 1.0
END DESCRIPTION:
XS GIS Cut Line= 3
      2106002.90     13872812.51      2105725.00     13872525.00
      2105500.04     13872500.00
#Sta/Elev= 30
  4600.4 1187.16  4604.2 1185.61  4625.3 1183.08  4660.8 1181.71  4681.9 1178.57
  4689.1 1178.74  4745.7 1173.81  4752.7 1172.54  4759.9 1169.28  4788.2 1160.98
  4823.4 1153.22  4901.3 1143.72  4945.3 1134.47  4950.7 1132.97  4957.9 1129.29
  4964.9 1122.61  4972.1 1117.67  4994.8 1104.79  4995.0 1104.29  4998.8 1104.79
  5030.4 1108.09  5040.5 1110.93  5050.6 1116.76  5080.8 1124.43  5088.9 1127.39
  5100.9 1131.59  5136.3 1135.85  5161.2 1139.53  5191.4 1142.20  5226.6 1143.55
#Mann=6,-1,0
  4600.4    0.07       0  4945.3    0.12       0  4994.8    0.05       0
  4998.8    0.12       0  5088.9   0.035       0  5136.3    0.07       0
Bank Sta=4994.8,4998.8
Exp/Cntr=0.3,0.1

Type RM Length L Ch R = 1,290,0,0,0
BEGIN DESCRIPTION:
Stream0107_DS 0.0
END DESCRIPTION:
XS GIS Cut Line= 3
      2106095.22     13872566.47      2105795.12     13872355.05
      2105535.87     13872425.32
#Sta/Elev= 30
  4632.9 1175.44  4692.2 1172.84  4713.1 1169.79  4727.9 1165.69  4749.9 1156.09
  4769.8 1155.00  4829.5 1148.49  4877.8 1143.47  4927.4 1134.08  4936.1 1129.99
  4942.2 1129.12  4950.9 1121.46  4957.0 1119.14  4971.8 1109.54  4986.6 1102.78
  5008.5 1099.77  5008.7 1099.27  5012.5 1099.77  5017.3 1102.06  5022.5 1101.27
  5041.6 1104.22  5051.9 1106.99  5057.1 1110.64  5062.3 1110.12  5072.6 1114.51
  5083.0 1120.55  5104.3 1124.87  5155.5 1132.50  5217.7 1137.39  5268.6 1139.55
#Mann=6,-1,0
  4632.9    0.12       0  4749.9    0.07       0  4829.5    0.12       0
  5008.5    0.05       0  5012.5    0.12       0  5104.3    0.07       0
Bank Sta=5008.5,5012.5
Exp/Cntr=0.3,0.1

Chan Stop Cuts=-1