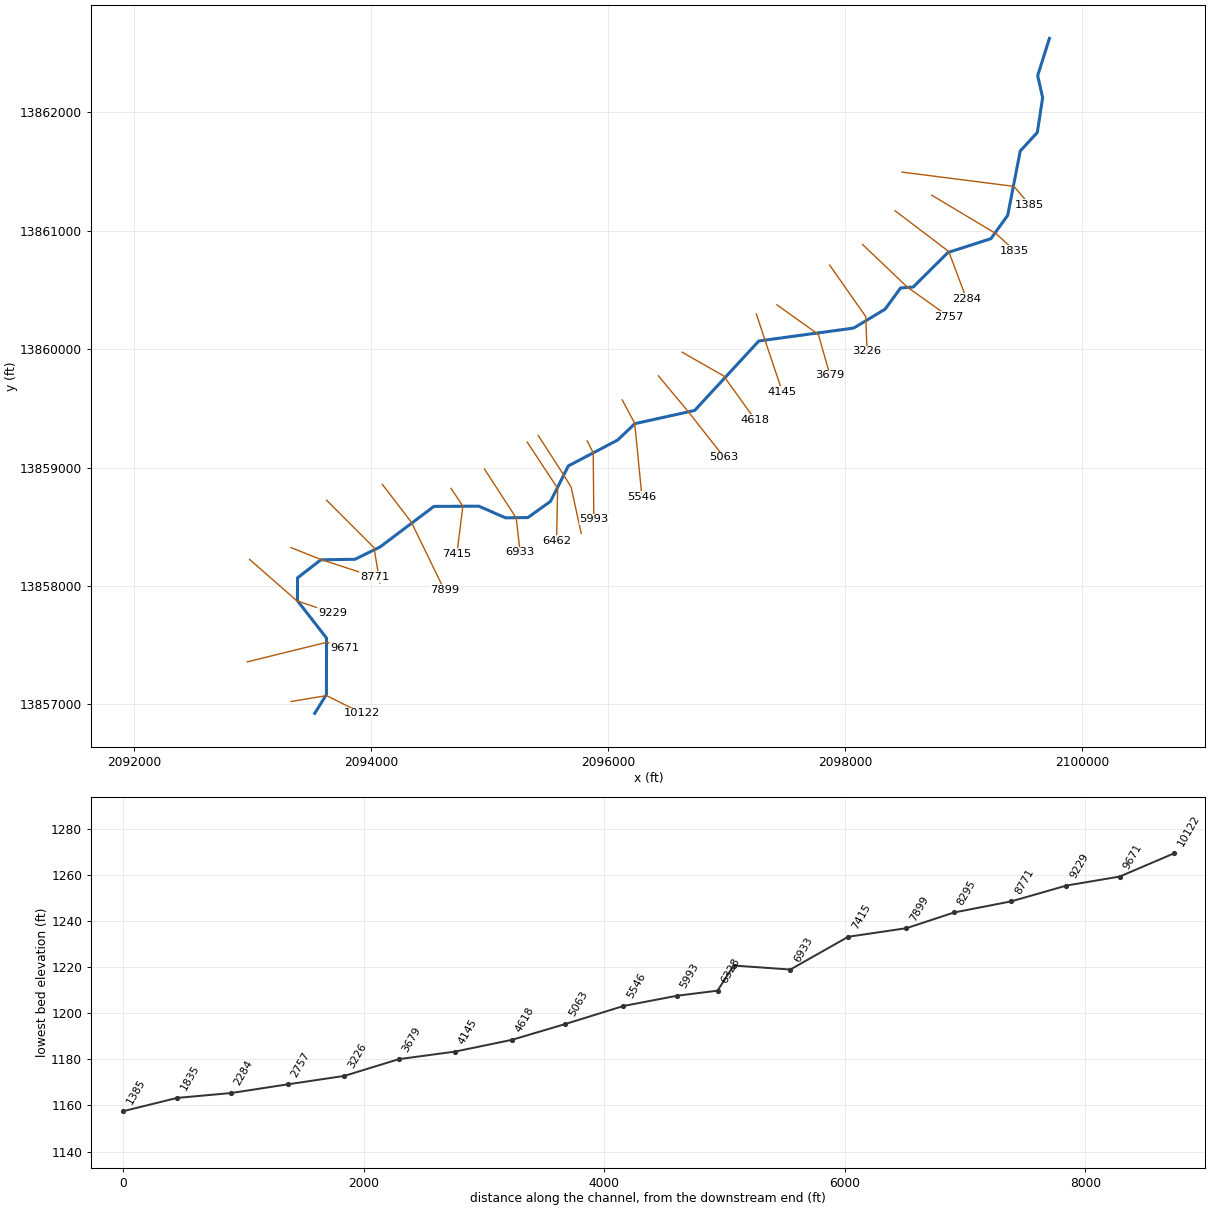
--- Stream0175_DS.prj (project) ---

Proj Title=Stream0175_DS Base Level Engineering
Current Plan=p01
Default Exp/Contr=0.3,0.1
English Units
Geom File=g01
Flow File=f01
Plan File=p01
BEGIN DESCRIPTION:
Stream0175_DS
END DESCRIPTION:

--- Stream0175_DS.p01 (plan) ---

Plan Title=Multiple Run
Short Identifier=Multiple
Geom File=g01
Flow File=f01
Subcritical Flow
K Sum by GR= 0
Std Step Tol= 0.01
Critical Tol= 0.01
Num of Std Step Trials= 20
Max Error Tol= 0.3
Flow Tol Ratio= 0.001
Split Flow NTrial= 30
Split Flow Tol= 0.02
Split Flow Ratio= 0.02
Log Output Level= 0
Friction Slope Method= 1
Unsteady Friction Slope Method= 2
Unsteady Bridges Friction Slope Method= 1
Parabolic Critical Depth
Global Vel Dist=  1 , 1 , 1
Global Log Level= 0
CheckData=True
Encroach Param= -1, 0, 0, 0
BEGIN DESCRIPTION:
Multiple Run
END DESCRIPTION:

--- Stream0175_DS.f01 (steady flow) ---

Flow Title=Multiple
Number of Profiles=7
Profile Names=10-year,25-year,50-year,1pct_min,100-year,1pct_plu,500-year
River Rch & RM= Stream0175_DS,Reach-1,10122
    1408    2418    3392    2307    4602    9183    8376
River Rch & RM= Stream0175_DS,Reach-1,9229
    1876    3260    4610    3155    6295   12559   11610
River Rch & RM= Stream0175_DS,Reach-1,2284
    1835    3193    4519    3094    6173   12318   11402
Boundary for River Rch & Prof#=Stream0175_DS,Reach-1,1
Up Type=0
Dn Type=3
Dn Slope=0.005
Boundary for River Rch & Prof#=Stream0175_DS,Reach-1,2
Up Type=0
Dn Type=3
Dn Slope=0.005
Boundary for River Rch & Prof#=Stream0175_DS,Reach-1,3
Up Type=0
Dn Type=3
Dn Slope=0.005
Boundary for River Rch & Prof#=Stream0175_DS,Reach-1,4
Up Type=0
Dn Type=3
Dn Slope=0.005
Boundary for River Rch & Prof#=Stream0175_DS,Reach-1,5
Up Type=0
Dn Type=3
Dn Slope=0.005
Boundary for River Rch & Prof#=Stream0175_DS,Reach-1,6
Up Type=0
Dn Type=3
Dn Slope=0.005
Boundary for River Rch & Prof#=Stream0175_DS,Reach-1,7
Up Type=0
Dn Type=3
Dn Slope=0.005

--- Stream0175_DS.g01 (geometry) ---

Geom Title=Existing Conditions

River Reach=Stream0175_DS,Reach-1
Reach XY= 30
      2093525.00     13856925.00      2093623.80     13857084.59
      2093624.46     13857561.14      2093378.75     13857876.55
      2093380.18     13858069.56      2093576.46     13858221.46
      2093865.35     13858226.36      2094077.30     13858330.83
      2094530.93     13858672.76      2094909.78     13858674.48
      2095134.66     13858576.38      2095323.53     13858578.55
      2095514.35     13858715.00      2095664.94     13859014.39
      2096081.17     13859232.86      2096226.50     13859371.39
      2096731.19     13859482.81      2097272.57     13860069.48
      2098073.53     13860178.55      2098338.57     13860338.47
      2098468.76     13860517.27      2098575.00     13860525.00
      2098868.94     13860816.86      2099231.07     13860933.13
      2099372.67     13861130.97      2099478.54     13861673.54
      2099622.83     13861830.44      2099667.44     13862125.00
      2099625.51     13862309.78      2099725.00     13862625.00

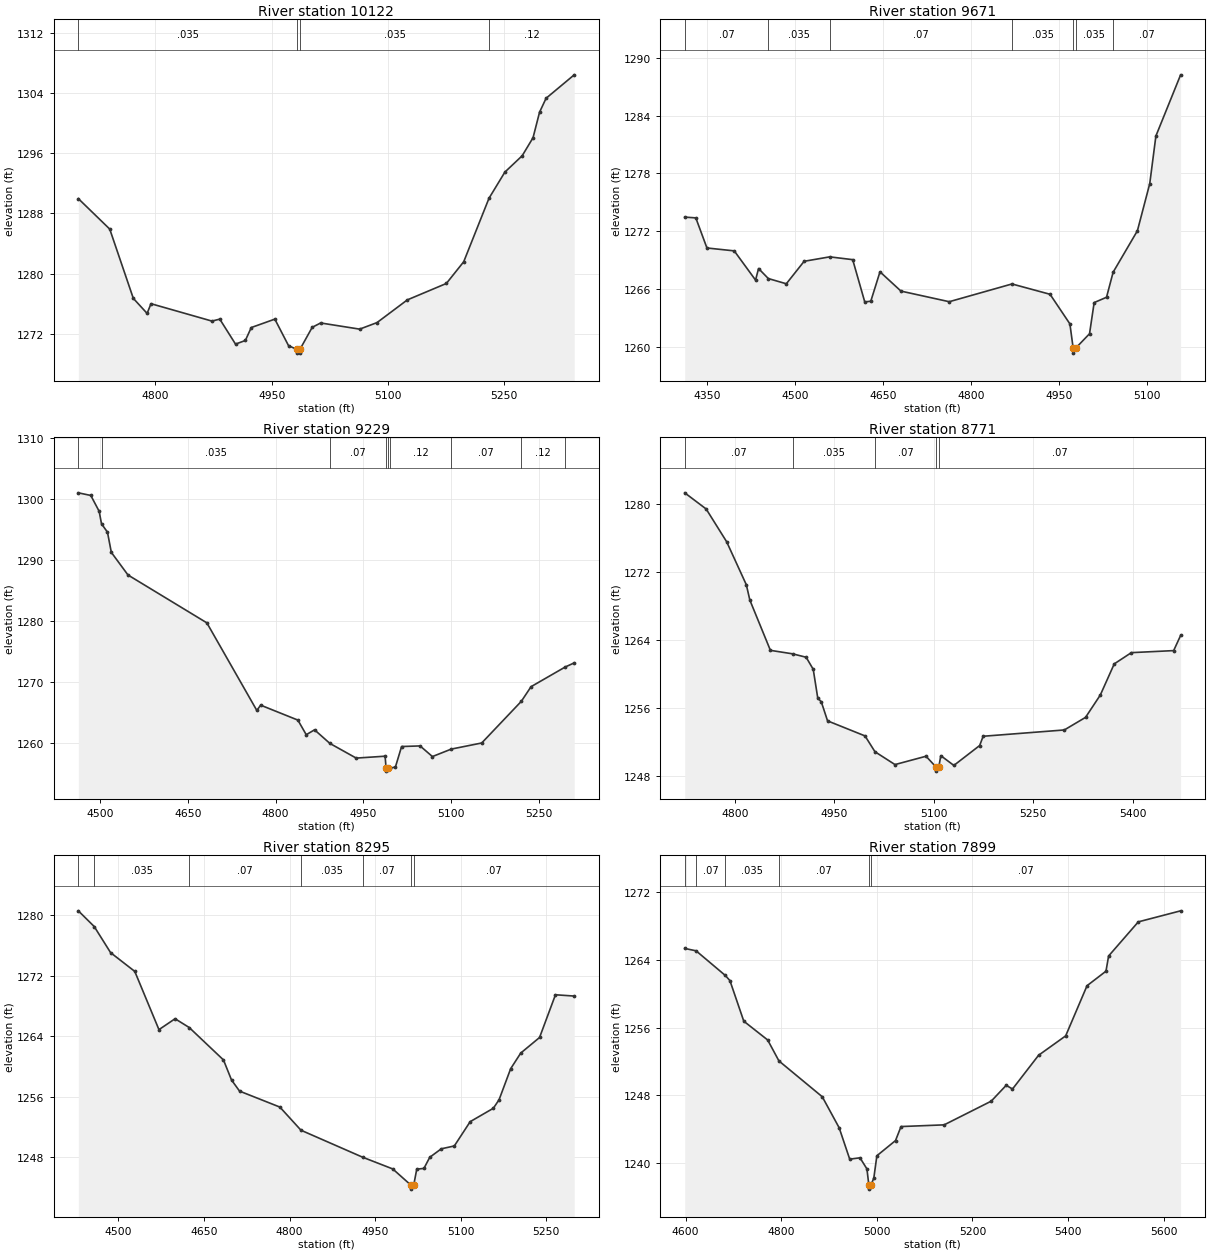
Type RM Length L Ch R = 1,10122,451,451,451
BEGIN DESCRIPTION:
Stream0175_DS 20.0
END DESCRIPTION:
XS GIS Cut Line= 3
      2093325.04     13857025.01      2093625.00     13857075.00
      2093924.99     13856925.00
#Sta/Elev= 30
  4700.6 1289.97  4741.1 1285.92  4771.5 1276.71  4789.3 1274.71  4794.3 1276.00
  4872.9 1273.69  4883.0 1273.95  4903.3 1270.63  4916.0 1271.11  4923.6 1272.83
  4954.0 1273.95  4971.7 1270.42  4982.4 1269.93  4982.7 1269.43  4986.2 1269.43
  4986.4 1269.93  5002.2 1272.86  5013.1 1273.44  5063.4 1272.62  5085.8 1273.49
  5124.9 1276.51  5175.2 1278.69  5197.6 1281.58  5230.2 1290.02  5250.7 1293.50
  5273.0 1295.67  5287.0 1298.07  5295.4 1301.46  5303.8 1303.31  5340.1 1306.43
#Mann=4,-1,0
  4700.6   0.035       0  4982.4   0.035       0  4986.4   0.035       0
  5230.2    0.12       0
Bank Sta=4982.4,4986.4
Exp/Cntr=0.3,0.1

Type RM Length L Ch R = 1,9671,442,442,442
BEGIN DESCRIPTION:
Stream0175_DS 19.0
END DESCRIPTION:
XS GIS Cut Line= 3
      2092956.67     13857360.05      2093625.00     13857525.00
      2093775.00     13857475.00
#Sta/Elev= 30
  4311.2 1273.47  4330.1 1273.39  4349.1 1270.27  4395.7 1269.97  4432.1 1266.94
  4437.2 1268.14  4453.9 1267.10  4484.6 1266.56  4515.0 1268.89  4558.7 1269.35
  4597.9 1269.06  4618.5 1264.68  4628.8 1264.75  4644.5 1267.80  4680.3 1265.80
  4762.7 1264.70  4869.8 1266.54  4934.8 1265.47  4968.7 1262.40  4974.3 1259.87
  4974.5 1259.37  4978.3 1259.87  5002.2 1261.38  5010.1 1264.61  5031.2 1265.16
  5042.5 1267.76  5083.9 1272.05  5105.0 1276.94  5115.5 1281.88  5157.7 1288.22
#Mann=7,-1,0
  4311.2    0.07       0  4453.9   0.035       0  4558.7    0.07       0
  4869.8   0.035       0  4974.3   0.035       0  4978.3   0.035       0
  5042.5    0.07       0
Bank Sta=4974.3,4978.3
Exp/Cntr=0.3,0.1

Type RM Length L Ch R = 1,9229,458,458,458
BEGIN DESCRIPTION:
Stream0175_DS 18.0
END DESCRIPTION:
XS GIS Cut Line= 3
      2092975.03     13858224.97      2093375.00     13857875.00
      2093675.00     13857775.00
#Sta/Elev= 30
  4462.8 1300.96  4484.1 1300.53  4498.4 1297.94  4502.4 1295.90  4512.6 1294.53
  4519.2 1291.23  4547.7 1287.53  4682.5 1279.71  4767.9 1265.40  4774.5 1266.26
  4838.1 1263.82  4852.4 1261.43  4866.6 1262.23  4892.8 1260.01  4937.8 1257.61
  4987.2 1257.92  4988.9 1255.98  4989.1 1255.48  4993.0 1255.98  4995.4 1255.98
  5004.8 1256.14  5015.4 1259.50  5047.0 1259.60  5068.1 1257.86  5100.3 1259.08
  5152.4 1260.08  5220.1 1266.89  5236.7 1269.28  5295.2 1272.50  5310.5 1273.17
#Mann=9,-1,0
  4462.8    0.07       0  4502.4   0.035       0  4892.8    0.07       0
  4988.9    0.05       0  4993.0    0.07       0  4995.4    0.12       0
  5100.3    0.07       0  5220.1    0.12       0  5295.2    0.07       0
Bank Sta=4988.9,4993
Exp/Cntr=0.3,0.1

Type RM Length L Ch R = 1,8771,476,476,476
BEGIN DESCRIPTION:
Stream0175_DS 17.0
END DESCRIPTION:
XS GIS Cut Line= 3
      2093325.03     13858324.99      2093575.00     13858225.00
      2094030.16     13858076.83
#Sta/Elev= 30
  4724.3 1281.35  4756.6 1279.45  4787.5 1275.60  4817.2 1270.54  4822.5 1268.74
  4853.5 1262.83  4887.0 1262.42  4907.4 1262.02  4918.1 1260.60  4924.9 1257.23
  4930.3 1256.77  4939.7 1254.54  4996.2 1252.77  5011.2 1250.91  5041.4 1249.40
  5088.2 1250.38  5103.1 1249.13  5103.4 1248.63  5107.5 1249.13  5110.5 1250.45
  5130.2 1249.30  5169.1 1251.64  5174.4 1252.73  5296.8 1253.47  5328.8 1254.95
  5351.1 1257.58  5372.1 1261.24  5397.9 1262.56  5461.7 1262.80  5472.2 1264.58
#Mann=5,-1,0
  4724.3    0.07       0  4887.0   0.035       0  5011.2    0.07       0
  5103.1   0.035       0  5107.5    0.07       0
Bank Sta=5103.1,5107.5
Exp/Cntr=0.3,0.1

Type RM Length L Ch R = 1,8295,396,396,396
BEGIN DESCRIPTION:
Stream0175_DS 16.0
END DESCRIPTION:
XS GIS Cut Line= 3
      2093625.01     13858724.99      2094025.00     13858325.00
      2094075.00     13858025.02
#Sta/Elev= 30
  4429.6 1280.59  4457.5 1278.51  4486.2 1275.06  4528.6 1272.58  4571.0 1264.88
  4599.3 1266.32  4624.1 1265.16  4684.2 1260.87  4698.3 1258.22  4712.4 1256.75
  4783.1 1254.64  4820.1 1251.58  4928.3 1248.01  4981.1 1246.46  5013.4 1244.29
  5013.7 1243.79  5017.8 1244.29  5023.2 1246.43  5035.8 1246.53  5046.0 1248.00
  5066.2 1249.12  5089.1 1249.50  5116.9 1252.71  5157.5 1254.48  5167.6 1255.61
  5187.9 1259.71  5205.6 1261.78  5238.6 1263.84  5266.5 1269.49  5299.4 1269.32
#Mann=7,-1,0
  4429.6    0.07       0  4457.5   0.035       0  4624.1    0.07       0
  4820.1   0.035       0  4928.3    0.07       0  5013.4    0.05       0
  5017.8    0.07       0
Bank Sta=5013.4,5017.8
Exp/Cntr=0.3,0.1

Type RM Length L Ch R = 1,7899,484,484,484
BEGIN DESCRIPTION:
Stream0175_DS 15.0
END DESCRIPTION:
XS GIS Cut Line= 3
      2094095.40     13858858.73      2094340.81     13858538.74
      2094617.87     13857968.77
#Sta/Elev= 30
  4598.4 1265.32  4622.1 1265.04  4683.2 1262.14  4692.9 1261.53  4721.9 1256.75
  4771.8 1254.54  4795.4 1252.07  4886.0 1247.85  4921.3 1244.20  4943.4 1240.50
  4964.9 1240.66  4979.4 1239.35  4983.4 1237.47  4983.7 1236.97  4987.9 1237.47
  4993.8 1238.27  5000.2 1240.90  5039.2 1242.69  5050.7 1244.34  5140.9 1244.54
  5239.3 1247.33  5270.7 1249.20  5283.8 1248.76  5338.4 1252.74  5395.0 1255.02
  5439.7 1260.93  5479.3 1262.64  5484.8 1264.43  5546.9 1268.45  5635.4 1269.75
#Mann=6,-1,0
  4598.4   0.035       0  4622.1    0.07       0  4683.2   0.035       0
  4795.4    0.07       0  4983.4    0.05       0  4987.9    0.07       0
Bank Sta=4983.4,4987.9
Exp/Cntr=0.3,0.1

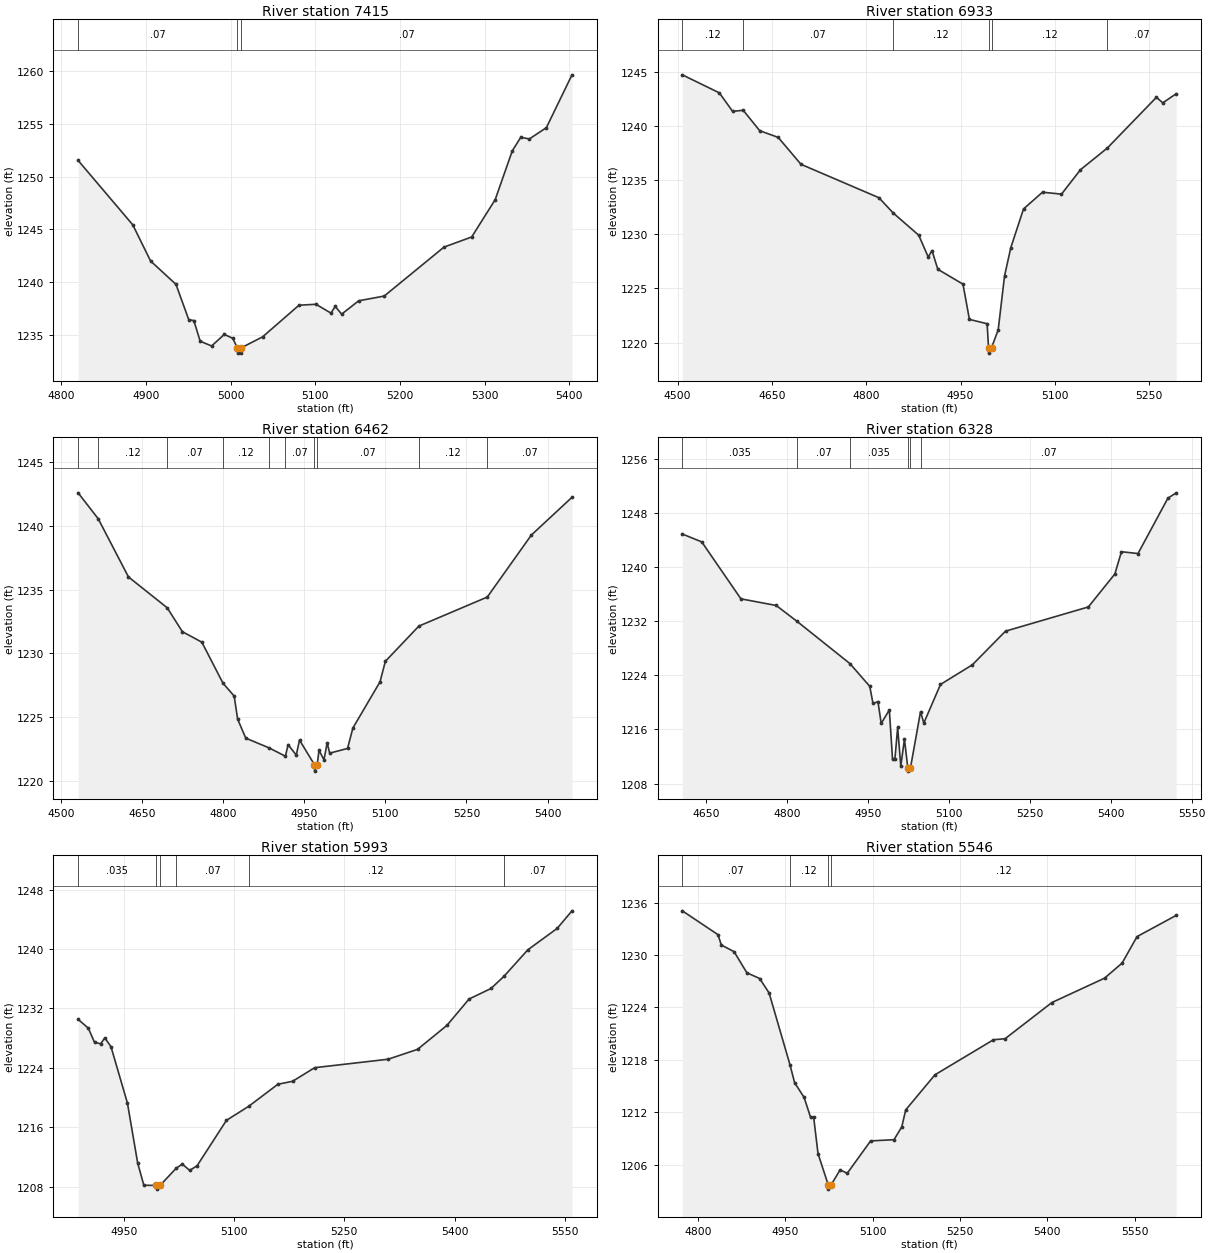
Type RM Length L Ch R = 1,7415,482,482,482
BEGIN DESCRIPTION:
Stream0175_DS 14.0
END DESCRIPTION:
XS GIS Cut Line= 3
      2094675.02     13858824.97      2094775.00     13858675.00
      2094724.99     13858274.96
#Sta/Elev= 30
  4819.8 1251.55  4884.4 1245.43  4905.4 1242.00  4935.4 1239.78  4950.5 1236.43
  4956.5 1236.34  4964.0 1234.38  4977.5 1233.93  4992.5 1235.03  5002.6 1234.65
  5007.8 1233.75  5008.2 1233.25  5012.1 1233.25  5012.4 1233.75  5037.8 1234.80
  5080.7 1237.80  5100.8 1237.89  5118.5 1237.05  5123.5 1237.69  5131.1 1236.95
  5151.2 1238.22  5181.4 1238.67  5252.0 1243.32  5284.7 1244.28  5312.5 1247.83
  5332.6 1252.45  5342.7 1253.75  5352.8 1253.59  5372.9 1254.66  5403.2 1259.68
#Mann=3,-1,0
  4819.8    0.07       0  5007.8    0.05       0  5012.4    0.07       0
Bank Sta=5007.8,5012.4
Exp/Cntr=0.3,0.1

Type RM Length L Ch R = 1,6933,471,471,471
BEGIN DESCRIPTION:
Stream0175_DS 13.0
END DESCRIPTION:
XS GIS Cut Line= 3
      2094957.26     13858988.30      2095225.00     13858575.00
      2095258.77     13858283.70
#Sta/Elev= 30
  4507.4 1244.77  4566.3 1243.10  4587.4 1241.39  4604.3 1241.49  4630.5 1239.60
  4659.9 1238.98  4696.2 1236.49  4820.1 1233.40  4843.0 1231.98  4883.5 1229.93
  4898.6 1227.91  4904.6 1228.51  4913.8 1226.78  4953.9 1225.40  4964.1 1222.14
  4992.3 1221.74  4994.5 1219.52  4994.8 1219.02  4999.3 1219.52  5009.9 1221.17
  5020.0 1226.17  5030.0 1228.79  5050.2 1232.36  5080.4 1233.91  5110.6 1233.73
  5140.8 1235.99  5183.4 1237.99  5261.6 1242.69  5271.7 1242.18  5293.1 1243.02
#Mann=6,-1,0
  4507.4    0.12       0  4604.3    0.07       0  4843.0    0.12       0
  4994.5    0.05       0  4999.3    0.12       0  5183.4    0.07       0
Bank Sta=4994.5,4999.3
Exp/Cntr=0.3,0.1

Type RM Length L Ch R = 1,6462,134,134,134
BEGIN DESCRIPTION:
Stream0175_DS 12.0
END DESCRIPTION:
XS GIS Cut Line= 3
      2095317.70     13859216.12      2095575.00     13858825.00
      2095565.77     13858379.96
#Sta/Elev= 30
  4531.8 1242.60  4568.9 1240.57  4624.9 1236.00  4696.5 1233.58  4724.7 1231.70
  4760.6 1230.88  4799.7 1227.66  4820.4 1226.65  4826.8 1224.84  4841.8 1223.35
  4884.6 1222.59  4915.2 1221.93  4920.1 1222.84  4935.2 1222.02  4941.2 1223.20
  4968.9 1221.26  4969.2 1220.76  4973.9 1221.26  4977.3 1222.40  4986.4 1221.65
  4992.4 1222.98  4997.0 1222.17  5030.0 1222.54  5040.0 1224.15  5090.0 1227.76
  5100.0 1229.38  5161.9 1232.14  5288.4 1234.42  5370.0 1239.29  5445.1 1242.25
#Mann=10,-1,0
  4531.8    0.07       0  4568.9    0.12       0  4696.5    0.07       0
  4799.7    0.12       0  4884.6   0.035       0  4915.2    0.07       0
  4968.9    0.05       0  4973.9    0.07       0  5161.9    0.12       0
  5288.4    0.07       0
Bank Sta=4968.9,4973.9
Exp/Cntr=0.3,0.1

Type RM Length L Ch R = 1,6328,335,335,335
BEGIN DESCRIPTION:
Stream0175_DS 11.5
END DESCRIPTION:
XS GIS Cut Line= 4
      2095411.06     13859271.14      2095624.78     13858940.14
      2095688.59     13858835.51      2095773.51     13858445.81
#Sta/Elev= 30
  4606.0 1244.91  4642.0 1243.74  4714.6 1235.32  4780.0 1234.34  4818.6 1231.99
  4916.7 1225.74  4953.4 1222.38  4959.4 1219.85  4968.6 1220.12  4974.6 1216.89
  4989.7 1218.89  4995.6 1211.59  5000.0 1211.59  5005.1 1216.30  5010.9 1210.59
  5017.7 1214.56  5023.9 1210.34  5024.3 1209.84  5028.9 1210.34  5047.5 1218.63
  5053.6 1216.95  5084.5 1222.66  5143.5 1225.56  5205.0 1230.54  5358.5 1234.12
  5407.7 1239.00  5419.9 1242.29  5450.6 1242.02  5505.9 1250.20  5521.4 1251.00
#Mann=6,-1,0
  4606.0   0.035       0  4818.6    0.07       0  4916.7   0.035       0
  5023.9   0.035       0  5028.9   0.035       0  5047.5    0.07       0
Bank Sta=5023.9,5028.9
Exp/Cntr=0.3,0.1

Type RM Length L Ch R = 1,5993,447,447,447
BEGIN DESCRIPTION:
Stream0175_DS 11.0
END DESCRIPTION:
XS GIS Cut Line= 3
      2095825.01     13859224.98      2095875.00     13859125.00
      2095880.30     13858564.90
#Sta/Elev= 30
  4887.9 1230.52  4901.8 1229.33  4910.2 1227.42  4918.6 1227.23  4924.2 1228.02
  4932.6 1226.84  4955.0 1219.24  4968.9 1211.19  4977.3 1208.18  4994.4 1208.16
  4994.7 1207.66  4999.4 1208.16  5021.4 1210.48  5029.7 1211.03  5039.7 1210.18
  5049.7 1210.80  5089.7 1216.92  5119.8 1218.80  5159.7 1221.78  5179.7 1222.18
  5209.7 1224.01  5309.7 1225.15  5349.7 1226.48  5389.7 1229.71  5419.7 1233.25
  5449.7 1234.68  5467.4 1236.33  5499.7 1239.88  5539.7 1242.77  5559.8 1245.13
#Mann=6,-1,0
  4887.9   0.035       0  4994.4   0.035       0  4999.4   0.035       0
  5021.4    0.07       0  5119.8    0.12       0  5467.4    0.07       0
Bank Sta=4994.4,4999.4
Exp/Cntr=0.3,0.1

Type RM Length L Ch R = 1,5546,483,483,483
BEGIN DESCRIPTION:
Stream0175_DS 10.0
END DESCRIPTION:
XS GIS Cut Line= 3
      2096119.90     13859571.84      2096225.00     13859375.00
      2096286.56     13858752.37
#Sta/Elev= 30
  4772.7 1235.05  4834.0 1232.32  4839.7 1231.14  4861.7 1230.37  4883.6 1227.96
  4905.6 1227.30  4921.8 1225.65  4957.7 1217.43  4965.7 1215.37  4982.0 1213.69
  4993.0 1211.43  4998.4 1211.43  5005.9 1207.26  5023.4 1203.69  5023.8 1203.19
  5028.5 1203.69  5043.9 1205.40  5056.1 1205.00  5096.3 1208.71  5136.5 1208.85
  5149.9 1210.33  5156.6 1212.26  5206.9 1216.28  5307.4 1220.29  5327.4 1220.41
  5407.8 1224.55  5498.3 1227.34  5528.4 1229.06  5554.2 1232.10  5621.5 1234.53
#Mann=4,-1,0
  4772.7    0.07       0  4957.7    0.12       0  5023.4    0.05       0
  5028.5    0.12       0
Bank Sta=5023.4,5028.5
Exp/Cntr=0.3,0.1

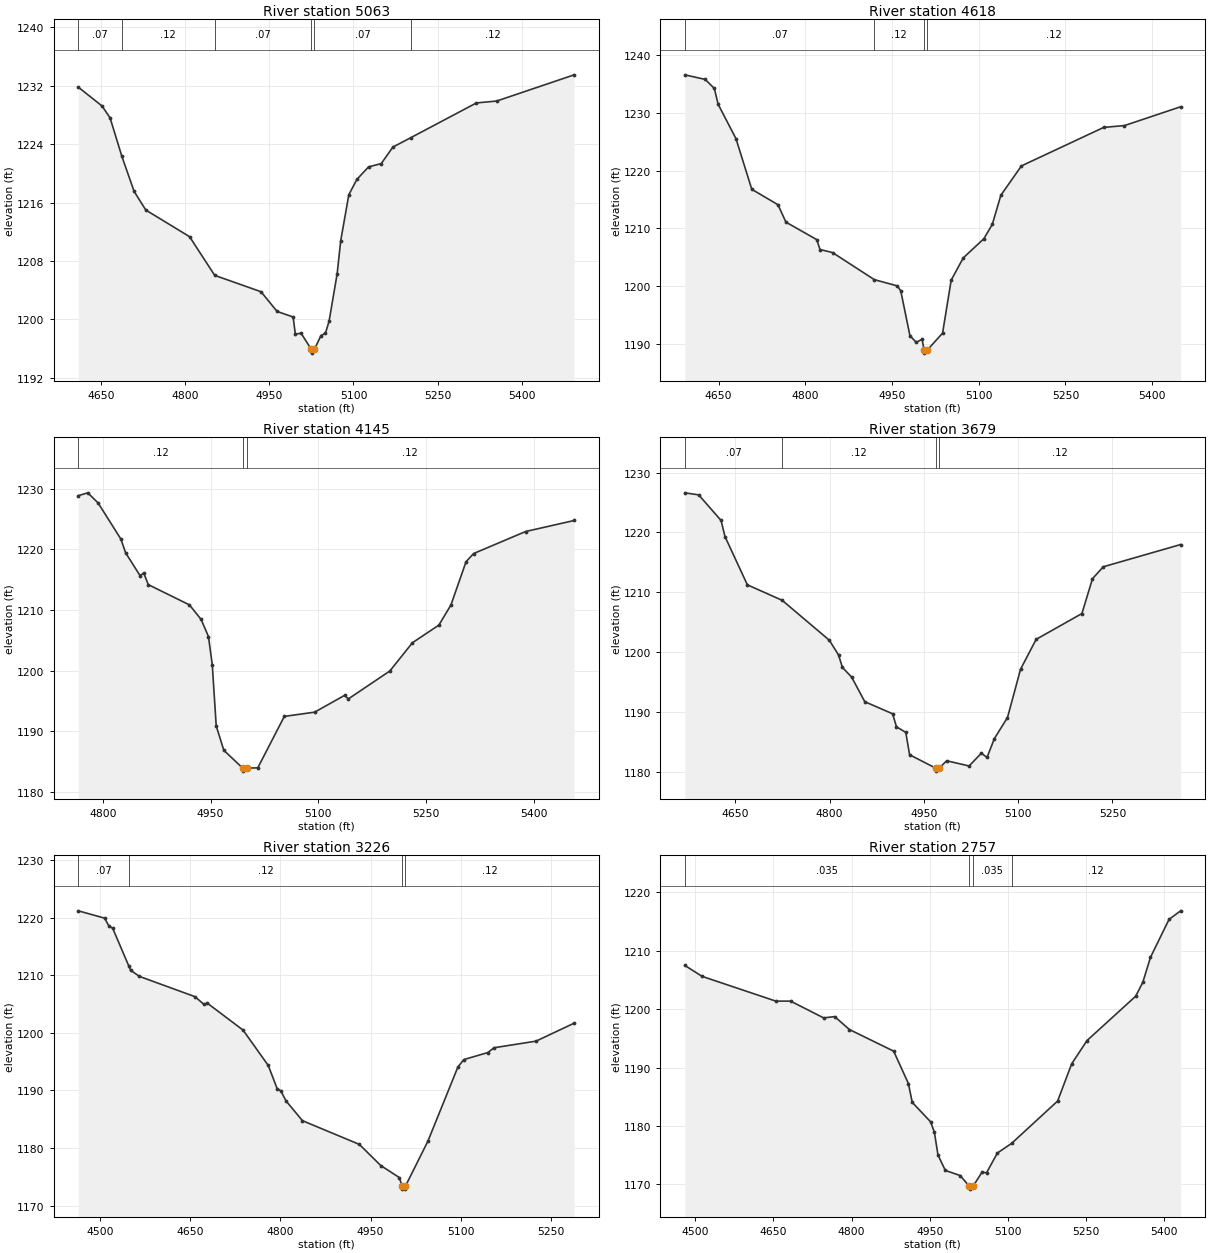
Type RM Length L Ch R = 1,5063,445,445,445
BEGIN DESCRIPTION:
Stream0175_DS 9.0
END DESCRIPTION:
XS GIS Cut Line= 3
      2096425.03     13859774.96      2096675.00     13859475.00
      2096980.51     13859086.37
#Sta/Elev= 30
  4609.0 1231.80  4651.3 1229.22  4665.6 1227.60  4686.7 1222.32  4708.5 1217.53
  4729.4 1214.97  4807.5 1211.32  4852.4 1206.02  4935.0 1203.78  4963.7 1201.08
  4992.3 1200.32  4996.2 1198.01  5006.7 1198.07  5024.9 1195.87  5025.3 1195.37
  5030.1 1195.87  5042.0 1197.77  5050.0 1198.11  5056.4 1199.72  5070.9 1206.25
  5077.2 1210.76  5091.7 1217.07  5106.1 1219.17  5126.9 1220.88  5149.5 1221.33
  5170.3 1223.59  5202.5 1224.89  5319.4 1229.64  5355.6 1229.90  5493.8 1233.49
#Mann=6,-1,0
  4609.0    0.07       0  4686.7    0.12       0  4852.4    0.07       0
  5024.9    0.05       0  5030.1    0.07       0  5202.5    0.12       0
Bank Sta=5024.9,5030.1
Exp/Cntr=0.3,0.1

Type RM Length L Ch R = 1,4618,473,473,473
BEGIN DESCRIPTION:
Stream0175_DS 8.0
END DESCRIPTION:
XS GIS Cut Line= 3
      2096625.00     13859975.00      2096975.00     13859775.00
      2097240.72     13859406.15
#Sta/Elev= 30
  4591.6 1236.52  4626.9 1235.73  4642.7 1234.17  4649.2 1231.45  4680.1 1225.51
  4707.5 1216.76  4752.8 1214.10  4766.5 1211.10  4819.8 1208.08  4825.5 1206.37
  4847.1 1205.85  4919.5 1201.17  4959.4 1200.09  4965.2 1199.23  4981.0 1191.52
  4991.8 1190.35  5002.1 1190.88  5005.6 1188.99  5006.0 1188.49  5010.8 1188.99
  5037.5 1191.94  5052.4 1201.08  5073.3 1204.93  5108.9 1208.23  5123.6 1210.72
  5138.3 1215.73  5173.9 1220.80  5316.3 1227.45  5352.1 1227.76  5449.3 1231.01
#Mann=4,-1,0
  4591.6    0.07       0  4919.5    0.12       0  5005.6    0.05       0
  5010.8    0.12       0
Bank Sta=5005.6,5010.8
Exp/Cntr=0.3,0.1

Type RM Length L Ch R = 1,4145,466,466,466
BEGIN DESCRIPTION:
Stream0175_DS 7.0
END DESCRIPTION:
XS GIS Cut Line= 3
      2097251.84     13860297.53      2097325.00     13860075.00
      2097470.29     13859642.18
#Sta/Elev= 30
  4765.8 1228.89  4779.0 1229.36  4793.4 1227.68  4825.2 1221.70  4831.6 1219.47
  4851.7 1215.70  4857.0 1216.10  4863.2 1214.20  4920.6 1210.85  4936.9 1208.44
  4947.1 1205.62  4952.4 1200.99  4957.9 1190.86  4968.5 1186.83  4994.8 1183.89
  4995.2 1183.39  5000.1 1183.89  5015.8 1183.93  5052.8 1192.43  5095.0 1193.13
  5136.7 1195.90  5142.0 1195.32  5199.8 1199.93  5231.3 1204.60  5268.1 1207.51
  5284.9 1210.83  5306.0 1217.99  5316.5 1219.33  5389.0 1222.97  5456.6 1224.79
#Mann=3,-1,0
  4765.8    0.12       0  4994.8    0.05       0  5000.1    0.12       0
Bank Sta=4994.8,5000.1
Exp/Cntr=0.3,0.1

Type RM Length L Ch R = 1,3679,453,453,453
BEGIN DESCRIPTION:
Stream0175_DS 6.0
END DESCRIPTION:
XS GIS Cut Line= 3
      2097425.01     13860374.99      2097775.00     13860125.00
      2097873.37     13859780.16
#Sta/Elev= 30
  4569.8 1226.62  4591.9 1226.28  4627.5 1222.00  4633.7 1219.32  4669.3 1211.25
  4724.7 1208.66  4799.6 1202.00  4814.3 1199.54  4820.5 1197.45  4835.2 1195.83
  4856.1 1191.72  4900.4 1189.70  4906.5 1187.52  4921.3 1186.60  4927.4 1182.85
  4969.0 1180.62  4969.4 1180.12  4974.3 1180.62  4986.4 1181.85  5022.0 1180.98
  5041.5 1183.11  5050.6 1182.41  5062.3 1185.57  5083.1 1189.07  5103.9 1197.15
  5128.7 1202.14  5201.5 1206.45  5218.3 1212.27  5235.4 1214.26  5358.5 1217.98
#Mann=4,-1,0
  4569.8    0.07       0  4724.7    0.12       0  4969.0    0.05       0
  4974.3    0.12       0
Bank Sta=4969,4974.3
Exp/Cntr=0.3,0.1

Type RM Length L Ch R = 1,3226,469,469,469
BEGIN DESCRIPTION:
Stream0175_DS 5.0
END DESCRIPTION:
XS GIS Cut Line= 3
      2097869.89     13860710.73      2098175.00     13860275.00
      2098185.86     13859981.53
#Sta/Elev= 30
  4463.4 1221.24  4507.0 1219.97  4514.5 1218.58  4520.6 1218.21  4547.5 1211.63
  4550.3 1210.92  4565.1 1209.84  4657.5 1206.32  4672.3 1205.00  4678.4 1205.17
  4737.7 1200.50  4779.6 1194.36  4794.4 1190.34  4800.5 1189.95  4809.2 1188.19
  4836.6 1184.75  4931.3 1180.63  4967.0 1176.95  4997.8 1174.87  5002.6 1173.35
  5003.1 1172.85  5007.6 1172.85  5008.0 1173.35  5045.4 1181.17  5095.4 1194.08
  5105.4 1195.38  5145.4 1196.60  5155.4 1197.43  5225.5 1198.58  5289.0 1201.71
#Mann=4,-1,0
  4463.4    0.07       0  4547.5    0.12       0  5002.6    0.05       0
  5008.0    0.12       0
Bank Sta=5002.6,5008
Exp/Cntr=0.3,0.1

Type RM Length L Ch R = 1,2757,473,473,473
BEGIN DESCRIPTION:
Stream0175_DS 4.0
END DESCRIPTION:
XS GIS Cut Line= 3
      2098147.68     13860884.34      2098525.00     13860525.00
      2098875.02     13860274.98
#Sta/Elev= 30
  4479.9 1207.48  4513.0 1205.61  4654.5 1201.37  4682.8 1201.37  4746.3 1198.50
  4767.4 1198.72  4795.7 1196.51  4880.6 1192.81  4908.9 1187.26  4916.2 1184.05
  4951.4 1180.72  4958.7 1178.95  4965.6 1175.04  4979.7 1172.40  5008.3 1171.52
  5025.6 1169.70  5026.1 1169.20  5032.9 1169.70  5050.1 1172.10  5058.7 1171.99
  5079.6 1175.38  5106.9 1177.03  5195.1 1184.27  5222.2 1190.66  5251.6 1194.63
  5345.0 1202.22  5358.6 1204.60  5373.3 1208.87  5408.9 1215.36  5431.1 1216.82
#Mann=4,-1,0
  4479.9   0.035       0  5025.6   0.035       0  5032.9   0.035       0
  5106.9    0.12       0
Bank Sta=5025.6,5032.9
Exp/Cntr=0.3,0.1

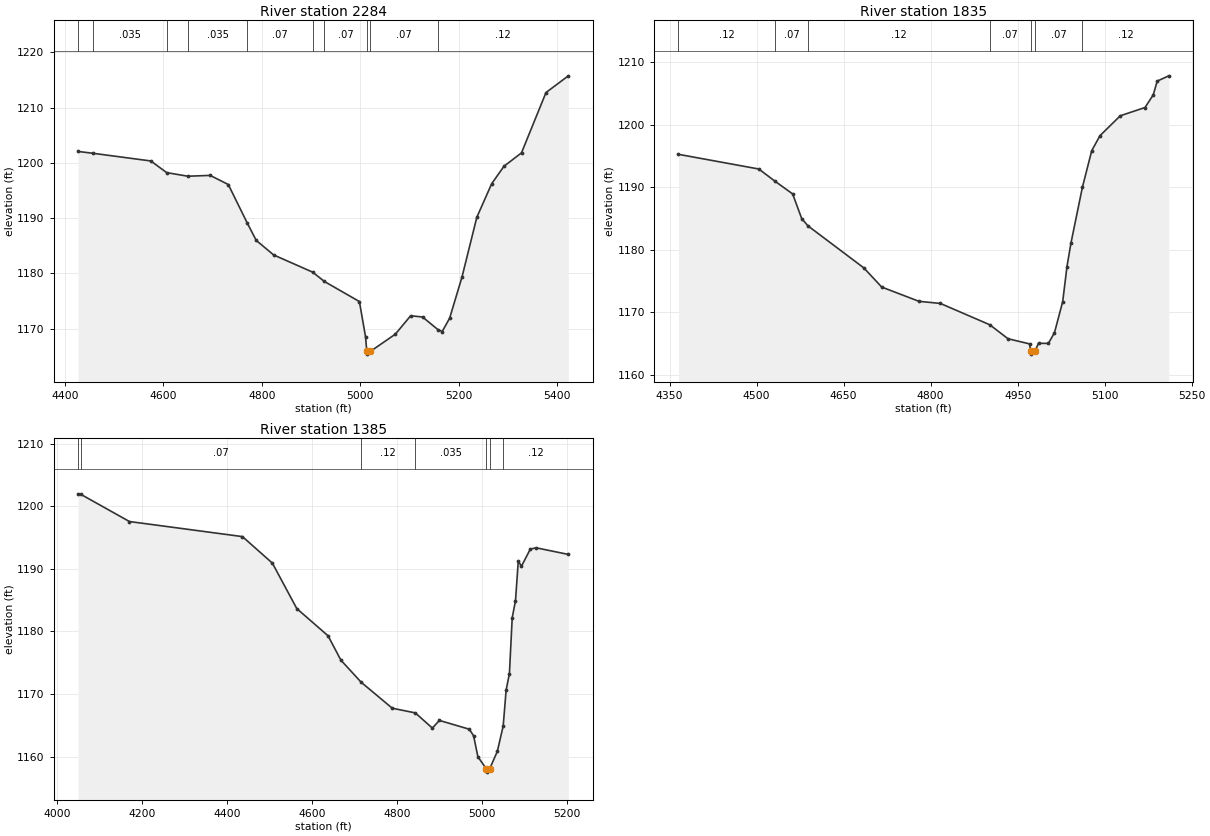
Type RM Length L Ch R = 1,2284,449,449,449
BEGIN DESCRIPTION:
Stream0175_DS 3.0
END DESCRIPTION:
XS GIS Cut Line= 3
      2098421.94     13861169.10      2098875.00     13860825.00
      2099024.99     13860425.02
#Sta/Elev= 30
  4426.8 1202.07  4458.0 1201.73  4574.6 1200.35  4606.9 1198.24  4650.0 1197.59
  4695.2 1197.74  4732.0 1196.09  4771.0 1189.04  4788.8 1185.98  4824.2 1183.35
  4903.4 1180.24  4927.3 1178.55  4998.4 1174.92  5010.9 1168.52  5013.4 1165.91
  5013.9 1165.41  5020.8 1165.91  5071.4 1169.02  5102.5 1172.35  5126.6 1172.13
  5158.0 1169.84  5166.6 1169.50  5181.7 1171.91  5206.7 1179.32  5236.9 1190.15
  5267.2 1196.25  5292.1 1199.39  5327.7 1201.82  5377.5 1212.73  5422.9 1215.75
#Mann=10,-1,0
  4426.8    0.07       0  4458.0   0.035       0  4606.9    0.07       0
  4650.0   0.035       0  4771.0    0.07       0  4903.4    0.12       0
  4927.3    0.07       0  5013.4    0.05       0  5020.8    0.07       0
  5158.0    0.12       0
Bank Sta=5013.4,5020.8
Exp/Cntr=0.3,0.1

Type RM Length L Ch R = 1,1835,450,450,450
BEGIN DESCRIPTION:
Stream0175_DS 2.0
END DESCRIPTION:
XS GIS Cut Line= 3
      2098730.97     13861301.04      2099275.00     13860975.00
      2099431.19     13860833.35
#Sta/Elev= 30
  4365.3 1195.26  4503.8 1192.91  4532.1 1190.93  4562.1 1188.93  4577.7 1184.99
  4588.3 1183.83  4684.8 1177.09  4715.7 1174.02  4779.8 1171.74  4816.8 1171.40
  4901.9 1167.99  4933.4 1165.75  4970.4 1164.93  4972.5 1163.79  4973.0 1163.29
  4980.0 1163.79  4985.9 1165.03  5002.9 1165.00  5013.4 1166.71  5027.6 1171.69
  5035.0 1177.31  5041.8 1181.04  5061.5 1189.96  5077.6 1195.83  5091.8 1198.24
  5126.9 1201.43  5169.5 1202.75  5183.7 1204.78  5190.5 1206.97  5210.4 1207.82
#Mann=7,-1,0
  4365.3    0.12       0  4532.1    0.07       0  4588.3    0.12       0
  4901.9    0.07       0  4972.5    0.05       0  4980.0    0.07       0
  5061.5    0.12       0
Bank Sta=4972.5,4980
Exp/Cntr=0.3,0.1

Type RM Length L Ch R = 1,1385,0,0,0
BEGIN DESCRIPTION:
Stream0175_DS 1.0
END DESCRIPTION:
XS GIS Cut Line= 3
      2098481.04     13861495.46      2099425.00     13861375.00
      2099557.40     13861221.14
#Sta/Elev= 30
  4048.7 1202.01  4054.7 1201.95  4169.7 1197.58  4435.8 1195.17  4506.3 1190.93
  4563.8 1183.66  4637.4 1179.31  4667.6 1175.42  4715.6 1171.87  4788.6 1167.73
  4842.9 1166.98  4883.1 1164.55  4899.5 1165.78  4970.1 1164.37  4980.2 1163.31
  4990.2 1159.98  5010.3 1158.01  5010.8 1157.51  5017.8 1158.01  5036.0 1160.82
  5049.8 1164.87  5056.8 1170.64  5064.5 1173.27  5071.1 1182.21  5078.8 1184.91
  5085.4 1191.28  5092.7 1190.42  5113.9 1193.19  5128.1 1193.37  5203.3 1192.32
#Mann=7,-1,0
  4048.7   0.035       0  4054.7    0.07       0  4715.6    0.12       0
  4842.9   0.035       0  5010.3   0.035       0  5017.8   0.035       0
  5049.8    0.12       0
Bank Sta=5010.3,5017.8
Exp/Cntr=0.3,0.1

Chan Stop Cuts=-1