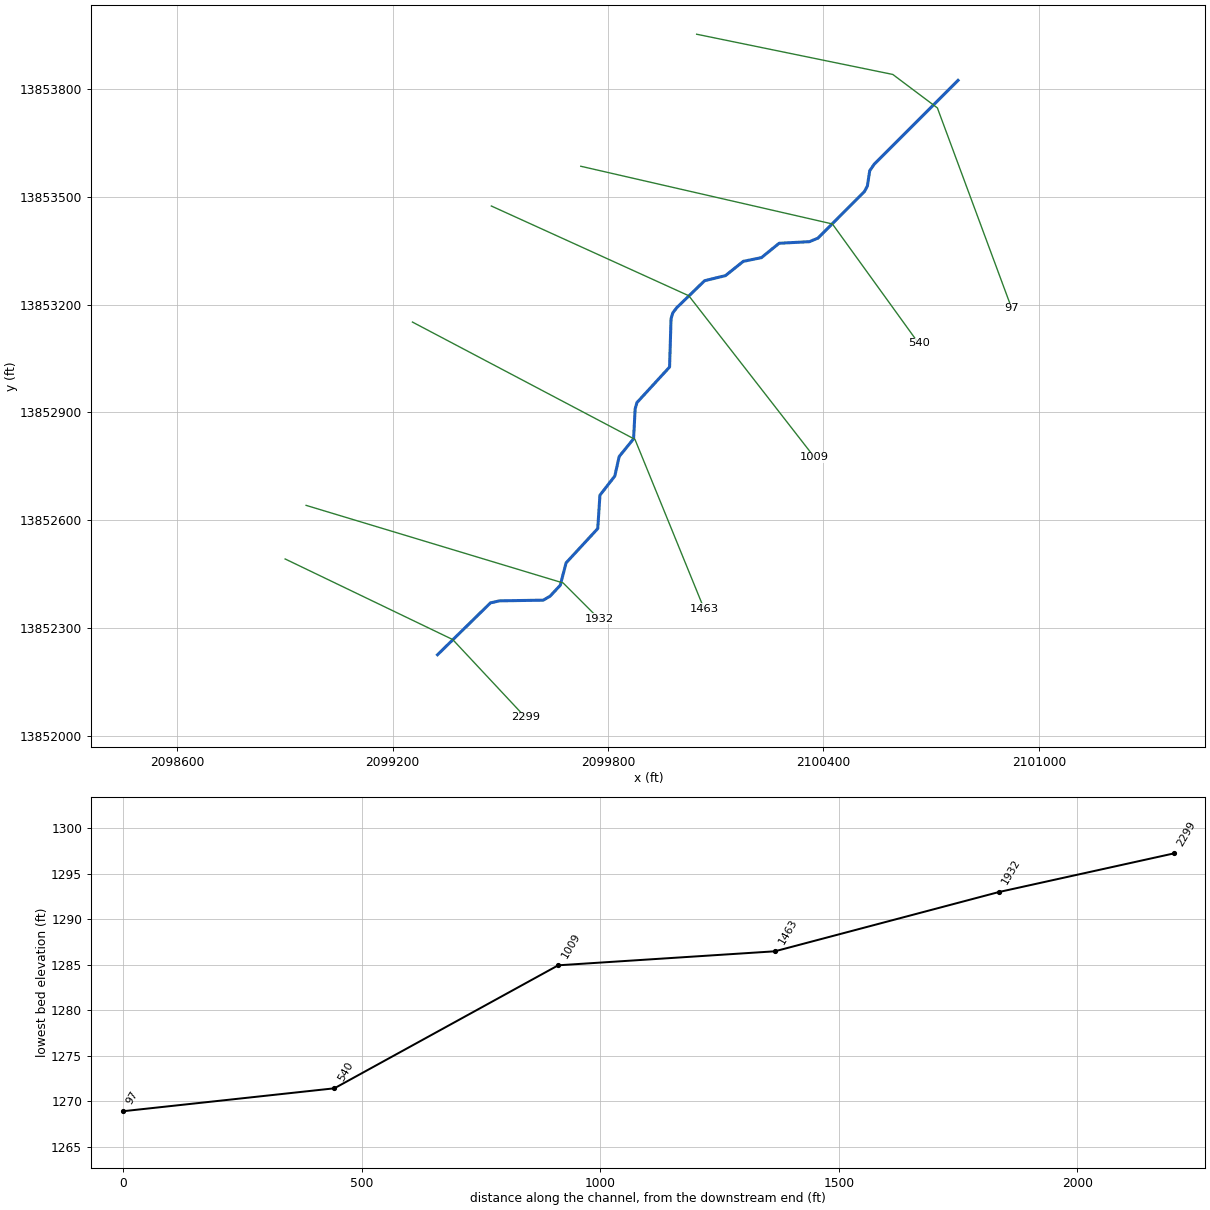
--- Stream0176_DS.prj (project) ---

Proj Title=Stream0176_DS Base Level Engineering
Current Plan=p01
Default Exp/Contr=0.3,0.1
English Units
Geom File=g01
Flow File=f01
Plan File=p01
BEGIN DESCRIPTION:
Stream0176_DS
END DESCRIPTION:

--- Stream0176_DS.p01 (plan) ---

Plan Title=Multiple Run
Short Identifier=Multiple
Geom File=g01
Flow File=f01
Subcritical Flow
K Sum by GR= 0
Std Step Tol= 0.01
Critical Tol= 0.01
Num of Std Step Trials= 20
Max Error Tol= 0.3
Flow Tol Ratio= 0.001
Split Flow NTrial= 30
Split Flow Tol= 0.02
Split Flow Ratio= 0.02
Log Output Level= 0
Friction Slope Method= 1
Unsteady Friction Slope Method= 2
Unsteady Bridges Friction Slope Method= 1
Parabolic Critical Depth
Global Vel Dist=  1 , 1 , 1
Global Log Level= 0
CheckData=True
Encroach Param= -1, 0, 0, 0
BEGIN DESCRIPTION:
Multiple Run
END DESCRIPTION:

--- Stream0176_DS.f01 (steady flow) ---

Flow Title=Multiple
Number of Profiles=7
Profile Names=10-year,25-year,50-year,1pct_min,100-year,1pct_plu,500-year
River Rch & RM= Stream0176_DS,Reach-1,2299
    1249    2132    2979    2018    4026    8034    7272
Boundary for River Rch & Prof#=Stream0176_DS,Reach-1,1
Up Type=0
Dn Type=3
Dn Slope=0.005
Boundary for River Rch & Prof#=Stream0176_DS,Reach-1,2
Up Type=0
Dn Type=3
Dn Slope=0.005
Boundary for River Rch & Prof#=Stream0176_DS,Reach-1,3
Up Type=0
Dn Type=3
Dn Slope=0.005
Boundary for River Rch & Prof#=Stream0176_DS,Reach-1,4
Up Type=0
Dn Type=3
Dn Slope=0.005
Boundary for River Rch & Prof#=Stream0176_DS,Reach-1,5
Up Type=0
Dn Type=3
Dn Slope=0.005
Boundary for River Rch & Prof#=Stream0176_DS,Reach-1,6
Up Type=0
Dn Type=3
Dn Slope=0.005
Boundary for River Rch & Prof#=Stream0176_DS,Reach-1,7
Up Type=0
Dn Type=3
Dn Slope=0.005

--- Stream0176_DS.g01 (geometry) ---

Geom Title=Existing Conditions

River Reach=Stream0176_DS,Reach-1
Reach XY= 30
      2099325.00     13852225.00      2099472.55     13852369.54
      2099497.66     13852375.17      2099619.74     13852377.10
      2099638.67     13852388.23      2099666.98     13852418.62
      2099683.19     13852481.02      2099771.38     13852576.50
      2099777.45     13852669.44      2099818.89     13852722.82
      2099831.11     13852777.18      2099871.17     13852826.59
      2099875.53     13852909.78      2099880.54     13852927.42
      2099971.44     13853026.47      2099975.55     13853161.14
      2099980.46     13853177.46      2099991.42     13853191.80
      2100068.93     13853266.87      2100127.18     13853281.10
      2100176.72     13853320.84      2100227.18     13853331.12
      2100276.59     13853371.17      2100361.09     13853375.67
      2100384.79     13853385.52      2100514.22     13853515.32
      2100522.36     13853530.64      2100528.98     13853573.35
      2100541.65     13853591.67      2100775.00     13853825.00

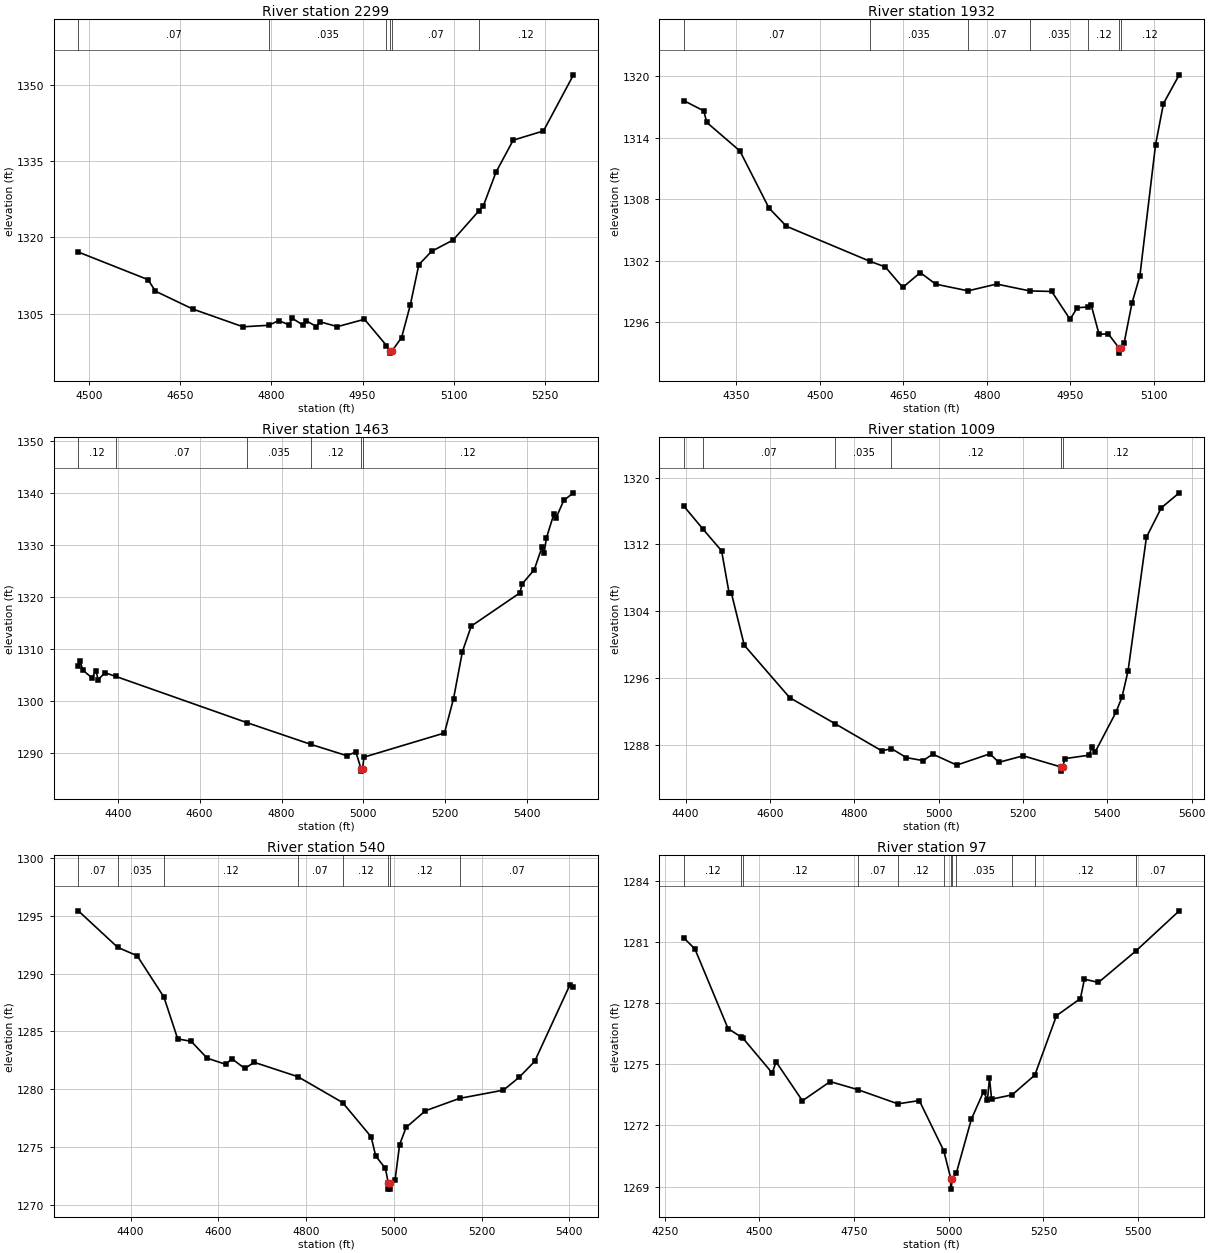
Type RM Length L Ch R = 1,2299,367,367,367
BEGIN DESCRIPTION:
Stream0176_DS 5.0
END DESCRIPTION:
XS GIS Cut Line= 3
      2098900.71     13852491.83      2099367.35     13852267.40
      2099570.32     13852050.30
#Sta/Elev= 30
  4482.2 1317.11  4597.1 1311.67  4609.0 1309.42  4670.5 1305.90  4753.3 1302.40
  4795.9 1302.70  4811.9 1303.62  4828.9 1302.80  4834.5 1304.06  4851.6 1302.77
  4857.1 1303.61  4874.2 1302.44  4879.8 1303.40  4908.6 1302.43  4953.2 1303.88
  4989.4 1298.72  4995.0 1297.72  4995.2 1297.22  4999.0 1297.72  5014.3 1300.29
  5028.5 1306.63  5042.7 1314.63  5063.7 1317.25  5099.1 1319.48  5141.8 1325.25
  5148.7 1326.15  5169.7 1332.84  5198.0 1339.12  5247.8 1340.94  5297.2 1351.98
#Mann=6,-1,0
  4482.2    0.07       0  4795.9   0.035       0  4989.4    0.07       0
  4995.0    0.05       0  4999.0    0.07       0  5141.8    0.12       0
Bank Sta=4995,4999
Exp/Cntr=0.3,0.1

Type RM Length L Ch R = 1,1932,469,469,469
BEGIN DESCRIPTION:
Stream0176_DS 4.0
END DESCRIPTION:
XS GIS Cut Line= 3
      2098958.97     13852641.17      2099675.00     13852425.00
      2099775.02     13852324.98
#Sta/Elev= 30
  4256.2 1317.60  4291.7 1316.61  4296.9 1315.49  4356.5 1312.70  4408.7 1307.13
  4440.1 1305.35  4590.2 1301.93  4617.7 1301.38  4649.0 1299.38  4680.5 1300.83
  4708.2 1299.70  4766.3 1299.05  4817.6 1299.71  4877.3 1299.04  4916.5 1298.99
  4949.5 1296.27  4962.4 1297.40  4981.2 1297.47  4987.7 1297.62  5001.5 1294.82
  5018.3 1294.84  5037.5 1293.47  5037.8 1292.97  5041.5 1293.47  5046.6 1293.96
  5060.7 1297.85  5074.9 1300.51  5103.1 1313.32  5117.3 1317.33  5145.6 1320.13
#Mann=7,-1,0
  4256.2    0.07       0  4590.2   0.035       0  4766.3    0.07       0
  4877.3   0.035       0  4981.2    0.12       0  5037.5    0.05       0
  5041.5    0.12       0
Bank Sta=5037.5,5041.5
Exp/Cntr=0.3,0.1

Type RM Length L Ch R = 1,1463,454,454,454
BEGIN DESCRIPTION:
Stream0176_DS 3.0
END DESCRIPTION:
XS GIS Cut Line= 3
      2099255.27     13853151.73      2099875.00     13852825.00
      2100067.25     13852353.79
#Sta/Elev= 30
  4303.6 1306.68  4308.1 1307.56  4314.6 1305.87  4337.2 1304.38  4346.5 1305.79
  4352.2 1304.03  4368.6 1305.38  4395.5 1304.66  4716.6 1295.75  4872.2 1291.59
  4959.0 1289.44  4981.6 1290.12  4994.0 1286.96  4994.2 1286.46  4998.0 1286.96
  5001.4 1289.15  5198.0 1293.79  5220.2 1300.42  5241.8 1309.44  5263.4 1314.34
  5382.2 1320.72  5387.8 1322.46  5417.2 1325.17  5435.9 1329.45  5441.3 1328.34
  5447.0 1331.29  5465.3 1335.90  5470.7 1335.17  5489.4 1338.51  5513.1 1339.96
#Mann=6,-1,0
  4303.6    0.12       0  4395.5    0.07       0  4716.6   0.035       0
  4872.2    0.12       0  4994.0    0.05       0  4998.0    0.12       0
Bank Sta=4994,4998
Exp/Cntr=0.3,0.1

Type RM Length L Ch R = 1,1009,469,469,469
BEGIN DESCRIPTION:
Stream0176_DS 2.0
END DESCRIPTION:
XS GIS Cut Line= 3
      2099474.96     13853475.02      2100025.00     13853225.00
      2100375.01     13852774.98
#Sta/Elev= 30
  4396.3 1316.55  4441.1 1313.84  4485.3 1311.24  4502.9 1306.26  4508.4 1306.22
  4539.1 1299.96  4646.8 1293.70  4755.4 1290.56  4865.4 1287.34  4888.2 1287.61
  4923.6 1286.53  4963.1 1286.18  4986.2 1286.95  5043.0 1285.64  5121.7 1286.99
  5142.6 1285.97  5200.5 1286.75  5289.9 1285.42  5290.1 1284.92  5293.9 1285.42
  5300.0 1286.42  5356.1 1286.82  5364.3 1287.78  5370.6 1287.15  5420.4 1291.94
  5434.8 1293.75  5449.3 1296.92  5492.8 1312.87  5528.0 1316.37  5570.6 1318.17
#Mann=6,-1,0
  4396.3   0.035       0  4441.1    0.07       0  4755.4   0.035       0
  4888.2    0.12       0  5289.9    0.05       0  5293.9    0.12       0
Bank Sta=5289.9,5293.9
Exp/Cntr=0.3,0.1

Type RM Length L Ch R = 1,540,443,443,443
BEGIN DESCRIPTION:
Stream0176_DS 1.0
END DESCRIPTION:
XS GIS Cut Line= 3
      2099724.05     13853585.74      2100425.00     13853425.00
      2100665.04     13853092.67
#Sta/Elev= 30
  4280.6 1295.41  4370.4 1292.26  4414.9 1291.53  4475.9 1287.96  4507.3 1284.36
  4538.1 1284.15  4574.3 1282.70  4617.2 1282.16  4630.4 1282.66  4660.1 1281.81
  4681.7 1282.34  4781.3 1281.10  4883.2 1278.87  4948.4 1275.91  4958.7 1274.26
  4980.9 1273.19  4987.5 1271.90  4987.7 1271.40  4991.2 1271.40  4991.5 1271.90
  5002.8 1272.17  5013.3 1275.25  5028.0 1276.72  5072.1 1278.16  5150.0 1279.23
  5250.0 1279.94  5285.6 1281.04  5321.2 1282.42  5400.9 1288.97  5409.7 1288.86
#Mann=8,-1,0
  4280.6    0.07       0  4370.4   0.035       0  4475.9    0.12       0
  4781.3    0.07       0  4883.2    0.12       0  4987.5    0.05       0
  4991.5    0.12       0  5150.0    0.07       0
Bank Sta=4987.5,4991.5
Exp/Cntr=0.3,0.1

Type RM Length L Ch R = 1,97,0,0,0
BEGIN DESCRIPTION:
Stream0176_DS 0.0
END DESCRIPTION:
XS GIS Cut Line= 4
      2100046.86     13853953.49      2100593.22     13853841.44
      2100717.43     13853748.19      2100924.30     13853190.15
#Sta/Elev= 30
  4300.7 1281.18  4329.4 1280.65  4416.9 1276.75  4451.9 1276.33  4455.3 1276.30
  4533.6 1274.57  4543.8 1275.12  4613.4 1273.21  4686.7 1274.15  4759.0 1273.76
  4865.6 1273.06  4922.2 1273.22  4986.8 1270.76  5005.6 1269.38  5005.9 1268.88
  5009.6 1269.38  5019.9 1269.66  5059.8 1272.31  5091.8 1273.65  5102.3 1273.26
  5107.6 1274.33  5113.1 1273.29  5167.4 1273.50  5227.4 1274.47  5284.6 1277.38
  5347.8 1278.22  5358.4 1279.17  5395.5 1279.01  5495.4 1280.57  5608.9 1282.52
#Mann=12,-1,0
  4300.7    0.12       0  4451.9    0.07       0  4455.3    0.12       0
  4759.0    0.07       0  4865.6    0.12       0  4986.8    0.07       0
  5005.6    0.05       0  5009.6    0.07       0  5019.9   0.035       0
  5167.4    0.07       0  5227.4    0.12       0  5495.4    0.07       0
Bank Sta=5005.6,5009.6
Exp/Cntr=0.3,0.1

Chan Stop Cuts=-1