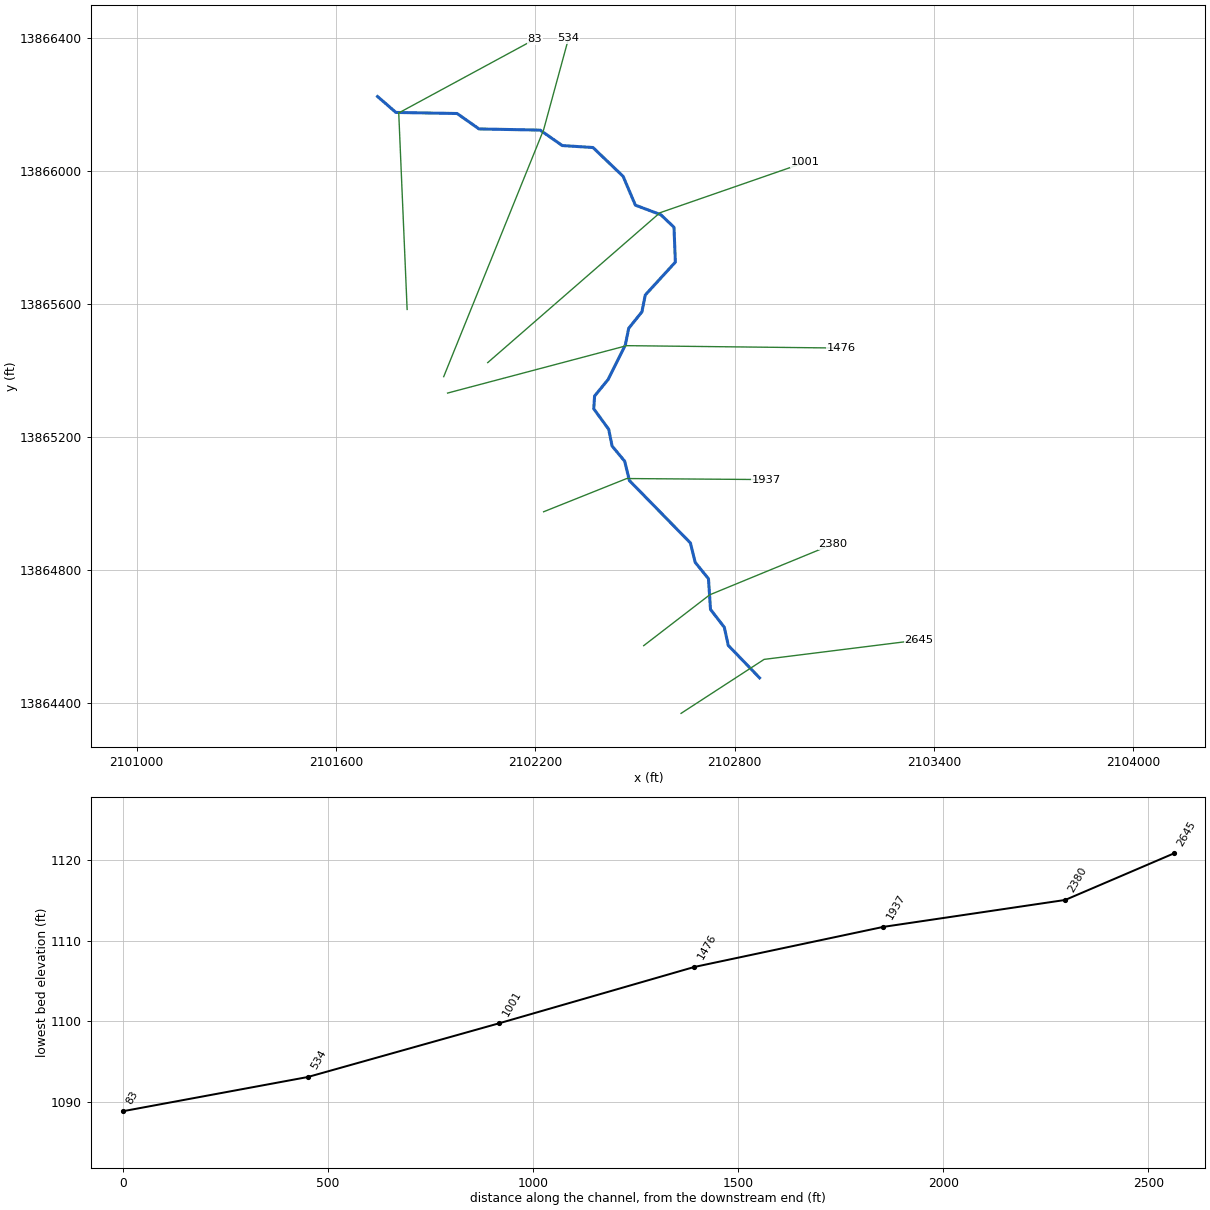
--- Stream0177_DS.prj (project) ---

Proj Title=Stream0177_DS Base Level Engineering
Current Plan=p01
Default Exp/Contr=0.3,0.1
English Units
Geom File=g01
Flow File=f01
Plan File=p01
BEGIN DESCRIPTION:
Stream0177_DS
END DESCRIPTION:

--- Stream0177_DS.p01 (plan) ---

Plan Title=Multiple Run
Short Identifier=Multiple
Geom File=g01
Flow File=f01
Subcritical Flow
K Sum by GR= 0
Std Step Tol= 0.01
Critical Tol= 0.01
Num of Std Step Trials= 20
Max Error Tol= 0.3
Flow Tol Ratio= 0.001
Split Flow NTrial= 30
Split Flow Tol= 0.02
Split Flow Ratio= 0.02
Log Output Level= 0
Friction Slope Method= 1
Unsteady Friction Slope Method= 2
Unsteady Bridges Friction Slope Method= 1
Parabolic Critical Depth
Global Vel Dist=  1 , 1 , 1
Global Log Level= 0
CheckData=True
Encroach Param= -1, 0, 0, 0
BEGIN DESCRIPTION:
Multiple Run
END DESCRIPTION:

--- Stream0177_DS.f01 (steady flow) ---

Flow Title=Multiple
Number of Profiles=7
Profile Names=10-year,25-year,50-year,1pct_min,100-year,1pct_plu,500-year
River Rch & RM= Stream0177_DS,Reach-1,2645
    1186    2010    2794    1882    3755    7491    6707
Boundary for River Rch & Prof#=Stream0177_DS,Reach-1,1
Up Type=0
Dn Type=3
Dn Slope=0.005
Boundary for River Rch & Prof#=Stream0177_DS,Reach-1,2
Up Type=0
Dn Type=3
Dn Slope=0.005
Boundary for River Rch & Prof#=Stream0177_DS,Reach-1,3
Up Type=0
Dn Type=3
Dn Slope=0.005
Boundary for River Rch & Prof#=Stream0177_DS,Reach-1,4
Up Type=0
Dn Type=3
Dn Slope=0.005
Boundary for River Rch & Prof#=Stream0177_DS,Reach-1,5
Up Type=0
Dn Type=3
Dn Slope=0.005
Boundary for River Rch & Prof#=Stream0177_DS,Reach-1,6
Up Type=0
Dn Type=3
Dn Slope=0.005
Boundary for River Rch & Prof#=Stream0177_DS,Reach-1,7
Up Type=0
Dn Type=3
Dn Slope=0.005

--- Stream0177_DS.g01 (geometry) ---

Geom Title=Existing Conditions

River Reach=Stream0177_DS,Reach-1
Reach XY= 30
      2102875.00     13864475.00      2102780.79     13864572.68
      2102768.87     13864627.17      2102727.33     13864680.97
      2102721.17     13864773.42      2102681.14     13864822.83
      2102666.86     13864881.06      2102483.14     13865068.94
      2102468.90     13865127.19      2102431.08     13865172.80
      2102420.78     13865223.28      2102375.90     13865284.84
      2102378.34     13865323.28      2102418.84     13865372.80
      2102470.84     13865476.72      2102481.08     13865527.20
      2102520.81     13865576.74      2102530.85     13865627.29
      2102621.53     13865726.50      2102617.36     13865831.45
      2102577.56     13865869.25      2102501.17     13865897.86
      2102464.22     13865984.69      2102373.52     13866071.39
      2102280.98     13866077.36      2102214.50     13866123.78
      2102030.53     13866127.38      2101964.49     13866173.78
      2101780.37     13866177.00      2101725.00     13866225.00

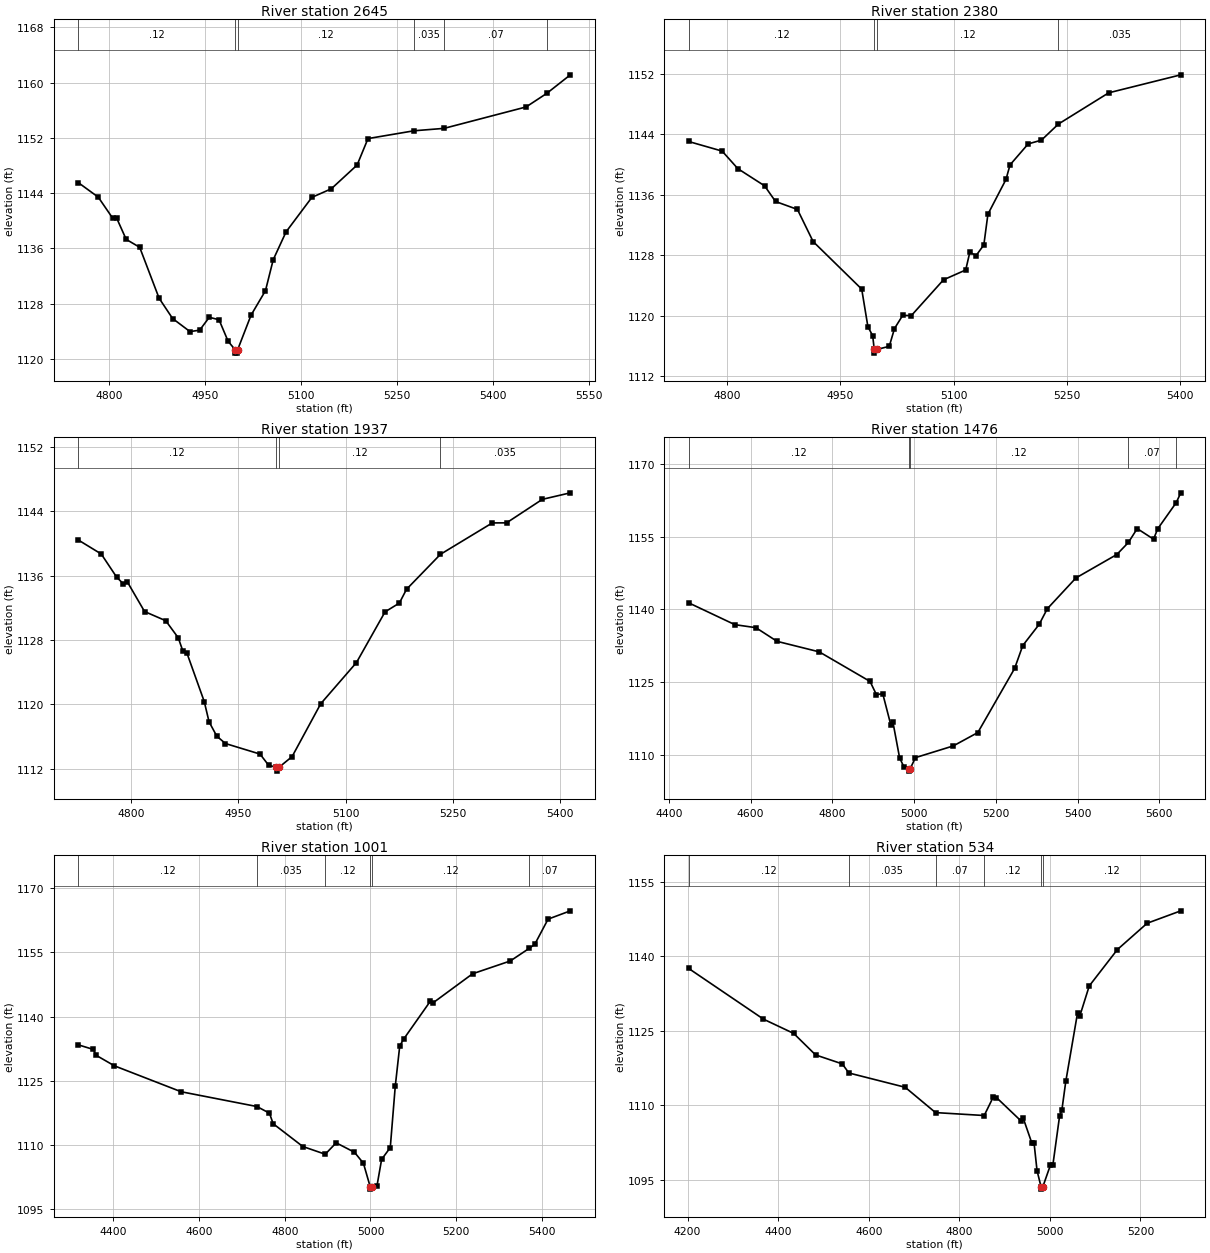
Type RM Length L Ch R = 1,2645,265,265,265
BEGIN DESCRIPTION:
Stream0177_DS 6.0
END DESCRIPTION:
XS GIS Cut Line= 3
      2102638.65     13864368.10      2102888.68     13864530.62
      2103355.44     13864588.96
#Sta/Elev= 30
  4752.0 1145.53  4783.4 1143.41  4805.9 1140.37  4811.9 1140.43  4827.0 1137.30
  4848.1 1136.15  4878.4 1128.78  4899.5 1125.84  4926.6 1123.95  4941.7 1124.15
  4956.8 1126.02  4972.0 1125.66  4986.2 1122.54  4997.1 1121.33  4997.3 1120.83
  5000.8 1120.83  5001.1 1121.33  5022.0 1126.33  5044.5 1129.87  5056.6 1134.35
  5076.7 1138.39  5117.0 1143.38  5147.3 1144.62  5187.6 1148.06  5204.6 1151.89
  5276.5 1153.02  5323.5 1153.37  5451.5 1156.47  5483.7 1158.43  5520.6 1161.12
#Mann=6,-1,0
  4752.0    0.12       0  4997.1    0.05       0  5001.1    0.12       0
  5276.5   0.035       0  5323.5    0.07       0  5483.7   0.035       0
Bank Sta=4997.1,5001.1
Exp/Cntr=0.3,0.1

Type RM Length L Ch R = 1,2380,443,443,443
BEGIN DESCRIPTION:
Stream0177_DS 5.0
END DESCRIPTION:
XS GIS Cut Line= 3
      2102526.15     13864571.87      2102725.00     13864725.00
      2103095.60     13864877.42
#Sta/Elev= 30
  4749.0 1143.02  4793.4 1141.75  4814.2 1139.43  4849.6 1137.16  4864.1 1135.09
  4893.1 1134.04  4913.9 1129.79  4978.2 1123.51  4986.4 1118.54  4992.7 1117.36
  4994.8 1115.55  4995.1 1115.05  4998.8 1115.55  5014.7 1115.95  5021.6 1118.30
  5032.4 1120.03  5044.0 1120.02  5086.5 1124.74  5115.9 1126.04  5121.3 1128.37
  5129.7 1127.95  5139.9 1129.35  5145.3 1133.41  5169.2 1138.00  5174.6 1139.93
  5198.6 1142.70  5216.2 1143.20  5238.7 1145.33  5305.2 1149.45  5400.7 1151.83
#Mann=4,-1,0
  4749.0    0.12       0  4994.8    0.05       0  4998.8    0.12       0
  5238.7   0.035       0
Bank Sta=4994.8,4998.8
Exp/Cntr=0.3,0.1

Type RM Length L Ch R = 1,1937,461,461,461
BEGIN DESCRIPTION:
Stream0177_DS 4.0
END DESCRIPTION:
XS GIS Cut Line= 3
      2102225.01     13864975.00      2102475.00     13865075.00
      2102894.24     13865071.86
#Sta/Elev= 30
  4726.0 1140.44  4758.3 1138.69  4779.8 1135.82  4789.3 1134.97  4794.7 1135.24
  4818.9 1131.54  4848.5 1130.40  4866.0 1128.28  4872.7 1126.58  4878.1 1126.39
  4902.4 1120.35  4909.1 1117.84  4919.9 1116.06  4932.0 1115.14  4980.4 1113.83
  4992.6 1112.42  5003.3 1112.21  5003.5 1111.71  5007.3 1112.21  5025.3 1113.52
  5065.3 1120.08  5115.3 1125.20  5155.3 1131.50  5175.3 1132.59  5185.3 1134.30
  5232.8 1138.65  5305.3 1142.55  5325.3 1142.56  5375.3 1145.48  5414.5 1146.29
#Mann=4,-1,0
  4726.0    0.12       0  5003.3    0.05       0  5007.3    0.12       0
  5232.8   0.035       0
Bank Sta=5003.3,5007.3
Exp/Cntr=0.3,0.1

Type RM Length L Ch R = 1,1476,475,475,475
BEGIN DESCRIPTION:
Stream0177_DS 3.0
END DESCRIPTION:
XS GIS Cut Line= 3
      2101935.82     13865332.26      2102475.00     13865475.00
      2103121.71     13865467.71
#Sta/Elev= 30
  4448.2 1141.37  4561.4 1136.87  4612.9 1136.25  4664.6 1133.44  4768.0 1131.27
  4892.2 1125.19  4908.0 1122.43  4923.2 1122.70  4943.0 1116.25  4948.2 1116.81
  4964.6 1109.44  4974.9 1107.65  4986.4 1107.23  4986.7 1106.73  4990.4 1107.23
  5003.4 1109.51  5096.0 1111.92  5156.0 1114.67  5246.0 1127.86  5266.0 1132.58
  5306.0 1136.92  5326.0 1140.14  5396.0 1146.48  5496.0 1151.30  5524.5 1153.79
  5546.0 1156.64  5586.0 1154.46  5596.0 1156.57  5641.3 1161.96  5652.7 1164.00
#Mann=5,-1,0
  4448.2    0.12       0  4986.4    0.05       0  4990.4    0.12       0
  5524.5    0.07       0  5641.3    0.12       0
Bank Sta=4986.4,4990.4
Exp/Cntr=0.3,0.1

Type RM Length L Ch R = 1,1001,467,467,467
BEGIN DESCRIPTION:
Stream0177_DS 2.0
END DESCRIPTION:
XS GIS Cut Line= 3
      2102056.67     13865423.90      2102575.00     13865875.00
      2103011.15     13866026.34
#Sta/Elev= 30
  4317.7 1133.41  4353.0 1132.33  4359.7 1130.96  4402.4 1128.50  4558.1 1122.46
  4735.0 1119.01  4764.2 1117.46  4772.8 1115.01  4842.0 1109.69  4894.4 1107.89
  4919.9 1110.55  4962.6 1108.35  4983.5 1105.79  4999.5 1100.25  4999.8 1099.75
  5003.5 1100.25  5015.1 1100.48  5026.0 1106.69  5046.2 1109.44  5057.8 1123.71
  5068.3 1133.15  5077.4 1134.73  5139.6 1143.56  5144.9 1143.11  5238.3 1149.97
  5326.4 1152.96  5370.2 1155.88  5383.4 1156.84  5414.5 1162.71  5466.5 1164.65
#Mann=6,-1,0
  4317.7    0.12       0  4735.0   0.035       0  4894.4    0.12       0
  4999.5    0.05       0  5003.5    0.12       0  5370.2    0.07       0
Bank Sta=4999.5,5003.5
Exp/Cntr=0.3,0.1

Type RM Length L Ch R = 1,534,451,451,451
BEGIN DESCRIPTION:
Stream0177_DS 1.0
END DESCRIPTION:
XS GIS Cut Line= 3
      2101924.19     13865381.66      2102225.00     13866125.00
      2102299.99     13866400.07
#Sta/Elev= 30
  4202.2 1137.54  4367.6 1127.31  4434.3 1124.44  4482.6 1120.11  4541.6 1118.30
  4556.1 1116.47  4680.5 1113.59  4747.5 1108.49  4855.0 1107.90  4874.6 1111.54
  4882.1 1111.52  4935.7 1106.86  4941.1 1107.39  4959.8 1102.46  4965.2 1102.28
  4971.7 1096.79  4980.5 1093.57  4980.7 1093.07  4984.6 1093.57  5001.4 1097.95
  5006.7 1097.95  5021.4 1107.74  5026.6 1109.03  5035.2 1114.78  5061.1 1128.55
  5066.3 1127.99  5087.0 1134.01  5149.2 1141.34  5214.9 1146.64  5289.2 1149.14
#Mann=6,-1,0
  4202.2    0.12       0  4556.1   0.035       0  4747.5    0.07       0
  4855.0    0.12       0  4980.5    0.05       0  4984.6    0.12       0
Bank Sta=4980.5,4984.6
Exp/Cntr=0.3,0.1

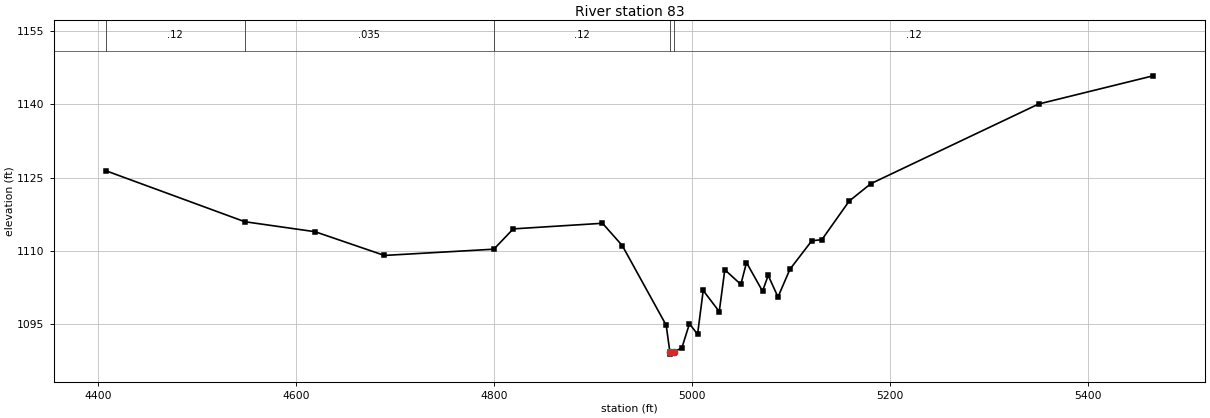
Type RM Length L Ch R = 1,83,0,0,0
BEGIN DESCRIPTION:
Stream0177_DS 0.0
END DESCRIPTION:
XS GIS Cut Line= 3
      2101814.11     13865584.04      2101788.84     13866175.50
      2102198.03     13866397.03
#Sta/Elev= 30
  4408.0 1126.39  4548.2 1115.95  4619.2 1113.90  4689.2 1109.04  4799.7 1110.32
  4819.3 1114.48  4909.4 1115.63  4929.4 1111.05  4973.7 1094.75  4977.4 1089.32
  4977.7 1088.82  4981.5 1089.32  4989.5 1090.07  4997.2 1095.04  5005.4 1092.89
  5011.1 1101.86  5027.3 1097.53  5032.9 1106.10  5049.1 1103.11  5054.8 1107.58
  5071.0 1101.71  5076.7 1104.95  5086.6 1100.52  5098.6 1106.19  5120.7 1112.04
  5130.9 1112.27  5158.5 1120.18  5180.4 1123.75  5349.7 1140.06  5465.3 1145.84
#Mann=5,-1,0
  4408.0    0.12       0  4548.2   0.035       0  4799.7    0.12       0
  4977.4    0.05       0  4981.5    0.12       0
Bank Sta=4977.4,4981.5
Exp/Cntr=0.3,0.1

Chan Stop Cuts=-1