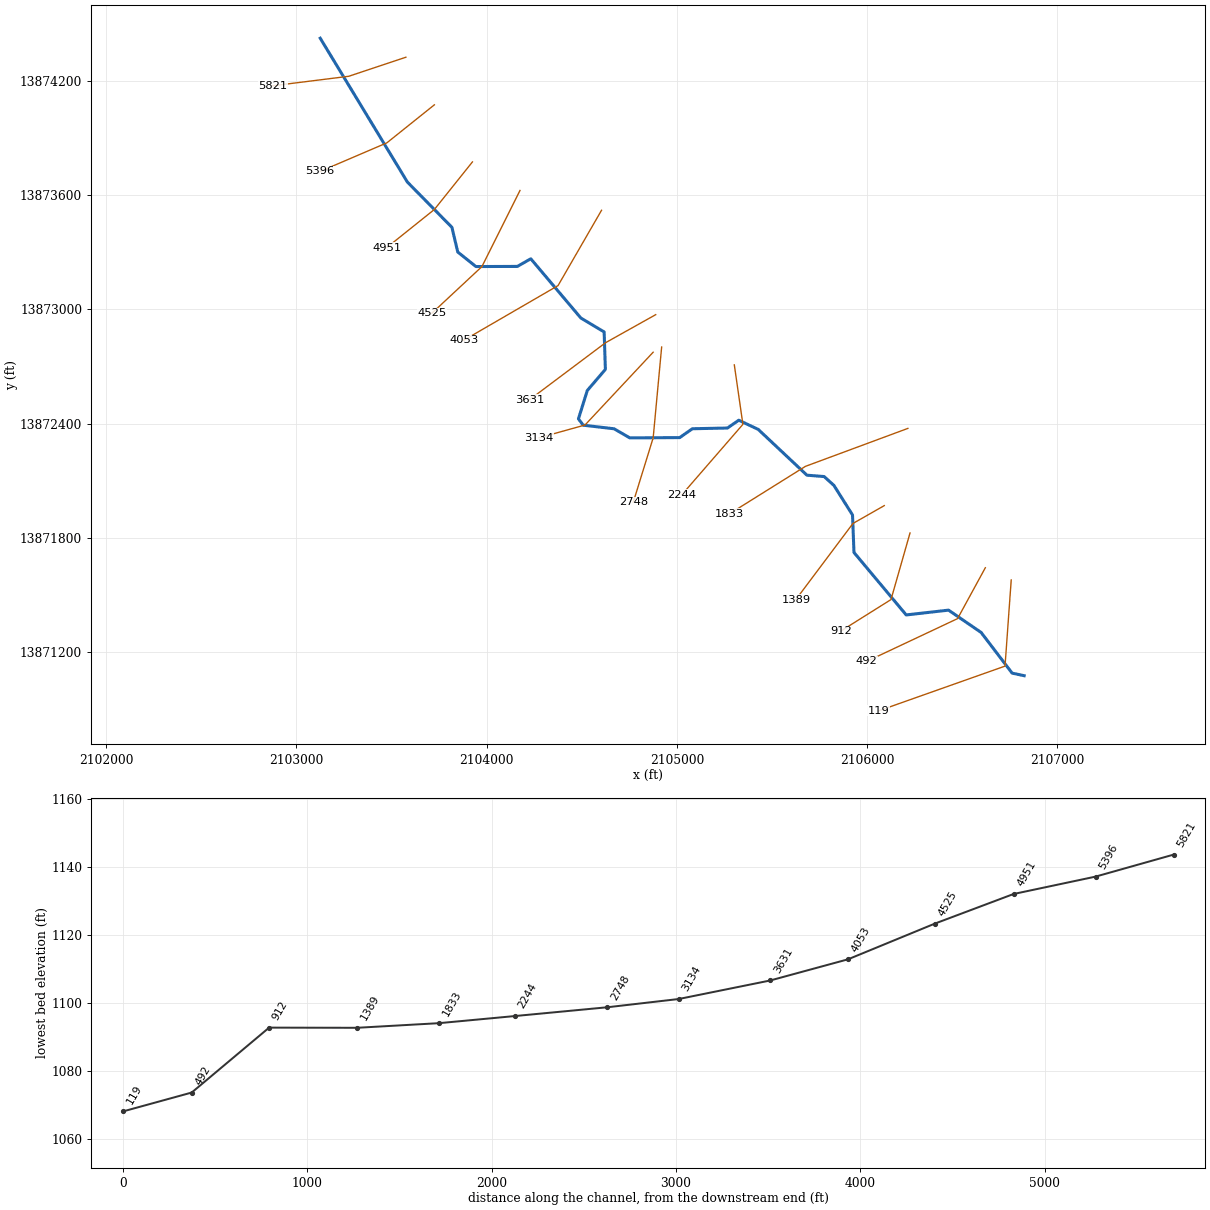
--- Stream0178_DS.prj (project) ---

Proj Title=Stream0178_DS Base Level Engineering
Current Plan=p01
Default Exp/Contr=0.3,0.1
English Units
Geom File=g01
Flow File=f01
Plan File=p01
Y Axis Title=Elevation
X Axis Title(PF)=Main Channel Distance
X Axis Title(XS)=Station
BEGIN DESCRIPTION:
Stream0178_DS
END DESCRIPTION:
DSS Export Rating Curves= 0
DSS Export Rating Curve Sorted= 0
DSS Export Volume Flow Curves= 0
DXF OffsetX= 0
DXF OffsetY= 0
DXF ScaleX= 1
DXF ScaleY= 10

--- Stream0178_DS.p01 (plan) ---

Plan Title=Multiple Run
Short Identifier=Multiple
Geom File=g01
Flow File=f01
Subcritical Flow
K Sum by GR= 0
Std Step Tol= 0.01
Critical Tol= 0.01
Num of Std Step Trials= 20
Max Error Tol= 0.3
Flow Tol Ratio= 0.001
Split Flow NTrial= 30
Split Flow Tol= 0.02
Split Flow Ratio= 0.02
Log Output Level= 0
Friction Slope Method= 1
Unsteady Friction Slope Method= 2
Unsteady Bridges Friction Slope Method= 1
Parabolic Critical Depth
Global Vel Dist=  1 , 1 , 1
Global Log Level= 0
CheckData=True
Encroach Param= -1, 0, 0, 0
BEGIN DESCRIPTION:
Multiple Run
END DESCRIPTION:

--- Stream0178_DS.f01 (steady flow) ---

Flow Title=Multiple
Program Version=4.10
Number of Profiles= 7
Profile Names=10-year,25-year,50-year,1pct_min,100-year,1pct_plu,500-year
River Rch & RM=Stream0178_DS,Reach-1         ,5821
    1388    2368    3306    2234    4458    8895    8021
River Rch & RM=Stream0178_DS,Reach-1         ,1833
    1566    2690    3774    2562    5111   10199    9278
Boundary for River Rch & Prof#=Stream0178_DS,Reach-1         , 1
Up Type= 0
Dn Type= 3
Dn Slope=0.005
Boundary for River Rch & Prof#=Stream0178_DS,Reach-1         , 2
Up Type= 0
Dn Type= 3
Dn Slope=0.005
Boundary for River Rch & Prof#=Stream0178_DS,Reach-1         , 3
Up Type= 0
Dn Type= 3
Dn Slope=0.005
Boundary for River Rch & Prof#=Stream0178_DS,Reach-1         , 4
Up Type= 0
Dn Type= 3
Dn Slope=0.005
Boundary for River Rch & Prof#=Stream0178_DS,Reach-1         , 5
Up Type= 0
Dn Type= 3
Dn Slope=0.005
Boundary for River Rch & Prof#=Stream0178_DS,Reach-1         , 6
Up Type= 0
Dn Type= 3
Dn Slope=0.005
Boundary for River Rch & Prof#=Stream0178_DS,Reach-1         , 7
Up Type= 0
Dn Type= 3
Dn Slope=0.005
DSS Import GetInterval= 0
DSS Import GetPeak= 0
DSS Import FillOption= 0

--- Stream0178_DS.g01 (geometry) ---

Geom Title=Existing Conditions

River Reach=Stream0178_DS,Reach-1
Reach XY= 30
      2103125.00     13874425.00      2103583.16     13873668.95
      2103817.14     13873431.17      2103847.85     13873301.42
      2103943.21     13873225.09      2104161.14     13873225.83
      2104231.74     13873265.87      2104494.84     13872954.62
      2104617.31     13872881.48      2104623.79     13872684.59
      2104528.62     13872573.50      2104482.21     13872424.65
      2104507.34     13872391.42      2104669.46     13872372.61
      2104752.16     13872324.72      2105014.50     13872326.22
      2105080.94     13872372.74      2105265.41     13872376.55
      2105325.01     13872417.47      2105427.29     13872369.19
      2105683.16     13872128.62      2105773.50     13872121.58
      2105825.00     13872075.00      2105922.83     13871919.56
      2105930.47     13871722.55      2106204.97     13871394.29
      2106427.44     13871419.53      2106598.84     13871302.14
      2106761.72     13871088.47      2106825.00     13871075.00

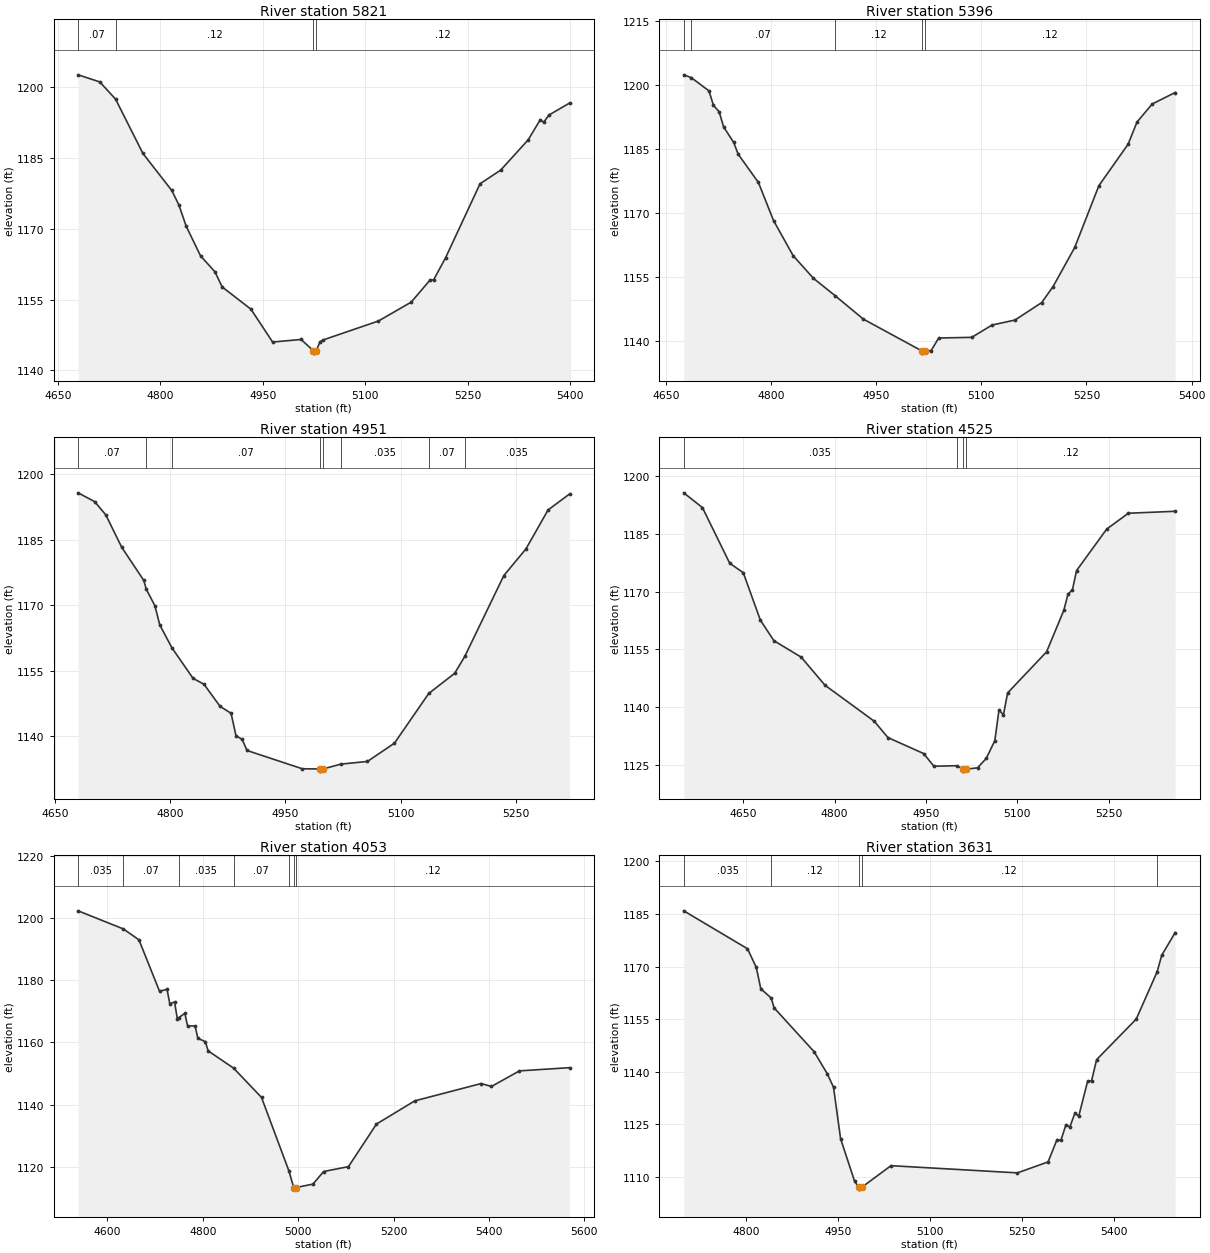
Type RM Length L Ch R = 1,5821,425,425,425
BEGIN DESCRIPTION:
Stream0178_DS 13.0
END DESCRIPTION:
XS GIS Cut Line= 3
      2103575.04     13874325.01      2103275.00     13874225.00
      2102874.99     13874175.00
#Sta/Elev= 30
  4679.6 1202.55  4711.3 1201.05  4734.4 1197.41  4774.5 1185.91  4816.7 1178.08
  4827.2 1174.99  4837.8 1170.52  4858.8 1164.25  4879.9 1160.87  4890.5 1157.66
  4932.6 1152.96  4964.3 1146.01  5006.0 1146.55  5024.1 1144.16  5024.4 1143.66
  5028.1 1144.16  5033.7 1146.05  5038.7 1146.47  5119.3 1150.46  5167.2 1154.45
  5194.9 1159.14  5200.0 1159.15  5217.6 1163.86  5268.0 1179.50  5298.2 1182.39
  5338.5 1188.80  5356.2 1193.07  5361.2 1192.52  5368.8 1194.04  5399.0 1196.57
#Mann=4,-1,0
  4679.6    0.07       0  4734.4    0.12       0  5024.1    0.05       0
  5028.1    0.12       0
Bank Sta=5024.1,5028.1
Exp/Cntr=0.3,0.1

Type RM Length L Ch R = 1,5396,445,445,445
BEGIN DESCRIPTION:
Stream0178_DS 12.0
END DESCRIPTION:
XS GIS Cut Line= 3
      2103725.02     13874075.02      2103475.00     13873875.00
      2103124.97     13873724.99
#Sta/Elev= 30
  4675.5 1202.29  4686.1 1201.65  4711.5 1198.54  4717.9 1195.14  4726.0 1193.66
  4732.4 1190.10  4746.8 1186.46  4753.2 1183.70  4782.0 1177.11  4803.6 1168.19
  4831.6 1159.96  4860.4 1154.69  4891.6 1150.58  4931.7 1145.12  5015.4 1137.66
  5015.6 1137.16  5019.5 1137.66  5028.3 1137.74  5039.2 1140.70  5086.3 1140.85
  5115.4 1143.74  5148.0 1144.90  5186.1 1148.99  5202.4 1152.75  5233.2 1161.88
  5267.7 1176.35  5309.4 1186.06  5322.1 1191.25  5343.8 1195.47  5376.5 1198.15
#Mann=5,-1,0
  4675.5   0.035       0  4686.1    0.07       0  4891.6    0.12       0
  5015.4    0.05       0  5019.5    0.12       0
Bank Sta=5015.4,5019.5
Exp/Cntr=0.3,0.1

Type RM Length L Ch R = 1,4951,426,426,426
BEGIN DESCRIPTION:
Stream0178_DS 11.0
END DESCRIPTION:
XS GIS Cut Line= 3
      2103924.99     13873774.98      2103725.00     13873525.00
      2103474.99     13873325.00
#Sta/Elev= 30
  4679.9 1195.80  4701.5 1193.78  4715.9 1190.77  4736.7 1183.33  4765.5 1175.72
  4768.7 1173.72  4779.9 1169.95  4786.3 1165.55  4802.0 1160.33  4829.6 1153.31
  4844.0 1151.93  4864.8 1146.89  4879.2 1145.29  4885.6 1140.16  4893.6 1139.31
  4900.0 1136.77  4972.0 1132.58  4994.8 1132.54  4995.0 1132.04  4998.9 1132.54
  5022.5 1133.65  5056.9 1134.26  5092.1 1138.45  5136.8 1149.84  5170.5 1154.44
  5183.7 1158.32  5234.6 1176.85  5263.4 1182.95  5292.2 1191.87  5320.2 1195.54
#Mann=8,-1,0
  4679.9    0.07       0  4768.7   0.035       0  4802.0    0.07       0
  4994.8    0.05       0  4998.9    0.07       0  5022.5   0.035       0
  5136.8    0.07       0  5183.7   0.035       0
Bank Sta=4994.8,4998.9
Exp/Cntr=0.3,0.1

Type RM Length L Ch R = 1,4525,472,472,472
BEGIN DESCRIPTION:
Stream0178_DS 10.0
END DESCRIPTION:
XS GIS Cut Line= 3
      2104175.00     13873625.00      2103975.00     13873225.00
      2103711.65     13872979.56
#Sta/Elev= 30
  4552.2 1195.74  4582.9 1191.90  4627.7 1177.43  4650.0 1174.96  4678.0 1162.65
  4700.3 1157.28  4745.1 1153.00  4784.2 1145.70  4865.2 1136.32  4887.6 1132.08
  4946.3 1127.92  4963.1 1124.62  5000.9 1124.76  5011.2 1123.85  5011.5 1123.35
  5015.4 1123.85  5034.8 1124.21  5049.0 1126.64  5063.2 1131.28  5070.0 1139.26
  5077.3 1137.98  5084.2 1143.69  5148.2 1154.38  5176.5 1165.17  5183.3 1169.33
  5190.7 1170.56  5197.5 1175.53  5246.9 1186.30  5282.5 1190.43  5359.4 1190.94
#Mann=4,-1,0
  4552.2   0.035       0  5000.9    0.12       0  5011.2   0.035       0
  5015.4    0.12       0
Bank Sta=5011.2,5015.4
Exp/Cntr=0.3,0.1

Type RM Length L Ch R = 1,4053,422,422,422
BEGIN DESCRIPTION:
Stream0178_DS 9.0
END DESCRIPTION:
XS GIS Cut Line= 3
      2104603.59     13873520.86      2104375.00     13873125.00
      2103878.95     13872837.41
#Sta/Elev= 30
  4538.5 1202.23  4633.5 1196.41  4666.1 1192.90  4709.2 1176.40  4725.0 1177.00
  4730.7 1172.41  4740.7 1172.94  4746.5 1167.62  4749.1 1167.87  4762.3 1169.29
  4768.0 1165.27  4783.8 1165.23  4789.6 1161.29  4805.4 1160.18  4811.1 1157.25
  4864.8 1151.66  4923.1 1142.27  4980.4 1118.73  4990.6 1113.32  4990.9 1112.82
  4994.8 1113.32  5030.8 1114.42  5053.4 1118.48  5105.4 1120.05  5164.2 1133.73
  5244.5 1141.18  5383.6 1146.74  5405.2 1145.80  5464.0 1150.81  5569.0 1151.84
#Mann=7,-1,0
  4538.5   0.035       0  4633.5    0.07       0  4749.1   0.035       0
  4864.8    0.07       0  4980.4    0.12       0  4990.6    0.05       0
  4994.8    0.12       0
Bank Sta=4990.6,4994.8
Exp/Cntr=0.3,0.1

Type RM Length L Ch R = 1,3631,497,497,497
BEGIN DESCRIPTION:
Stream0178_DS 8.0
END DESCRIPTION:
XS GIS Cut Line= 3
      2104888.26     13872972.19      2104625.00     13872825.00
      2104225.01     13872525.01
#Sta/Elev= 30
  4698.9 1185.86  4802.9 1175.06  4817.2 1169.76  4824.6 1163.66  4841.6 1161.02
  4846.3 1158.23  4911.4 1145.77  4933.1 1139.43  4943.2 1135.61  4954.8 1120.92
  4977.6 1108.83  4984.5 1107.09  4984.8 1106.59  4989.1 1107.09  5037.0 1113.27
  5243.2 1111.22  5293.2 1114.34  5307.8 1120.71  5314.1 1120.48  5322.4 1124.96
  5328.6 1124.25  5337.0 1128.24  5343.2 1127.36  5357.8 1137.38  5364.1 1137.40
  5372.4 1143.48  5437.0 1155.02  5471.0 1168.45  5478.6 1173.20  5500.5 1179.67
#Mann=5,-1,0
  4698.9   0.035       0  4841.6    0.12       0  4984.5    0.05       0
  4989.1    0.12       0  5471.0    0.07       0
Bank Sta=4984.5,4989.1
Exp/Cntr=0.3,0.1

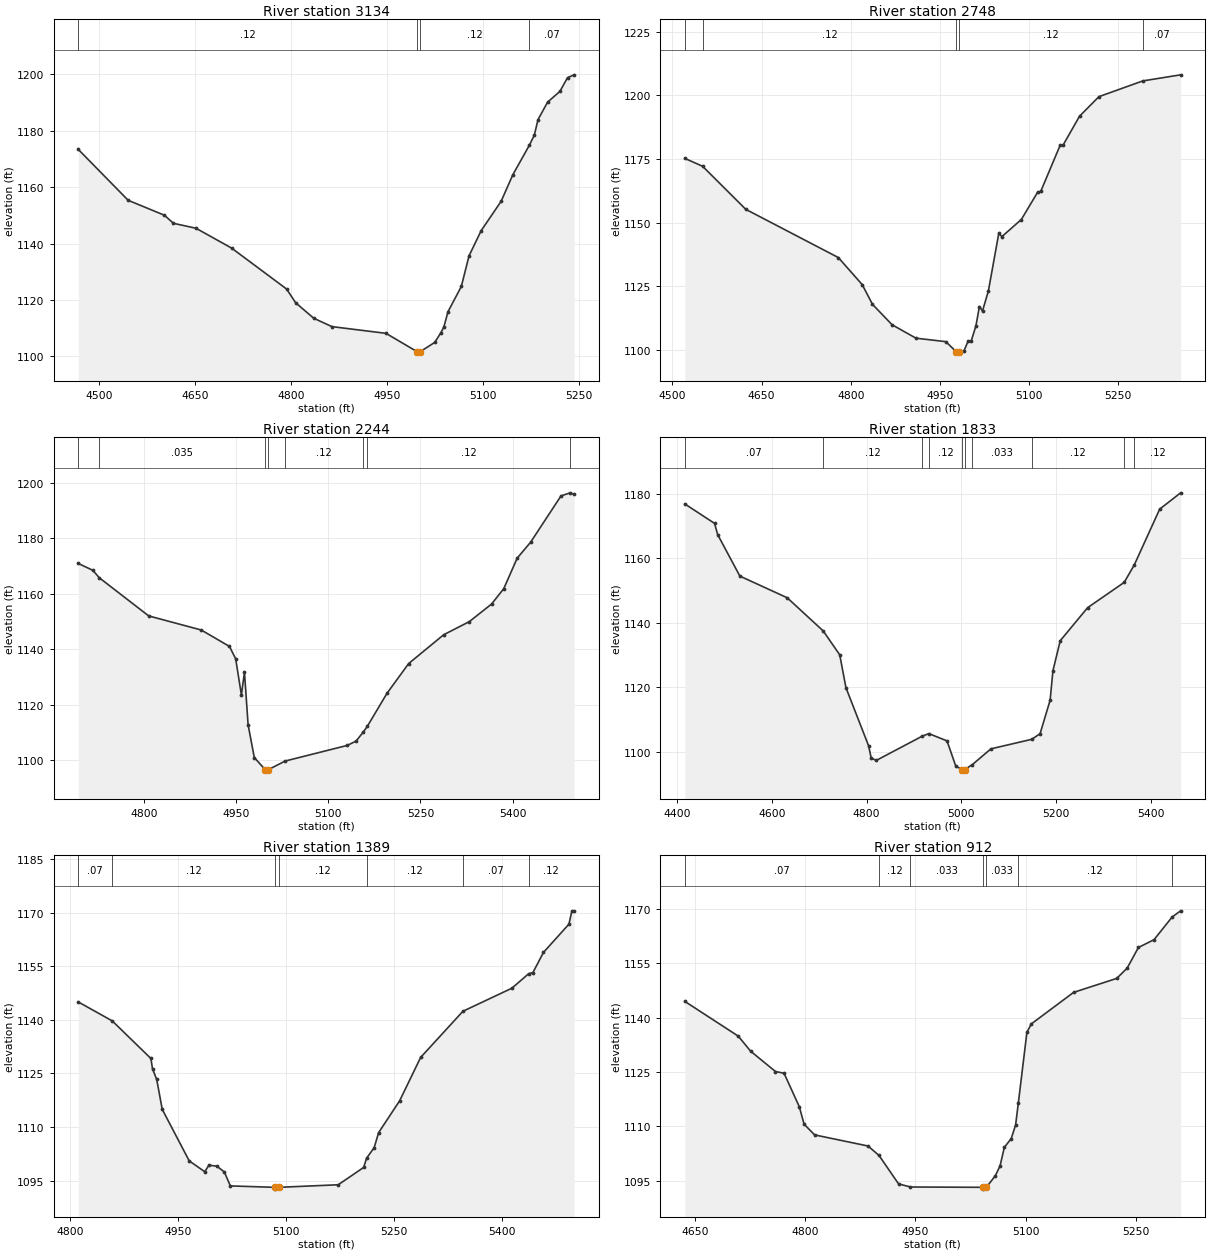
Type RM Length L Ch R = 1,3134,386,386,386
BEGIN DESCRIPTION:
Stream0178_DS 7.0
END DESCRIPTION:
XS GIS Cut Line= 3
      2104874.99     13872774.99      2104516.76     13872392.34
      2104275.03     13872325.01
#Sta/Elev= 30
  4467.6 1173.36  4545.5 1155.33  4602.2 1150.03  4616.3 1147.17  4651.5 1145.42
  4707.3 1138.37  4793.2 1123.86  4807.3 1119.00  4835.6 1113.50  4864.0 1110.53
  4948.5 1108.15  4997.3 1101.63  4997.6 1101.13  5002.0 1101.63  5024.7 1104.93
  5033.8 1108.14  5039.0 1110.39  5045.5 1115.83  5066.3 1124.76  5078.4 1135.66
  5097.4 1144.59  5128.5 1154.96  5146.8 1164.37  5172.8 1174.92  5180.4 1178.42
  5186.2 1183.95  5201.2 1190.15  5220.4 1193.95  5232.3 1198.82  5242.7 1199.83
#Mann=4,-1,0
  4467.6    0.12       0  4997.3    0.05       0  5002.0    0.12       0
  5172.8    0.07       0
Bank Sta=4997.3,5002
Exp/Cntr=0.3,0.1

Type RM Length L Ch R = 1,2748,504,504,504
BEGIN DESCRIPTION:
Stream0178_DS 6.0
END DESCRIPTION:
XS GIS Cut Line= 3
      2104919.54     13872802.09      2104875.00     13872325.00
      2104770.23     13871986.09
#Sta/Elev= 30
  4520.8 1175.18  4550.7 1172.09  4623.4 1155.17  4779.0 1136.24  4819.2 1125.61
  4836.4 1117.89  4869.4 1109.85  4909.6 1104.58  4959.8 1103.22  4977.5 1099.21
  4977.9 1098.71  4982.2 1099.21  4989.9 1099.39  4997.5 1103.53  5002.6 1103.53
  5010.4 1109.40  5016.3 1117.00  5021.5 1115.26  5031.4 1123.15  5048.9 1145.78
  5054.1 1144.46  5086.8 1151.18  5114.2 1161.89  5119.4 1162.20  5152.0 1180.28
  5157.3 1180.51  5184.7 1191.74  5217.3 1199.42  5291.1 1205.60  5354.7 1207.99
#Mann=5,-1,0
  4520.8   0.035       0  4550.7    0.12       0  4977.5    0.05       0
  4982.2    0.12       0  5291.1    0.07       0
Bank Sta=4977.5,4982.2
Exp/Cntr=0.3,0.1

Type RM Length L Ch R = 1,2244,411,411,411
BEGIN DESCRIPTION:
Stream0178_DS 5.0
END DESCRIPTION:
XS GIS Cut Line= 3
      2105301.48     13872708.36      2105346.62     13872395.81
      2105024.97     13872024.96
#Sta/Elev= 30
  4693.4 1170.96  4717.0 1168.50  4727.5 1165.81  4807.9 1152.06  4893.4 1146.98
  4939.3 1141.06  4949.4 1136.60  4958.7 1123.60  4963.7 1131.75  4969.6 1112.83
  4979.7 1101.00  4997.6 1096.61  4997.9 1096.11  5002.3 1096.61  5029.8 1099.74
  5131.1 1105.39  5145.3 1106.94  5156.9 1110.17  5163.5 1112.23  5195.6 1124.16
  5230.8 1134.88  5287.8 1145.27  5329.6 1150.01  5365.7 1156.34  5385.6 1161.90
  5407.4 1172.88  5429.3 1178.64  5478.7 1195.32  5493.7 1196.43  5500.1 1195.86
#Mann=8,-1,0
  4693.4    0.07       0  4727.5   0.035       0  4997.6   0.035       0
  5002.3   0.035       0  5029.8    0.12       0  5156.9   0.035       0
  5163.5    0.12       0  5493.7    0.07       0
Bank Sta=4997.6,5002.3
Exp/Cntr=0.3,0.1

Type RM Length L Ch R = 1,1833,444,444,444
BEGIN DESCRIPTION:
Stream0178_DS 4.0
END DESCRIPTION:
XS GIS Cut Line= 3
      2106213.92     13872374.60      2105675.00     13872175.00
      2105275.00     13871925.00
#Sta/Elev= 30
  4416.4 1176.91  4479.2 1170.87  4485.9 1167.35  4532.6 1154.52  4632.5 1147.80
  4708.5 1137.51  4743.4 1130.09  4756.5 1119.90  4804.2 1101.91  4809.8 1098.08
  4820.5 1097.34  4917.3 1104.85  4931.4 1105.66  4969.8 1103.40  4988.4 1095.51
  5002.3 1094.52  5002.6 1094.02  5007.0 1094.52  5023.0 1096.01  5062.4 1100.93
  5148.6 1103.89  5166.2 1105.63  5187.4 1116.03  5193.3 1125.14  5208.7 1134.47
  5266.5 1144.72  5343.8 1152.58  5365.1 1158.02  5418.6 1175.29  5462.8 1180.35
#Mann=10,-1,0
  4416.4    0.07       0  4708.5    0.12       0  4917.3    0.07       0
  4931.4    0.12       0  5002.3    0.05       0  5007.0    0.12       0
  5023.0   0.033       0  5148.6    0.12       0  5343.8    0.07       0
  5365.1    0.12       0
Bank Sta=5002.3,5007
Exp/Cntr=0.3,0.1

Type RM Length L Ch R = 1,1389,477,477,477
BEGIN DESCRIPTION:
Stream0178_DS 3.0
END DESCRIPTION:
XS GIS Cut Line= 3
      2106089.69     13871968.74      2105925.00     13871875.00
      2105625.00     13871475.00
#Sta/Elev= 30
  4811.0 1145.00  4858.2 1139.70  4911.9 1129.20  4914.2 1126.26  4920.0 1123.33
  4927.7 1114.96  4965.2 1100.56  4986.8 1097.53  4992.6 1099.36  5003.6 1099.08
  5014.0 1097.47  5022.4 1093.56  5084.4 1093.16  5084.8 1092.66  5089.5 1093.16
  5172.4 1093.88  5207.8 1098.73  5211.9 1101.33  5222.4 1104.26  5228.6 1108.47
  5257.8 1117.36  5287.0 1129.49  5345.8 1142.40  5414.0 1148.86  5437.1 1152.88
  5443.2 1153.24  5457.8 1158.86  5493.2 1166.75  5497.4 1170.49  5500.5 1170.49
#Mann=7,-1,0
  4811.0    0.07       0  4858.2    0.12       0  5084.4    0.05       0
  5089.5    0.12       0  5211.9    0.12       0  5345.8    0.07       0
  5437.1    0.12       0
Bank Sta=5084.4,5089.5
Exp/Cntr=0.3,0.1

Type RM Length L Ch R = 1,912,420,420,420
BEGIN DESCRIPTION:
Stream0178_DS 2.0
END DESCRIPTION:
XS GIS Cut Line= 3
      2106225.01     13871825.04      2106125.00     13871475.00
      2105861.28     13871309.49
#Sta/Elev= 30
  4635.9 1144.53  4708.7 1134.94  4725.6 1130.78  4759.4 1125.17  4771.1 1124.70
  4791.9 1115.44  4798.4 1110.64  4812.7 1107.68  4885.5 1104.61  4900.5 1102.00
  4927.1 1094.15  4943.3 1093.30  5041.6 1093.21  5041.9 1092.71  5046.7 1093.21
  5059.0 1096.44  5065.3 1099.11  5071.2 1104.25  5080.6 1106.68  5086.5 1110.41
  5090.3 1116.58  5101.9 1135.97  5107.8 1138.29  5165.5 1147.01  5224.3 1150.87
  5238.5 1153.72  5253.8 1159.40  5275.1 1161.56  5299.9 1167.85  5311.3 1169.52
#Mann=7,-1,0
  4635.9    0.07       0  4900.5    0.12       0  4943.3   0.033       0
  5041.6   0.033       0  5046.7   0.033       0  5090.3    0.12       0
  5299.9    0.07       0
Bank Sta=5041.6,5046.7
Exp/Cntr=0.3,0.1

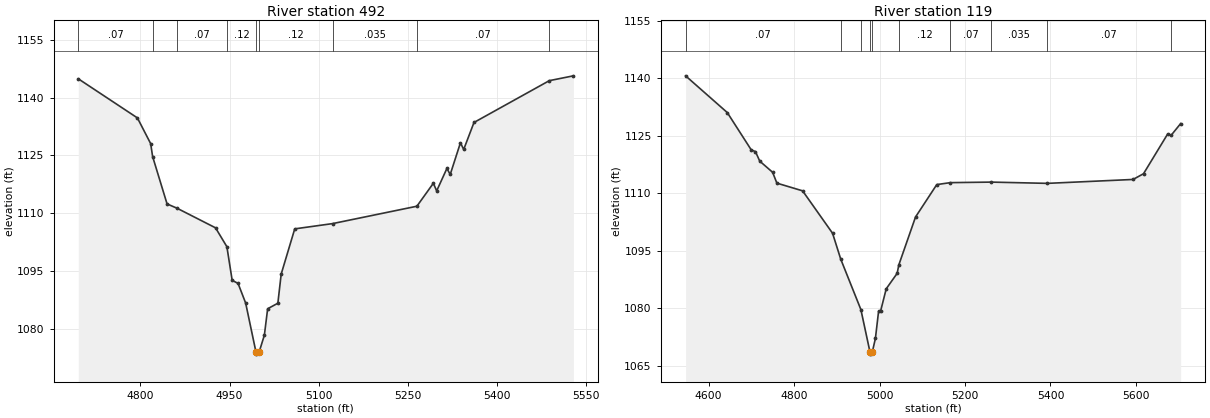
Type RM Length L Ch R = 1,492,373,373,373
BEGIN DESCRIPTION:
Stream0178_DS 1.0
END DESCRIPTION:
XS GIS Cut Line= 3
      2106620.91     13871642.30      2106475.00     13871375.00
      2105996.67     13871149.63
#Sta/Elev= 30
  4695.5 1144.84  4795.0 1134.72  4817.3 1128.07  4820.6 1124.72  4844.9 1112.47
  4861.6 1111.36  4926.5 1106.28  4945.6 1101.39  4954.5 1092.69  4964.4 1091.90
  4977.2 1086.81  4994.6 1074.10  4995.0 1073.60  4999.8 1074.10  5008.7 1078.51
  5014.2 1085.34  5031.4 1086.77  5037.0 1094.31  5059.8 1106.01  5123.4 1107.37
  5265.4 1111.87  5293.1 1117.81  5298.7 1115.84  5315.9 1121.64  5321.5 1120.09
  5338.7 1128.28  5344.2 1126.56  5361.5 1133.54  5488.3 1144.36  5528.8 1145.61
#Mann=9,-1,0
  4695.5    0.07       0  4820.6    0.12       0  4861.6    0.07       0
  4945.6    0.12       0  4994.6    0.05       0  4999.8    0.12       0
  5123.4   0.035       0  5265.4    0.07       0  5488.3   0.035       0
Bank Sta=4994.6,4999.8
Exp/Cntr=0.3,0.1

Type RM Length L Ch R = 1,119,0,0,0
BEGIN DESCRIPTION:
Stream0178_DS 0.0
END DESCRIPTION:
XS GIS Cut Line= 3
      2106756.94     13871578.16      2106724.38     13871125.33
      2106060.01     13870890.35
#Sta/Elev= 30
  4546.0 1140.63  4643.6 1131.05  4699.6 1121.33  4709.6 1120.85  4719.6 1118.38
  4749.7 1115.47  4759.7 1112.64  4819.9 1110.63  4890.0 1099.57  4909.2 1092.80
  4956.3 1079.66  4977.7 1068.54  4978.1 1068.04  4982.9 1068.54  4990.3 1072.13
  4997.7 1079.20  5002.3 1079.20  5015.6 1085.08  5041.2 1089.11  5045.1 1091.32
  5084.2 1103.81  5133.9 1112.26  5165.6 1112.77  5261.7 1112.91  5392.8 1112.58
  5593.3 1113.60  5617.8 1115.10  5674.3 1125.46  5682.6 1125.14  5704.7 1128.18
#Mann=10,-1,0
  4546.0    0.07       0  4909.2    0.12       0  4956.3    0.07       0
  4977.7    0.05       0  4982.9    0.07       0  5045.1    0.12       0
  5165.6    0.07       0  5261.7   0.035       0  5392.8    0.07       0
  5682.6    0.12       0
Bank Sta=4977.7,4982.9
Exp/Cntr=0.3,0.1

Chan Stop Cuts=-1