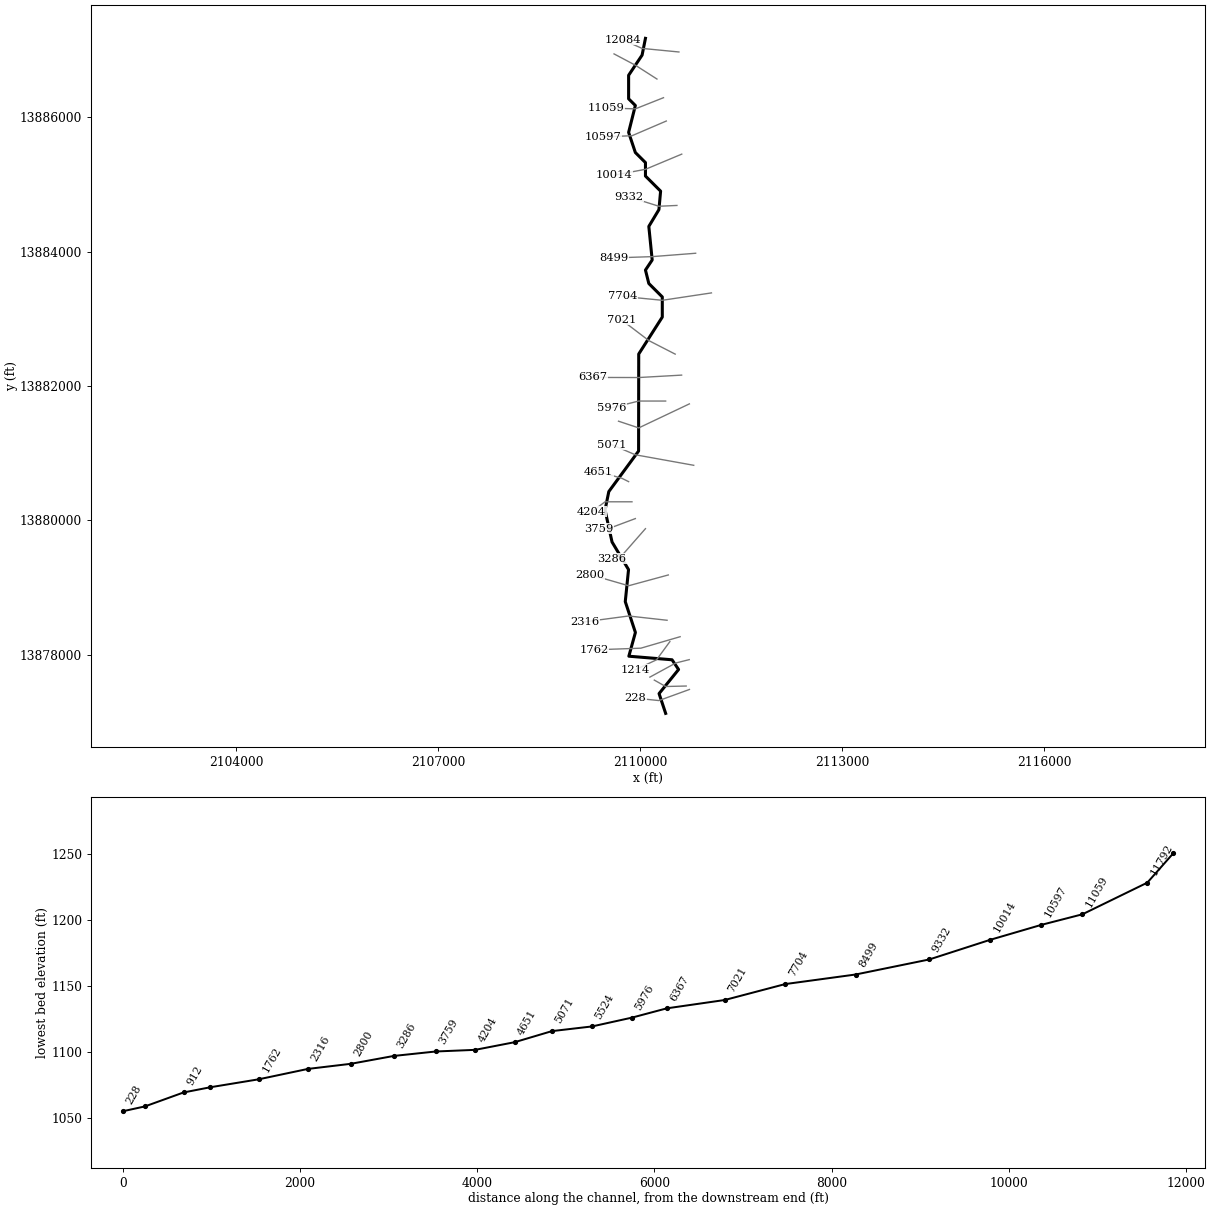
--- Stream0179_DS.prj (project) ---

Proj Title=Stream0179_DS Base Level Engineering
Current Plan=p01
Default Exp/Contr=0.3,0.1
English Units
Geom File=g01
Flow File=f01
Plan File=p01
BEGIN DESCRIPTION:
Stream0179_DS
END DESCRIPTION:

--- Stream0179_DS.p01 (plan) ---

Plan Title=Multiple Run
Short Identifier=Multiple
Geom File=g01
Flow File=f01
Subcritical Flow
K Sum by GR= 0
Std Step Tol= 0.01
Critical Tol= 0.01
Num of Std Step Trials= 20
Max Error Tol= 0.3
Flow Tol Ratio= 0.001
Split Flow NTrial= 30
Split Flow Tol= 0.02
Split Flow Ratio= 0.02
Log Output Level= 0
Friction Slope Method= 1
Unsteady Friction Slope Method= 2
Unsteady Bridges Friction Slope Method= 1
Parabolic Critical Depth
Global Vel Dist=  1 , 1 , 1
Global Log Level= 0
CheckData=True
Encroach Param= -1, 0, 0, 0
BEGIN DESCRIPTION:
Multiple Run
END DESCRIPTION:

--- Stream0179_DS.f01 (steady flow) ---

Flow Title=Multiple
Number of Profiles=7
Profile Names=10-year,25-year,50-year,1pct_min,100-year,1pct_plu,500-year
River Rch & RM= Stream0179_DS,Reach-1,12084
     236     359     466     295     588    1174     922
River Rch & RM= Stream0179_DS,Reach-1,11792
     765    1272    1747    1166    2327    4643    4074
River Rch & RM= Stream0179_DS,Reach-1,9332
    1776    3100    4397    3019    6024   12020   11190
River Rch & RM= Stream0179_DS,Reach-1,5976
    2363    4168    5952    4109    8198   16358   15398
Boundary for River Rch & Prof#=Stream0179_DS,Reach-1,1
Up Type=0
Dn Type=3
Dn Slope=0.005
Boundary for River Rch & Prof#=Stream0179_DS,Reach-1,2
Up Type=0
Dn Type=3
Dn Slope=0.005
Boundary for River Rch & Prof#=Stream0179_DS,Reach-1,3
Up Type=0
Dn Type=3
Dn Slope=0.005
Boundary for River Rch & Prof#=Stream0179_DS,Reach-1,4
Up Type=0
Dn Type=3
Dn Slope=0.005
Boundary for River Rch & Prof#=Stream0179_DS,Reach-1,5
Up Type=0
Dn Type=3
Dn Slope=0.005
Boundary for River Rch & Prof#=Stream0179_DS,Reach-1,6
Up Type=0
Dn Type=3
Dn Slope=0.005
Boundary for River Rch & Prof#=Stream0179_DS,Reach-1,7
Up Type=0
Dn Type=3
Dn Slope=0.005

--- Stream0179_DS.g01 (geometry) ---

Geom Title=Existing Conditions

River Reach=Stream0179_DS,Reach-1
Reach XY= 30
      2110075.00     13887175.00      2110025.00     13886925.00
      2109825.00     13886625.00      2109825.00     13886275.00
      2109925.00     13886175.00      2109825.00     13885775.00
      2109925.00     13885475.00      2110075.00     13885325.00
      2110075.00     13885125.00      2110300.00     13884900.00
      2110275.00     13884625.00      2110125.00     13884375.00
      2110175.00     13883875.00      2110075.00     13883725.00
      2110125.00     13883525.00      2110325.00     13883325.00
      2110325.00     13883025.00      2109975.00     13882475.00
      2109973.08     13881030.70      2109530.83     13880427.30
      2109474.70     13880152.15      2109578.82     13879676.58
      2109823.79     13879265.41      2109775.24     13878789.10
      2109925.83     13878329.56      2109828.43     13877976.22
      2110469.74     13877922.91      2110566.98     13877778.31
      2110277.16     13877419.55      2110375.00     13877125.00

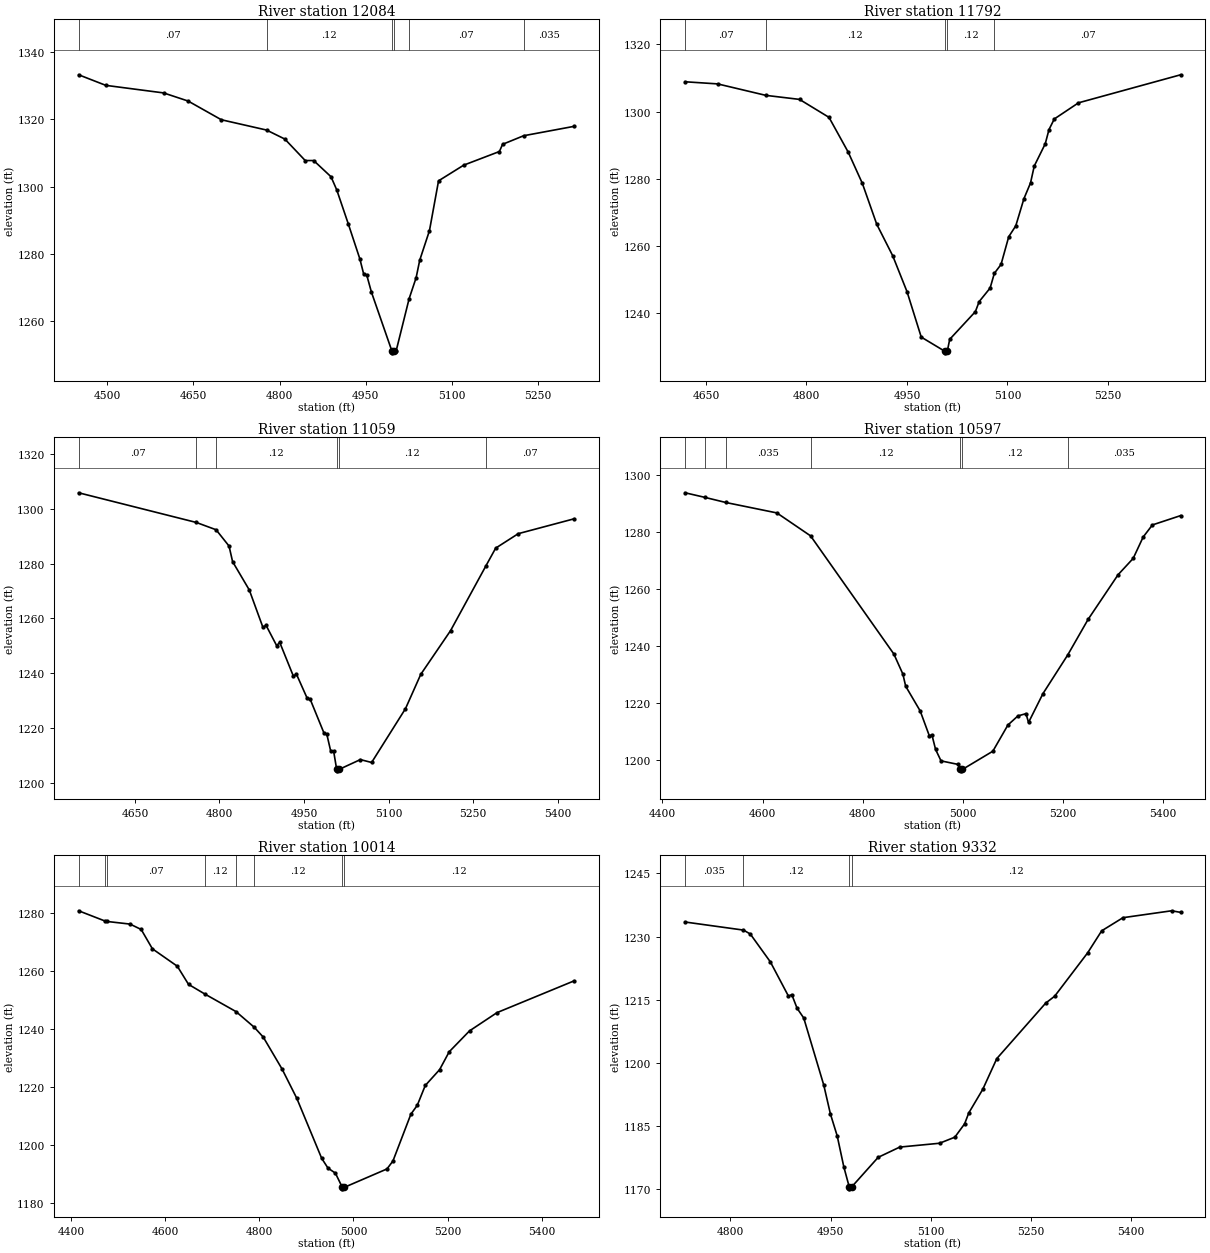
Type RM Length L Ch R = 1,12084,292,292,292
BEGIN DESCRIPTION:
Stream0179_DS 23.0
END DESCRIPTION:
XS GIS Cut Line= 3
      2110572.12     13886971.82      2110025.00     13887025.00
      2109739.41     13887152.11
#Sta/Elev= 30
  4450.3 1333.29  4497.6 1330.14  4598.1 1327.89  4640.8 1325.47  4698.6 1319.90
  4777.3 1316.83  4809.1 1314.15  4844.6 1307.75  4859.3 1307.75  4889.5 1302.92
  4899.5 1298.99  4919.6 1288.86  4939.7 1278.44  4946.5 1273.82  4951.6 1273.68
  4959.8 1268.57  4995.5 1250.99  4995.7 1250.49  4999.5 1250.99  5002.7 1250.99
  5025.4 1266.62  5037.6 1272.87  5043.8 1278.05  5060.8 1286.89  5076.6 1301.71
  5120.4 1306.38  5182.5 1310.44  5188.0 1312.58  5224.7 1315.14  5312.6 1317.94
#Mann=6,-1,0
  4450.3    0.07       0  4777.3    0.12       0  4995.5    0.05       0
  4999.5    0.12       0  5025.4    0.07       0  5224.7   0.035       0
Bank Sta=4995.5,4999.5
Exp/Cntr=0.3,0.1

Type RM Length L Ch R = 1,11792,733,733,733
BEGIN DESCRIPTION:
Stream0179_DS 22.0
END DESCRIPTION:
XS GIS Cut Line= 3
      2110245.77     13886569.04      2109925.00     13886775.00
      2109608.42     13886943.22
#Sta/Elev= 30
  4618.8 1308.90  4667.3 1308.27  4739.3 1304.86  4789.6 1303.66  4833.6 1298.32
  4862.3 1287.97  4883.4 1278.68  4904.9 1266.52  4928.7 1257.17  4950.1 1246.47
  4971.3 1232.98  5006.2 1228.80  5006.4 1228.30  5010.2 1228.80  5013.8 1232.32
  5052.1 1240.55  5057.8 1243.55  5074.1 1247.56  5080.4 1251.93  5090.4 1254.58
  5101.9 1262.83  5112.4 1266.06  5124.6 1274.15  5134.4 1278.81  5140.0 1283.85
  5156.4 1290.46  5162.0 1294.69  5169.9 1297.84  5206.0 1302.64  5358.5 1310.98
#Mann=5,-1,0
  4618.8    0.07       0  4739.3    0.12       0  5006.2    0.05       0
  5010.2    0.12       0  5080.4    0.07       0
Bank Sta=5006.2,5010.2
Exp/Cntr=0.3,0.1

Type RM Length L Ch R = 1,11059,462,462,462
BEGIN DESCRIPTION:
Stream0179_DS 21.0
END DESCRIPTION:
XS GIS Cut Line= 3
      2110343.05     13886291.27      2109925.00     13886125.00
      2109495.81     13886138.48
#Sta/Elev= 30
  4550.1 1305.95  4758.9 1295.10  4794.0 1292.43  4817.0 1286.47  4823.3 1280.77
  4852.9 1270.43  4877.2 1256.70  4882.6 1257.52  4901.5 1250.06  4906.9 1251.27
  4931.2 1238.89  4936.6 1239.63  4955.5 1230.89  4960.9 1230.50  4985.2 1218.23
  4990.5 1217.66  4997.3 1211.58  5002.5 1211.58  5008.0 1204.79  5008.3 1204.29
  5012.0 1204.79  5050.0 1208.40  5070.0 1207.35  5130.1 1227.03  5157.2 1239.57
  5210.1 1255.56  5272.3 1279.04  5290.1 1285.71  5330.2 1291.00  5429.4 1296.44
#Mann=6,-1,0
  4550.1    0.07       0  4758.9   0.035       0  4794.0    0.12       0
  5008.0    0.05       0  5012.0    0.12       0  5272.3    0.07       0
Bank Sta=5008,5012
Exp/Cntr=0.3,0.1

Type RM Length L Ch R = 1,10597,583,583,583
BEGIN DESCRIPTION:
Stream0179_DS 20.0
END DESCRIPTION:
XS GIS Cut Line= 3
      2110384.63     13885944.02      2109875.00     13885725.00
      2109440.24     13885707.92
#Sta/Elev= 30
  4445.3 1293.75  4484.1 1292.17  4526.5 1290.35  4628.6 1286.69  4695.9 1278.65
  4862.3 1237.24  4880.3 1230.21  4885.9 1225.95  4914.9 1217.28  4933.0 1208.64
  4938.4 1208.84  4945.6 1203.81  4956.5 1199.79  4990.9 1198.54  4995.3 1196.80
  4995.5 1196.30  4999.3 1196.80  5060.0 1203.18  5090.1 1212.36  5110.1 1215.55
  5126.2 1216.34  5131.3 1213.25  5160.1 1223.36  5209.6 1236.92  5250.2 1249.36
  5310.2 1265.04  5340.3 1270.75  5360.3 1278.26  5378.7 1282.48  5435.1 1285.75
#Mann=7,-1,0
  4445.3   0.035       0  4484.1    0.07       0  4526.5   0.035       0
  4695.9    0.12       0  4995.3    0.05       0  4999.3    0.12       0
  5209.6   0.035       0
Bank Sta=4995.3,4999.3
Exp/Cntr=0.3,0.1

Type RM Length L Ch R = 1,10014,682,682,682
BEGIN DESCRIPTION:
Stream0179_DS 19.0
END DESCRIPTION:
XS GIS Cut Line= 3
      2110613.83     13885450.98      2110075.00     13885225.00
      2109613.85     13885138.48
#Sta/Elev= 30
  4415.7 1280.74  4472.5 1277.16  4475.9 1277.06  4525.0 1276.15  4548.7 1274.29
  4572.5 1267.63  4625.5 1261.62  4649.3 1255.37  4683.5 1252.08  4750.3 1245.97
  4789.0 1240.58  4808.2 1237.18  4848.2 1226.16  4879.5 1216.07  4932.4 1195.38
  4945.8 1192.00  4961.6 1190.26  4976.3 1185.35  4976.6 1184.85  4980.3 1185.35
  5071.2 1191.71  5083.9 1194.44  5122.1 1210.61  5135.6 1213.64  5152.6 1220.49
  5183.1 1225.95  5203.5 1232.11  5246.7 1239.32  5305.2 1245.62  5469.2 1256.58
#Mann=8,-1,0
  4415.7    0.07       0  4472.5    0.12       0  4475.9    0.07       0
  4683.5    0.12       0  4750.3    0.07       0  4789.0    0.12       0
  4976.3    0.05       0  4980.3    0.12       0
Bank Sta=4976.3,4980.3
Exp/Cntr=0.3,0.1

Type RM Length L Ch R = 1,9332,833,833,833
BEGIN DESCRIPTION:
Stream0179_DS 18.0
END DESCRIPTION:
XS GIS Cut Line= 3
      2110542.63     13884687.09      2110275.00     13884675.00
      2109822.13     13884817.31
#Sta/Elev= 30
  4732.1 1233.45  4819.6 1231.53  4829.8 1230.60  4859.9 1223.97  4887.0 1215.84
  4892.0 1216.20  4899.9 1212.97  4909.9 1210.64  4939.9 1194.71  4949.9 1187.83
  4960.0 1182.66  4970.0 1175.25  4978.0 1170.56  4978.2 1170.06  4982.0 1170.56
  5021.4 1177.54  5053.8 1179.98  5113.4 1180.89  5136.3 1182.33  5151.0 1185.51
  5157.2 1188.09  5178.2 1193.71  5199.2 1201.00  5272.5 1214.19  5285.9 1215.82
  5335.4 1226.14  5356.4 1231.36  5388.3 1234.48  5461.2 1236.12  5474.7 1235.74
#Mann=4,-1,0
  4732.1   0.035       0  4819.6    0.12       0  4978.0    0.05       0
  4982.0    0.12       0
Bank Sta=4978,4982
Exp/Cntr=0.3,0.1

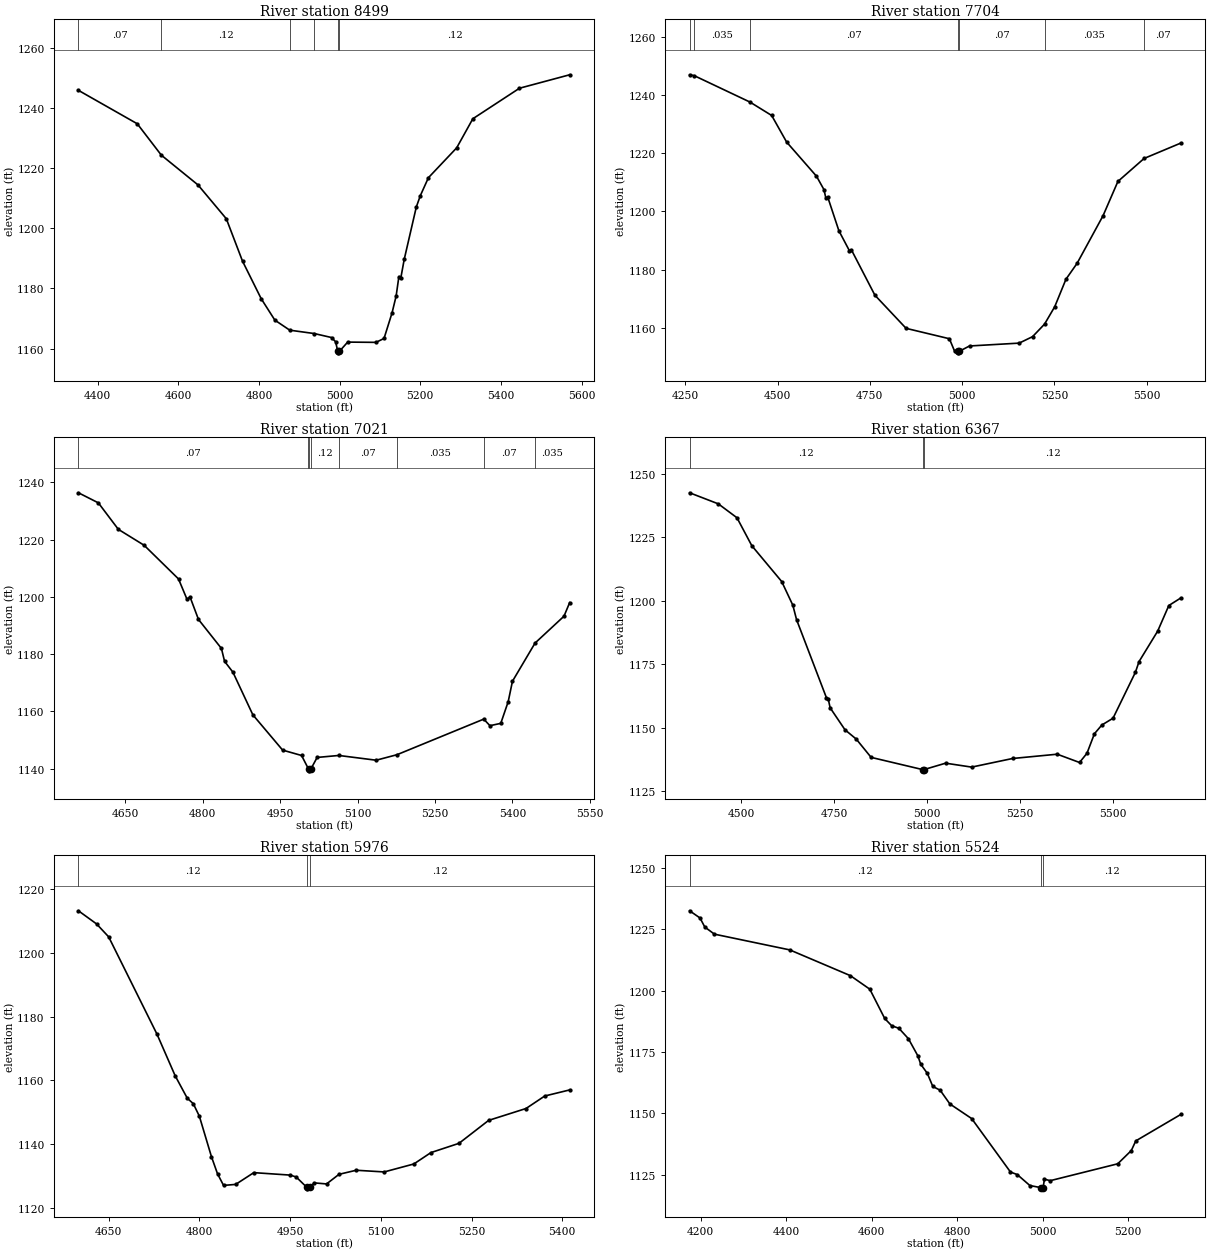
Type RM Length L Ch R = 1,8499,795,795,795
BEGIN DESCRIPTION:
Stream0179_DS 17.0
END DESCRIPTION:
XS GIS Cut Line= 3
      2110820.44     13883975.29      2110175.00     13883925.00
      2109605.12     13883905.84
#Sta/Elev= 30
  4352.6 1245.82  4498.5 1234.71  4558.1 1224.29  4648.9 1214.41  4719.2 1203.16
  4759.3 1189.09  4805.6 1176.61  4839.5 1169.48  4876.4 1166.15  4937.1 1165.03
  4979.9 1163.71  4990.0 1162.31  4995.5 1159.12  4995.7 1158.62  4999.5 1159.12
  5020.0 1162.19  5090.1 1162.10  5110.1 1163.40  5130.1 1171.96  5140.1 1177.51
  5146.9 1183.95  5151.9 1183.64  5160.1 1189.66  5190.1 1207.07  5200.1 1210.85
  5220.1 1216.80  5290.2 1226.73  5330.2 1236.38  5445.8 1246.52  5570.2 1250.99
#Mann=6,-1,0
  4352.6    0.07       0  4558.1    0.12       0  4876.4   0.035       0
  4937.1    0.12       0  4995.5    0.05       0  4999.5    0.12       0
Bank Sta=4995.5,4999.5
Exp/Cntr=0.3,0.1

Type RM Length L Ch R = 1,7704,683,683,683
BEGIN DESCRIPTION:
Stream0179_DS 16.0
END DESCRIPTION:
XS GIS Cut Line= 3
      2111054.86     13883385.01      2110325.00     13883275.00
      2109735.34     13883332.93
#Sta/Elev= 30
  4261.9 1246.95  4274.7 1246.63  4425.4 1237.57  4484.2 1232.96  4524.7 1223.82
  4605.6 1212.08  4625.8 1207.47  4630.9 1204.60  4636.0 1204.92  4666.3 1193.32
  4694.8 1186.45  4699.9 1186.83  4763.8 1171.17  4848.3 1159.78  4965.5 1156.21
  4979.8 1151.89  4987.9 1151.86  4988.1 1151.36  4991.9 1151.86  5020.1 1153.72
  5154.6 1154.70  5190.9 1156.93  5223.3 1161.23  5250.9 1167.22  5281.3 1176.67
  5311.5 1182.14  5381.8 1198.51  5422.0 1210.28  5492.9 1218.18  5592.5 1223.48
#Mann=7,-1,0
  4261.9    0.07       0  4274.7   0.035       0  4425.4    0.07       0
  4987.9    0.05       0  4991.9    0.07       0  5223.3   0.035       0
  5492.9    0.07       0
Bank Sta=4987.9,4991.9
Exp/Cntr=0.3,0.1

Type RM Length L Ch R = 1,7021,654,654,654
BEGIN DESCRIPTION:
Stream0179_DS 15.0
END DESCRIPTION:
XS GIS Cut Line= 3
      2110516.62     13882473.55      2110125.00     13882675.00
      2109718.99     13882984.95
#Sta/Elev= 30
  4559.6 1236.38  4598.2 1232.86  4636.9 1223.61  4686.9 1218.04  4753.4 1206.29
  4770.0 1199.12  4775.6 1200.05  4792.1 1192.13  4836.5 1182.02  4842.6 1177.51
  4858.7 1173.74  4897.4 1158.82  4955.0 1146.51  4991.7 1144.63  5005.0 1139.95
  5005.3 1139.77  5005.5 1139.27  5009.3 1139.77  5021.8 1143.95  5063.8 1144.64
  5136.1 1142.98  5176.4 1144.90  5344.4 1157.33  5356.4 1155.04  5377.4 1155.85
  5391.8 1163.44  5400.0 1170.55  5443.8 1183.90  5499.8 1193.27  5510.8 1198.03
#Mann=8,-1,0
  4559.6    0.07       0  5005.0    0.12       0  5005.3    0.05       0
  5009.3    0.12       0  5063.8    0.07       0  5176.4   0.035       0
  5344.4    0.07       0  5443.8   0.035       0
Bank Sta=5005.3,5009.3
Exp/Cntr=0.3,0.1

Type RM Length L Ch R = 1,6367,391,391,391
BEGIN DESCRIPTION:
Stream0179_DS 14.0
END DESCRIPTION:
XS GIS Cut Line= 3
      2110612.08     13882161.05      2109975.00     13882125.00
      2109292.70     13882126.33
#Sta/Elev= 30
  4361.9 1242.61  4439.1 1238.24  4489.2 1232.76  4529.2 1221.72  4609.4 1207.62
  4639.4 1198.26  4649.4 1192.57  4729.5 1161.84  4734.5 1161.34  4739.6 1157.82
  4779.6 1149.13  4809.7 1145.49  4849.8 1138.26  4988.0 1133.45  4988.2 1132.95
  4992.0 1133.45  5050.0 1135.97  5120.0 1134.42  5230.0 1137.82  5350.0 1139.51
  5410.0 1136.24  5430.0 1139.89  5450.0 1147.58  5470.0 1151.03  5500.0 1153.70
  5560.0 1171.77  5570.0 1176.06  5620.0 1188.05  5650.0 1198.15  5682.3 1201.14
#Mann=3,-1,0
  4361.9    0.12       0  4988.0    0.05       0  4992.0    0.12       0
Bank Sta=4988,4992
Exp/Cntr=0.3,0.1

Type RM Length L Ch R = 1,5976,452,452,452
BEGIN DESCRIPTION:
Stream0179_DS 13.0
END DESCRIPTION:
XS GIS Cut Line= 3
      2110374.99     13881775.00      2109975.00     13881775.00
      2109575.00     13881675.00
#Sta/Elev= 30
  4599.9 1213.31  4629.9 1209.18  4649.9 1205.12  4729.9 1174.51  4759.9 1161.46
  4779.9 1154.41  4789.9 1152.69  4799.9 1148.75  4819.9 1136.03  4829.9 1130.67
  4839.9 1127.02  4859.9 1127.33  4889.9 1131.03  4949.9 1130.26  4959.9 1129.68
  4977.4 1126.44  4977.7 1125.94  4982.4 1126.44  4989.9 1127.81  5010.2 1127.48
  5030.8 1130.50  5059.2 1131.78  5105.5 1131.25  5154.5 1133.75  5182.8 1137.33
  5229.2 1140.24  5278.2 1147.45  5340.0 1151.18  5371.0 1155.11  5412.2 1157.02
#Mann=3,-1,0
  4599.9    0.12       0  4977.4    0.05       0  4982.4    0.12       0
Bank Sta=4977.4,4982.4
Exp/Cntr=0.3,0.1

Type RM Length L Ch R = 1,5524,453,453,453
BEGIN DESCRIPTION:
Stream0179_DS 12.0
END DESCRIPTION:
XS GIS Cut Line= 3
      2110727.17     13881732.68      2109975.00     13881375.00
      2109675.02     13881474.99
#Sta/Elev= 30
  4173.9 1232.55  4198.2 1229.62  4209.5 1225.91  4232.0 1223.02  4408.2 1216.61
  4550.0 1206.11  4595.4 1200.60  4630.3 1188.65  4646.4 1185.73  4663.5 1184.65
  4685.7 1180.42  4707.8 1173.44  4714.5 1170.03  4730.0 1166.28  4742.8 1160.95
  4760.0 1159.42  4782.7 1153.83  4833.7 1147.87  4924.5 1126.07  4940.4 1125.04
  4969.9 1120.57  4995.6 1119.73  4996.0 1119.23  5000.7 1119.73  5004.0 1123.18
  5017.3 1122.55  5175.4 1129.44  5207.1 1134.83  5217.6 1138.77  5323.0 1149.56
#Mann=3,-1,0
  4173.9    0.12       0  4995.6    0.05       0  5000.7    0.12       0
Bank Sta=4995.6,5000.7
Exp/Cntr=0.3,0.1

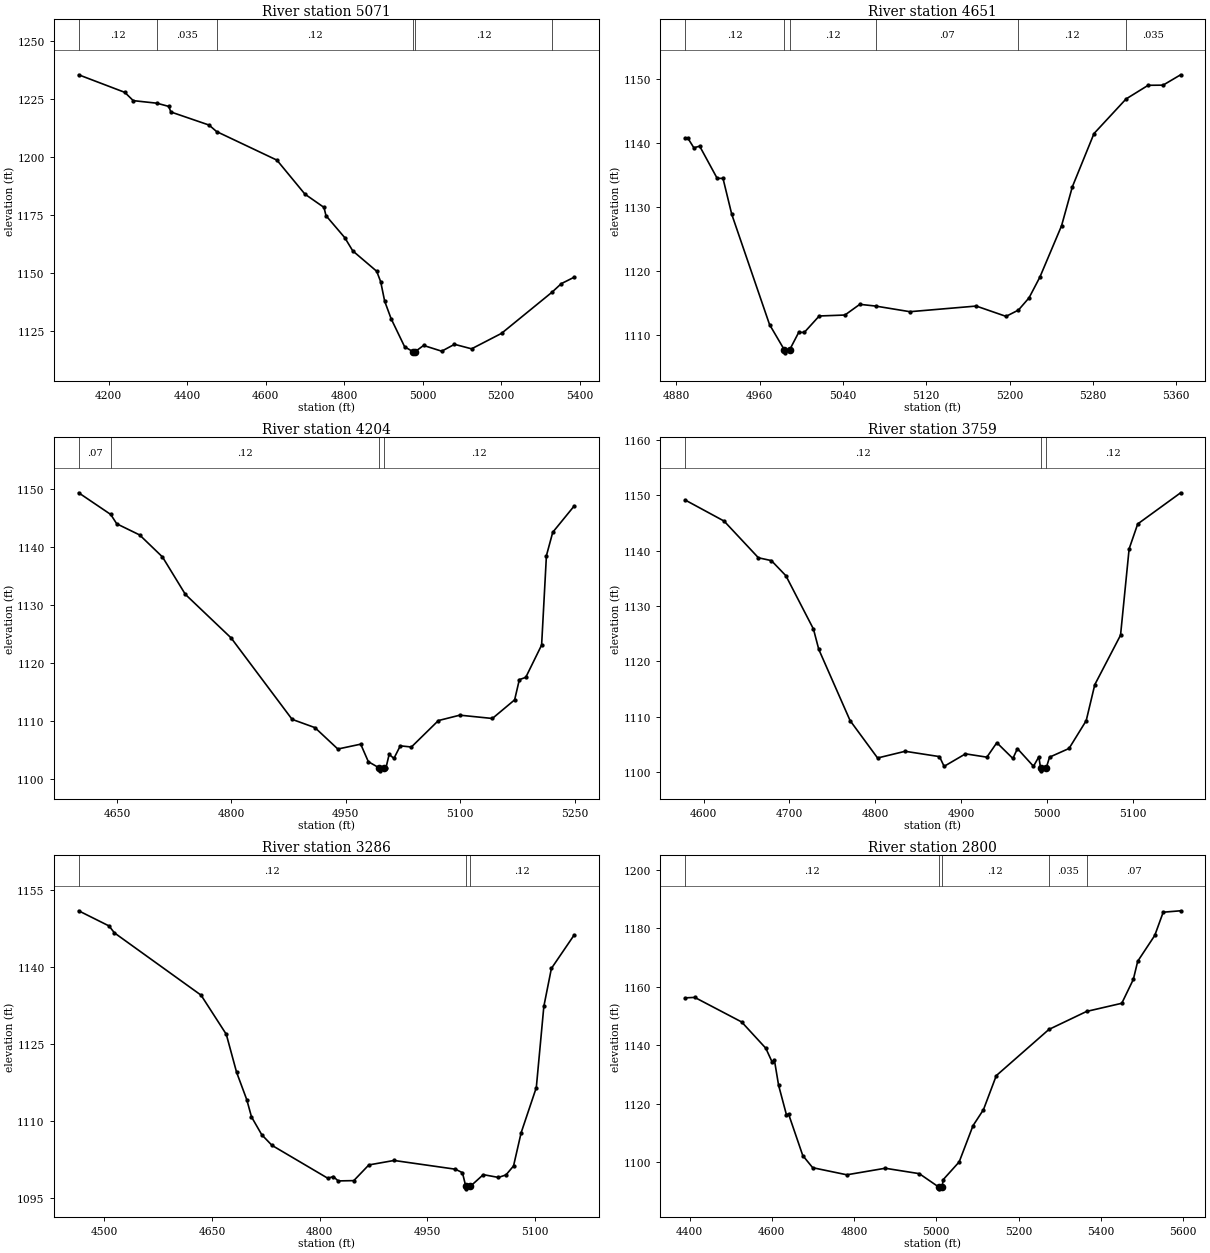
Type RM Length L Ch R = 1,5071,420,420,420
BEGIN DESCRIPTION:
Stream0179_DS 11.0
END DESCRIPTION:
XS GIS Cut Line= 3
      2110791.84     13880818.45      2109925.00     13880975.00
      2109574.96     13881125.02
#Sta/Elev= 30
  4123.9 1235.45  4241.4 1227.88  4263.0 1224.31  4323.0 1223.21  4353.5 1221.82
  4358.6 1219.44  4456.0 1213.79  4475.1 1211.00  4628.8 1198.68  4700.1 1184.04
  4748.6 1178.32  4753.7 1174.77  4801.5 1165.29  4821.9 1159.59  4882.8 1150.82
  4893.0 1146.29  4903.1 1137.93  4919.4 1130.43  4954.0 1118.27  4975.3 1116.18
  4975.7 1115.68  4980.6 1116.18  5002.2 1118.86  5048.3 1116.39  5080.9 1119.35
  5124.4 1117.41  5200.6 1124.07  5329.0 1141.77  5352.9 1145.49  5385.6 1148.25
#Mann=6,-1,0
  4123.9    0.12       0  4323.0   0.035       0  4475.1    0.12       0
  4975.3    0.05       0  4980.6    0.12       0  5329.0   0.035       0
Bank Sta=4975.3,4980.6
Exp/Cntr=0.3,0.1

Type RM Length L Ch R = 1,4651,447,447,447
BEGIN DESCRIPTION:
Stream0179_DS 10.0
END DESCRIPTION:
XS GIS Cut Line= 3
      2109825.04     13880574.98      2109725.00     13880625.00
      2109374.96     13880725.01
#Sta/Elev= 30
  4888.4 1140.75  4891.2 1140.75  4896.8 1139.29  4902.4 1139.54  4919.2 1134.52
  4924.8 1134.51  4933.2 1128.91  4969.5 1111.70  4983.6 1107.79  4984.0 1107.29
  4988.9 1107.79  4997.5 1110.48  5002.9 1110.48  5017.2 1113.04  5041.9 1113.19
  5056.2 1114.86  5071.3 1114.59  5104.3 1113.71  5168.0 1114.59  5196.6 1112.98
  5208.5 1113.96  5218.7 1115.87  5229.1 1119.10  5249.9 1127.10  5260.3 1133.20
  5281.1 1141.51  5311.9 1146.91  5333.1 1149.04  5347.4 1149.06  5364.3 1150.68
#Mann=6,-1,0
  4888.4    0.12       0  4983.6    0.05       0  4988.9    0.12       0
  5071.3    0.07       0  5208.5    0.12       0  5311.9   0.035       0
Bank Sta=4983.6,4988.9
Exp/Cntr=0.3,0.1

Type RM Length L Ch R = 1,4204,445,445,445
BEGIN DESCRIPTION:
Stream0179_DS 9.0
END DESCRIPTION:
XS GIS Cut Line= 3
      2109875.02     13880275.00      2109475.00     13880275.00
      2109275.02     13880125.01
#Sta/Elev= 30
  4599.5 1149.42  4641.6 1145.68  4649.5 1144.07  4679.5 1142.15  4709.5 1138.35
  4739.5 1131.90  4799.5 1124.39  4879.5 1110.35  4909.5 1108.92  4939.5 1105.23
  4969.5 1106.07  4979.5 1103.05  4993.8 1101.97  4994.3 1101.47  5000.3 1101.97
  5002.6 1101.97  5006.8 1104.30  5013.1 1103.62  5021.4 1105.78  5036.0 1105.58
  5071.4 1110.14  5099.5 1111.07  5142.2 1110.50  5171.4 1113.71  5177.6 1117.20
  5186.0 1117.59  5206.8 1123.16  5213.1 1138.58  5221.4 1142.61  5249.5 1147.14
#Mann=4,-1,0
  4599.5    0.07       0  4641.6    0.12       0  4993.8    0.05       0
  5000.3    0.12       0
Bank Sta=4993.8,5000.3
Exp/Cntr=0.3,0.1

Type RM Length L Ch R = 1,3759,473,473,473
BEGIN DESCRIPTION:
Stream0179_DS 8.0
END DESCRIPTION:
XS GIS Cut Line= 3
      2109924.97     13880024.99      2109525.00     13879875.00
      2109374.97     13879875.00
#Sta/Elev= 30
  4578.5 1149.14  4623.9 1145.33  4663.9 1138.70  4679.0 1138.19  4695.9 1135.46
  4728.0 1125.83  4734.2 1122.16  4770.7 1109.29  4802.7 1102.54  4834.8 1103.75
  4874.8 1102.79  4880.2 1101.03  4905.1 1103.29  4930.0 1102.69  4941.6 1105.30
  4960.3 1102.45  4965.6 1104.23  4984.3 1101.04  4990.5 1102.75  4992.6 1100.72
  4993.1 1100.22  4999.1 1100.72  5003.0 1102.69  5025.7 1104.26  5045.7 1109.28
  5055.7 1115.78  5085.7 1124.72  5095.7 1140.31  5105.7 1144.81  5155.7 1150.44
#Mann=3,-1,0
  4578.5    0.12       0  4992.6    0.05       0  4999.1    0.12       0
Bank Sta=4992.6,4999.1
Exp/Cntr=0.3,0.1

Type RM Length L Ch R = 1,3286,486,486,486
BEGIN DESCRIPTION:
Stream0179_DS 7.0
END DESCRIPTION:
XS GIS Cut Line= 3
      2110075.03     13879875.03      2109725.00     13879475.00
      2109574.96     13879424.99
#Sta/Elev= 30
  4464.5 1150.95  4506.8 1148.00  4514.4 1146.64  4634.9 1134.53  4670.0 1126.92
  4684.3 1119.55  4698.5 1114.20  4705.1 1110.85  4719.4 1107.37  4733.6 1105.31
  4811.4 1098.90  4819.0 1099.25  4825.7 1098.39  4847.5 1098.45  4868.4 1101.50
  4903.5 1102.37  4988.9 1100.67  4998.7 1099.99  5003.3 1097.35  5003.8 1096.85
  5009.8 1097.35  5027.7 1099.61  5048.8 1099.07  5059.3 1099.56  5069.8 1101.30
  5080.4 1107.77  5101.5 1116.55  5112.0 1132.36  5122.5 1139.73  5154.2 1146.24
#Mann=3,-1,0
  4464.5    0.12       0  5003.3    0.05       0  5009.8    0.12       0
Bank Sta=5003.3,5009.8
Exp/Cntr=0.3,0.1

Type RM Length L Ch R = 1,2800,484,484,484
BEGIN DESCRIPTION:
Stream0179_DS 6.0
END DESCRIPTION:
XS GIS Cut Line= 3
      2110414.31     13879185.74      2109825.00     13879025.00
      2109254.55     13879190.47
#Sta/Elev= 30
  4389.2 1156.17  4412.7 1156.33  4526.7 1147.93  4585.4 1138.95  4601.0 1134.16
  4606.2 1135.00  4616.5 1126.30  4635.5 1116.24  4640.7 1116.47  4675.3 1102.25
  4699.4 1098.10  4782.4 1095.67  4875.7 1097.91  4958.6 1096.06  5007.1 1091.37
  5007.6 1090.87  5013.7 1091.37  5016.8 1094.03  5055.6 1100.08  5089.2 1112.47
  5114.6 1117.94  5145.8 1129.58  5273.7 1145.37  5365.5 1151.54  5450.9 1154.32
  5479.0 1162.49  5489.6 1168.68  5531.1 1177.52  5551.6 1185.46  5594.0 1185.95
#Mann=5,-1,0
  4389.2    0.12       0  5007.1    0.05       0  5013.7    0.12       0
  5273.7   0.035       0  5365.5    0.07       0
Bank Sta=5007.1,5013.7
Exp/Cntr=0.3,0.1

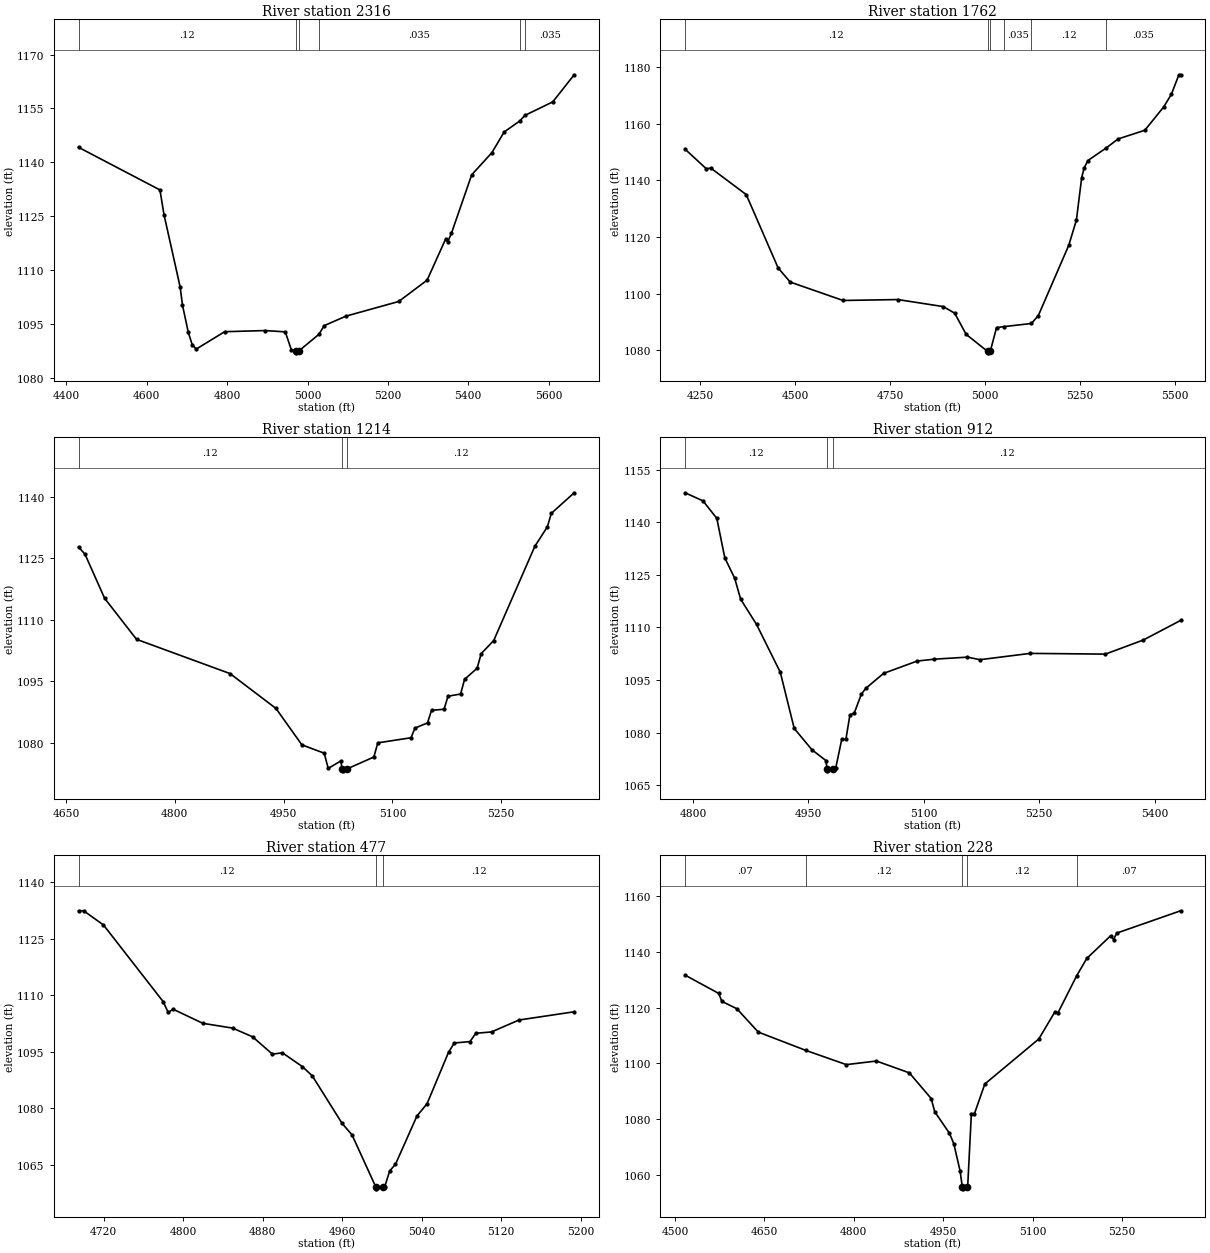
Type RM Length L Ch R = 1,2316,554,554,554
BEGIN DESCRIPTION:
Stream0179_DS 5.0
END DESCRIPTION:
XS GIS Cut Line= 3
      2110396.13     13878511.26      2109825.00     13878575.00
      2109172.17     13878487.83
#Sta/Elev= 30
  4430.2 1144.18  4632.6 1132.33  4642.6 1125.49  4682.9 1105.30  4688.6 1100.33
  4703.0 1092.75  4713.1 1089.19  4723.1 1088.06  4793.6 1092.88  4894.2 1093.20
  4944.5 1092.84  4959.7 1087.81  4971.3 1087.50  4971.8 1087.00  4978.0 1087.50
  5028.2 1092.15  5041.4 1094.57  5095.7 1097.22  5226.8 1101.29  5297.5 1107.23
  5343.9 1118.75  5348.9 1117.90  5358.0 1120.26  5408.4 1136.53  5458.9 1142.73
  5489.1 1148.44  5527.7 1151.50  5541.1 1153.09  5610.2 1156.84  5663.5 1164.38
#Mann=6,-1,0
  4430.2    0.12       0  4971.3    0.05       0  4978.0    0.12       0
  5028.2   0.035       0  5527.7    0.12       0  5541.1   0.035       0
Bank Sta=4971.3,4978
Exp/Cntr=0.3,0.1

Type RM Length L Ch R = 1,1762,548,548,548
BEGIN DESCRIPTION:
Stream0179_DS 4.0
END DESCRIPTION:
XS GIS Cut Line= 3
      2110590.08     13878266.47      2110006.65     13878095.61
      2109310.73     13878070.61
#Sta/Elev= 30
  4210.1 1150.95  4265.5 1144.11  4277.9 1144.28  4371.0 1134.95  4455.0 1109.07
  4486.9 1104.09  4625.8 1097.61  4769.9 1097.93  4889.7 1095.45  4919.7 1093.11
  4949.8 1085.67  5006.3 1079.64  5006.8 1079.14  5013.3 1079.64  5029.8 1088.04
  5048.6 1088.38  5121.7 1089.49  5139.9 1092.30  5219.9 1117.06  5240.0 1125.93
  5253.9 1140.85  5260.0 1144.18  5270.0 1146.93  5318.7 1151.41  5350.0 1154.58
  5420.1 1157.63  5470.1 1165.91  5490.1 1170.34  5509.8 1177.20  5514.4 1177.20
#Mann=6,-1,0
  4210.1    0.12       0  5006.3    0.05       0  5013.3    0.12       0
  5048.6   0.035       0  5121.7    0.12       0  5318.7   0.035       0
Bank Sta=5006.3,5013.3
Exp/Cntr=0.3,0.1

Type RM Length L Ch R = 1,1214,302,302,302
BEGIN DESCRIPTION:
Stream0179_DS 3.0
END DESCRIPTION:
XS GIS Cut Line= 3
      2110437.76     13878193.55      2110239.85     13877922.72
      2109925.01     13877775.01
#Sta/Elev= 30
  4667.4 1127.77  4676.2 1126.02  4703.2 1115.26  4747.2 1105.23  4876.2 1096.85
  4939.5 1088.33  4975.2 1079.44  5006.0 1077.40  5011.5 1073.68  5028.8 1075.50
  5030.7 1073.59  5031.2 1073.09  5037.8 1073.59  5074.4 1076.47  5079.9 1079.93
  5125.6 1081.17  5131.1 1083.53  5148.4 1084.81  5153.9 1087.86  5171.2 1088.15
  5176.7 1091.33  5194.0 1091.86  5199.5 1095.45  5216.8 1098.16  5222.4 1101.73
  5239.7 1104.94  5296.3 1127.93  5313.6 1132.71  5319.1 1136.01  5350.6 1141.04
#Mann=3,-1,0
  4667.4    0.12       0  5030.7    0.05       0  5037.8    0.12       0
Bank Sta=5030.7,5037.8
Exp/Cntr=0.3,0.1

Type RM Length L Ch R = 1,912,435,435,435
BEGIN DESCRIPTION:
Stream0179_DS 2.0
END DESCRIPTION:
XS GIS Cut Line= 3
      2110725.02     13877925.00      2110525.00     13877875.00
      2110140.88     13877664.90
#Sta/Elev= 30
  4789.7 1148.39  4812.9 1146.09  4830.9 1141.11  4841.3 1129.85  4854.1 1124.04
  4861.9 1118.05  4882.5 1110.88  4913.4 1097.24  4931.5 1081.22  4954.6 1075.12
  4972.7 1072.06  4974.2 1069.63  4974.7 1069.13  4981.4 1069.63  4985.6 1070.07
  4993.3 1078.13  4998.7 1078.13  5003.9 1085.08  5009.6 1085.63  5018.7 1090.96
  5024.4 1092.62  5047.6 1096.90  5091.2 1100.42  5113.0 1100.95  5156.7 1101.54
  5172.8 1100.81  5238.2 1102.61  5335.9 1102.40  5385.3 1106.43  5433.7 1112.01
#Mann=3,-1,0
  4789.7    0.12       0  4974.2    0.05       0  4981.4    0.12       0
Bank Sta=4974.2,4981.4
Exp/Cntr=0.3,0.1

Type RM Length L Ch R = 1,477,249,249,249
BEGIN DESCRIPTION:
Stream0179_DS 1.0
END DESCRIPTION:
XS GIS Cut Line= 3
      2110679.99     13877532.10      2110375.00     13877525.00
      2110206.58     13877620.31
#Sta/Elev= 30
  4694.9 1132.46  4699.9 1132.46  4719.9 1128.69  4779.9 1108.34  4785.0 1105.45
  4790.0 1106.30  4819.9 1102.55  4849.9 1101.28  4869.9 1098.97  4889.9 1094.36
  4899.9 1094.72  4920.0 1091.06  4930.0 1088.59  4960.0 1075.96  4970.0 1072.90
  4993.9 1059.07  4994.4 1058.57  5001.1 1059.07  5002.8 1059.07  5007.9 1063.35
  5013.7 1065.09  5035.3 1077.93  5045.5 1081.20  5067.1 1094.86  5072.9 1097.33
  5088.7 1097.70  5094.5 1099.90  5110.4 1100.27  5137.9 1103.43  5193.5 1105.62
#Mann=3,-1,0
  4694.9    0.12       0  4993.9    0.05       0  5001.1    0.12       0
Bank Sta=4993.9,5001.1
Exp/Cntr=0.3,0.1

Type RM Length L Ch R = 1,228,0,0,0
BEGIN DESCRIPTION:
Stream0179_DS 0.0
END DESCRIPTION:
XS GIS Cut Line= 3
      2110728.21     13877480.94      2110274.45     13877315.73
      2109928.51     13877351.62
#Sta/Elev= 30
  4517.1 1131.70  4573.4 1125.14  4578.7 1122.28  4603.9 1119.62  4639.8 1111.23
  4719.2 1104.68  4787.4 1099.54  4837.9 1100.83  4893.0 1096.58  4929.6 1087.36
  4935.6 1082.61  4960.2 1074.89  4967.5 1071.14  4978.1 1061.33  4981.9 1055.40
  4982.4 1054.90  4989.1 1055.40  4990.8 1055.60  4997.0 1081.94  5002.2 1081.94
  5019.6 1092.59  5110.0 1108.75  5136.7 1118.39  5141.8 1118.00  5173.6 1131.50
  5190.5 1137.71  5230.4 1145.84  5235.4 1144.49  5240.7 1146.81  5347.8 1154.83
#Mann=5,-1,0
  4517.1    0.07       0  4719.2    0.12       0  4981.9    0.05       0
  4989.1    0.12       0  5173.6    0.07       0
Bank Sta=4981.9,4989.1
Exp/Cntr=0.3,0.1

Chan Stop Cuts=-1