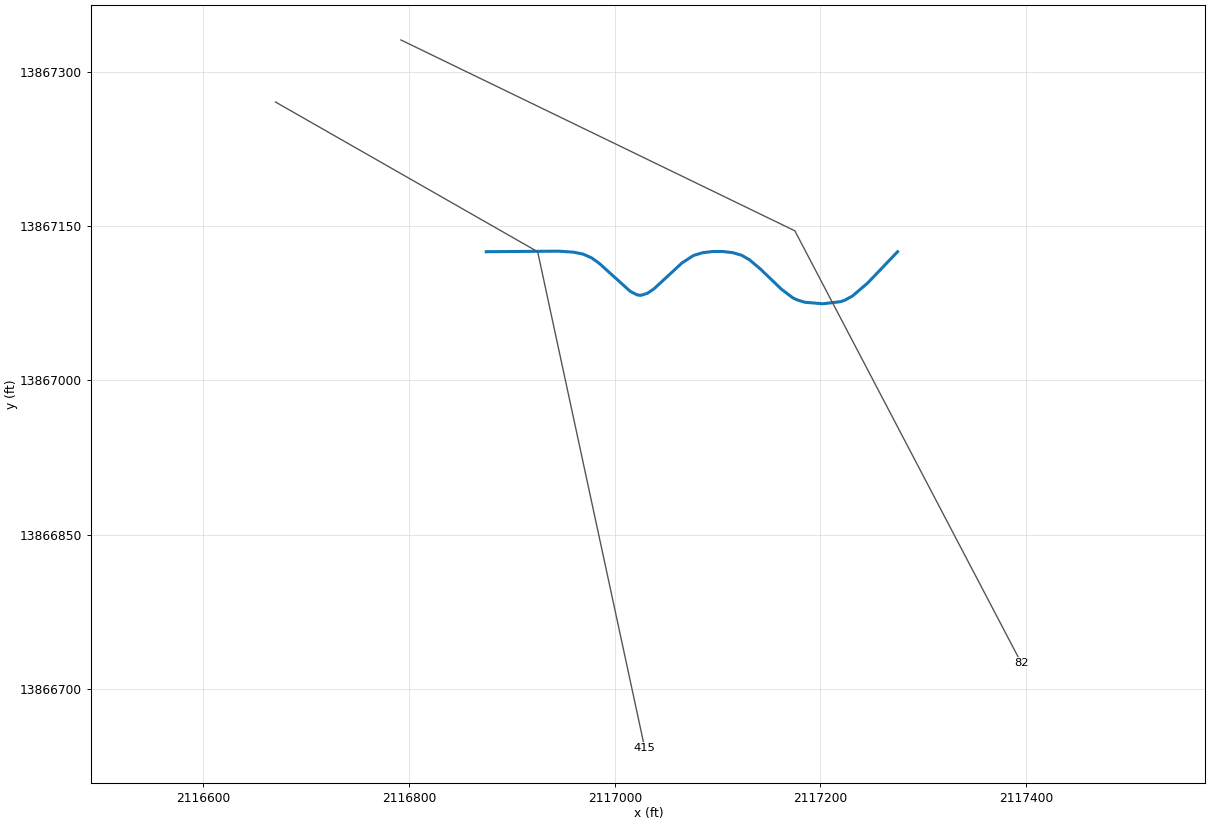
--- Stream0180_DS.prj (project) ---

Proj Title=Stream0180_DS Base Level Engineering
Current Plan=p01
Default Exp/Contr=0.3,0.1
English Units
Geom File=g01
Flow File=f01
Plan File=p01
BEGIN DESCRIPTION:
Stream0180_DS
END DESCRIPTION:

--- Stream0180_DS.p01 (plan) ---

Plan Title=Multiple Run
Short Identifier=Multiple
Geom File=g01
Flow File=f01
Subcritical Flow
K Sum by GR= 0
Std Step Tol= 0.01
Critical Tol= 0.01
Num of Std Step Trials= 20
Max Error Tol= 0.3
Flow Tol Ratio= 0.001
Split Flow NTrial= 30
Split Flow Tol= 0.02
Split Flow Ratio= 0.02
Log Output Level= 0
Friction Slope Method= 1
Unsteady Friction Slope Method= 2
Unsteady Bridges Friction Slope Method= 1
Parabolic Critical Depth
Global Vel Dist=  1 , 1 , 1
Global Log Level= 0
CheckData=True
Encroach Param= -1, 0, 0, 0
BEGIN DESCRIPTION:
Multiple Run
END DESCRIPTION:

--- Stream0180_DS.f01 (steady flow) ---

Flow Title=Multiple
Number of Profiles=7
Profile Names=10-year,25-year,50-year,1pct_min,100-year,1pct_plu,500-year
River Rch & RM= Stream0180_DS,Reach-1,415
    1084    1832    2542    1709    3410    6803    6068
Boundary for River Rch & Prof#=Stream0180_DS,Reach-1,1
Up Type=0
Dn Type=3
Dn Slope=0.005
Boundary for River Rch & Prof#=Stream0180_DS,Reach-1,2
Up Type=0
Dn Type=3
Dn Slope=0.005
Boundary for River Rch & Prof#=Stream0180_DS,Reach-1,3
Up Type=0
Dn Type=3
Dn Slope=0.005
Boundary for River Rch & Prof#=Stream0180_DS,Reach-1,4
Up Type=0
Dn Type=3
Dn Slope=0.005
Boundary for River Rch & Prof#=Stream0180_DS,Reach-1,5
Up Type=0
Dn Type=3
Dn Slope=0.005
Boundary for River Rch & Prof#=Stream0180_DS,Reach-1,6
Up Type=0
Dn Type=3
Dn Slope=0.005
Boundary for River Rch & Prof#=Stream0180_DS,Reach-1,7
Up Type=0
Dn Type=3
Dn Slope=0.005

--- Stream0180_DS.g01 (geometry) ---

Geom Title=Existing Conditions

River Reach=Stream0180_DS,Reach-1
Reach XY= 30
      2116875.00     13867125.00      2116945.30     13867125.54
      2116959.95     13867124.54      2116969.23     13867122.66
      2116977.49     13867119.01      2116984.81     13867113.75
      2117015.09     13867086.41      2117021.70     13867083.05
      2117025.01     13867082.55      2117031.62     13867084.48
      2117038.23     13867089.01      2117065.33     13867114.08
      2117076.64     13867121.39      2117085.62     13867124.07
      2117095.13     13867125.17      2117104.80     13867125.21
      2117114.30     13867124.18      2117123.27     13867121.59
      2117130.94     13867117.15      2117141.52     13867108.26
      2117161.92     13867088.65      2117172.77     13867080.41
      2117176.67     13867078.37      2117184.78     13867075.87
      2117202.14     13867074.40      2117219.37     13867076.39
      2117223.40     13867077.71      2117231.15     13867081.95
      2117245.92     13867094.60      2117275.00     13867125.00

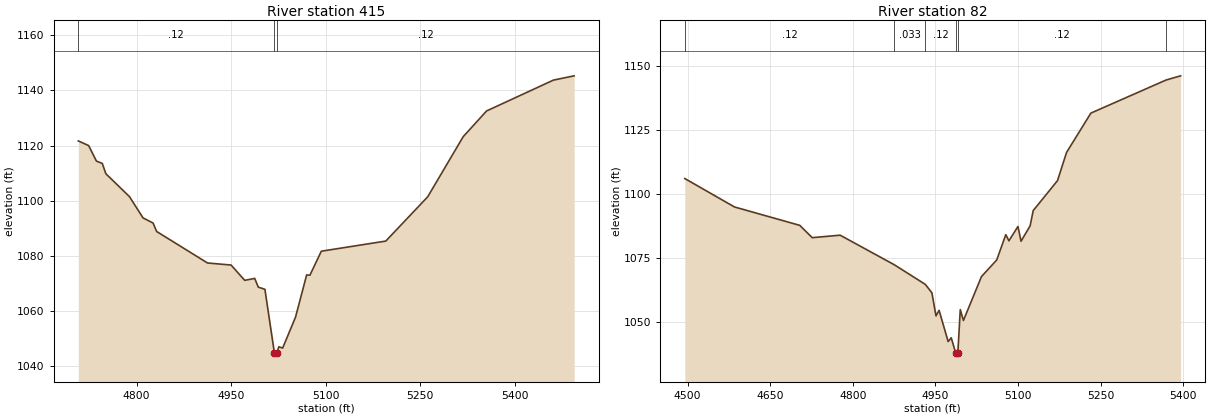
Type RM Length L Ch R = 1,415,333,333,333
BEGIN DESCRIPTION:
Stream0180_DS 2.0
END DESCRIPTION:
XS GIS Cut Line= 3
      2116670.10     13867270.56      2116925.00     13867125.00
      2117029.02     13866642.83
#Sta/Elev= 30
  4707.6 1121.68  4724.0 1119.99  4736.3 1114.39  4745.6 1113.53  4751.3 1109.80
  4788.7 1101.52  4810.3 1093.80  4826.2 1091.94  4831.9 1088.88  4912.6 1077.47
  4950.0 1076.73  4971.6 1071.19  4987.5 1071.88  4993.2 1068.72  5003.7 1067.93
  5018.7 1044.96  5018.9 1044.46  5022.7 1044.96  5025.8 1047.12  5031.8 1046.65
  5052.3 1057.87  5069.9 1073.14  5075.1 1073.05  5093.2 1081.74  5195.5 1085.41
  5262.0 1101.44  5318.3 1123.21  5355.4 1132.53  5461.5 1143.71  5494.4 1145.26
#Mann=3,-1,0
  4707.6    0.12       0  5018.7    0.05       0  5022.7    0.12       0
Bank Sta=5018.7,5022.7
Exp/Cntr=0.3,0.1

Type RM Length L Ch R = 1,82,0,0,0
BEGIN DESCRIPTION:
Stream0180_DS 1.0
END DESCRIPTION:
XS GIS Cut Line= 3
      2116792.04     13867330.91      2117175.08     13867145.34
      2117395.30     13866725.06
#Sta/Elev= 30
  4495.0 1106.10  4585.2 1095.00  4703.7 1087.83  4726.3 1083.02  4777.0 1083.99
  4874.9 1072.50  4931.6 1064.80  4943.6 1061.50  4951.0 1052.48  4956.6 1054.67
  4973.1 1042.47  4978.7 1043.95  4986.7 1038.07  4987.0 1037.57  4990.7 1038.07
  4995.1 1054.94  5000.8 1050.70  5033.6 1067.84  5061.3 1074.33  5077.7 1084.19
  5083.4 1081.80  5099.8 1087.38  5105.4 1081.63  5121.9 1087.65  5127.5 1093.59
  5171.6 1105.28  5188.0 1116.27  5232.2 1131.63  5368.8 1144.55  5395.1 1146.18
#Mann=6,-1,0
  4495.0    0.12       0  4874.9   0.033       0  4931.6    0.12       0
  4986.7    0.05       0  4990.7    0.12       0  5368.8    0.07       0
Bank Sta=4986.7,4990.7
Exp/Cntr=0.3,0.1

Chan Stop Cuts=-1