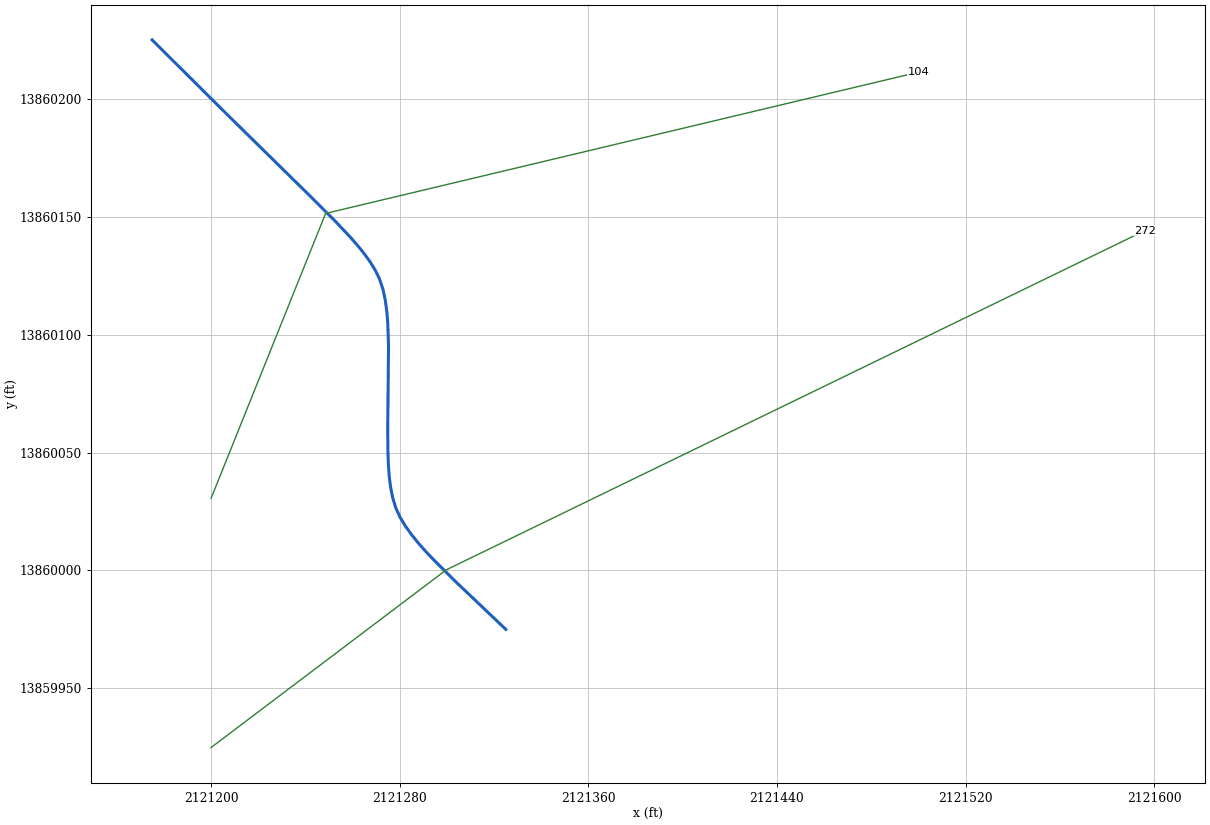
--- Stream0181_DS.prj (project) ---

Proj Title=Stream0181_DS Base Level Engineering
Current Plan=p01
Default Exp/Contr=0.3,0.1
English Units
Geom File=g01
Flow File=f01
Plan File=p01
BEGIN DESCRIPTION:
Stream0181_DS
END DESCRIPTION:

--- Stream0181_DS.p01 (plan) ---

Plan Title=Multiple Run
Short Identifier=Multiple
Geom File=g01
Flow File=f01
Subcritical Flow
K Sum by GR= 0
Std Step Tol= 0.01
Critical Tol= 0.01
Num of Std Step Trials= 20
Max Error Tol= 0.3
Flow Tol Ratio= 0.001
Split Flow NTrial= 30
Split Flow Tol= 0.02
Split Flow Ratio= 0.02
Log Output Level= 0
Friction Slope Method= 1
Unsteady Friction Slope Method= 2
Unsteady Bridges Friction Slope Method= 1
Parabolic Critical Depth
Global Vel Dist=  1 , 1 , 1
Global Log Level= 0
CheckData=True
Encroach Param= -1, 0, 0, 0
BEGIN DESCRIPTION:
Multiple Run
END DESCRIPTION:

--- Stream0181_DS.f01 (steady flow) ---

Flow Title=Multiple
Number of Profiles=7
Profile Names=10-year,25-year,50-year,1pct_min,100-year,1pct_plu,500-year
River Rch & RM= Stream0181_DS,Reach-1,272
    1049    1760    2430    1624    3241    6467    5705
Boundary for River Rch & Prof#=Stream0181_DS,Reach-1,1
Up Type=0
Dn Type=3
Dn Slope=0.005
Boundary for River Rch & Prof#=Stream0181_DS,Reach-1,2
Up Type=0
Dn Type=3
Dn Slope=0.005
Boundary for River Rch & Prof#=Stream0181_DS,Reach-1,3
Up Type=0
Dn Type=3
Dn Slope=0.005
Boundary for River Rch & Prof#=Stream0181_DS,Reach-1,4
Up Type=0
Dn Type=3
Dn Slope=0.005
Boundary for River Rch & Prof#=Stream0181_DS,Reach-1,5
Up Type=0
Dn Type=3
Dn Slope=0.005
Boundary for River Rch & Prof#=Stream0181_DS,Reach-1,6
Up Type=0
Dn Type=3
Dn Slope=0.005
Boundary for River Rch & Prof#=Stream0181_DS,Reach-1,7
Up Type=0
Dn Type=3
Dn Slope=0.005

--- Stream0181_DS.g01 (geometry) ---

Geom Title=Existing Conditions

River Reach=Stream0181_DS,Reach-1
Reach XY= 30
      2121325.00     13859975.00      2121303.63     13859995.33
      2121294.90     13860003.99      2121291.12     13860007.95
      2121287.97     13860011.52      2121285.11     13860015.05
      2121282.50     13860018.68      2121280.22     13860022.45
      2121278.39     13860026.40      2121277.02     13860030.84
      2121276.11     13860035.46      2121275.53     13860040.22
      2121275.19     13860045.08      2121275.01     13860050.00
      2121274.92     13860059.97      2121275.26     13860095.11
      2121274.94     13860104.97      2121274.54     13860109.81
      2121273.90     13860114.55      2121272.92     13860119.14
      2121271.47     13860123.54      2121269.56     13860127.46
      2121267.23     13860131.21      2121264.58     13860134.83
      2121261.70     13860138.35      2121258.65     13860141.80
      2121252.24     13860148.57      2121242.23     13860158.57
      2121208.37     13860191.84      2121175.00     13860225.00

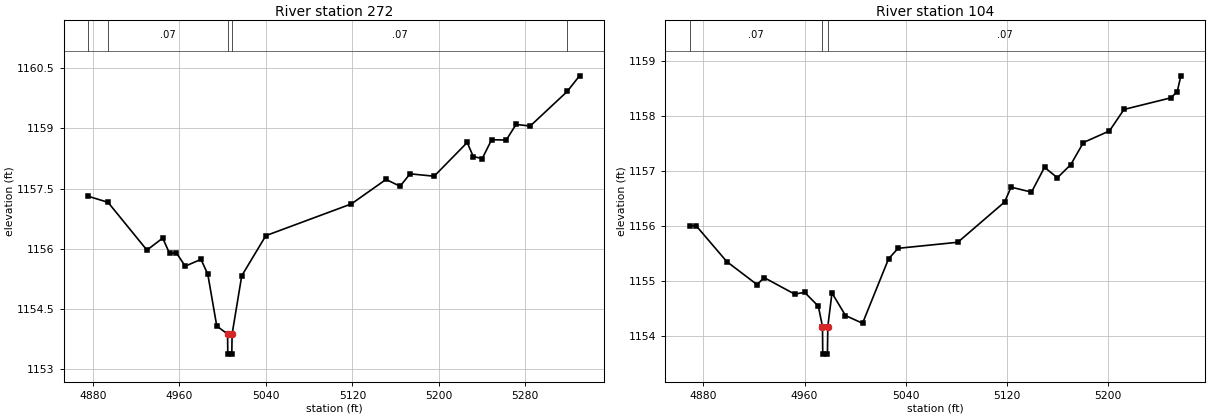
Type RM Length L Ch R = 1,272,168,168,168
BEGIN DESCRIPTION:
Stream0181_DS 2.0
END DESCRIPTION:
XS GIS Cut Line= 3
      2121199.97     13859924.85      2121299.76     13860000.24
      2121596.00     13860144.11
#Sta/Elev= 30
  4875.7 1157.31  4893.9 1157.16  4929.9 1155.97  4944.5 1156.27  4950.8 1155.89
  4957.2 1155.90  4965.3 1155.57  4979.9 1155.74  4986.2 1155.37  4994.5 1154.08
  5004.5 1153.88  5004.7 1153.38  5008.4 1153.38  5008.7 1153.88  5017.6 1155.33
  5039.9 1156.33  5119.0 1157.12  5151.1 1157.73  5164.1 1157.56  5173.3 1157.87
  5195.6 1157.81  5226.2 1158.65  5231.8 1158.30  5240.1 1158.25  5248.8 1158.72
  5262.3 1158.71  5271.4 1159.10  5284.5 1159.06  5318.7 1159.92  5330.1 1160.31
#Mann=5,-1,0
  4875.7   0.035       0  4893.9    0.07       0  5004.5    0.05       0
  5008.7    0.07       0  5318.7    0.12       0
Bank Sta=5004.5,5008.7
Exp/Cntr=0.3,0.1

Type RM Length L Ch R = 1,104,0,0,0
BEGIN DESCRIPTION:
Stream0181_DS 1.0
END DESCRIPTION:
XS GIS Cut Line= 3
      2121200.00     13860030.59      2121248.58     13860151.42
      2121500.00     13860211.33
#Sta/Elev= 30
  4869.1 1156.01  4874.2 1156.01  4898.4 1155.36  4922.5 1154.94  4927.9 1155.07
  4952.1 1154.77  4960.1 1154.80  4970.9 1154.55  4974.2 1154.18  4974.4 1153.68
  4978.1 1153.68  4978.4 1154.18  4981.7 1154.79  4992.4 1154.38  5005.9 1154.24
  5026.5 1155.41  5034.0 1155.60  5081.3 1155.71  5118.3 1156.44  5123.4 1156.71
  5139.6 1156.62  5149.9 1157.07  5160.1 1156.88  5170.7 1157.12  5180.7 1157.52
  5201.3 1157.73  5212.8 1158.12  5249.8 1158.33  5254.9 1158.44  5257.8 1158.73
#Mann=3,-1,0
  4869.1    0.07       0  4974.2    0.05       0  4978.4    0.07       0
Bank Sta=4974.2,4978.4
Exp/Cntr=0.3,0.1

Chan Stop Cuts=-1