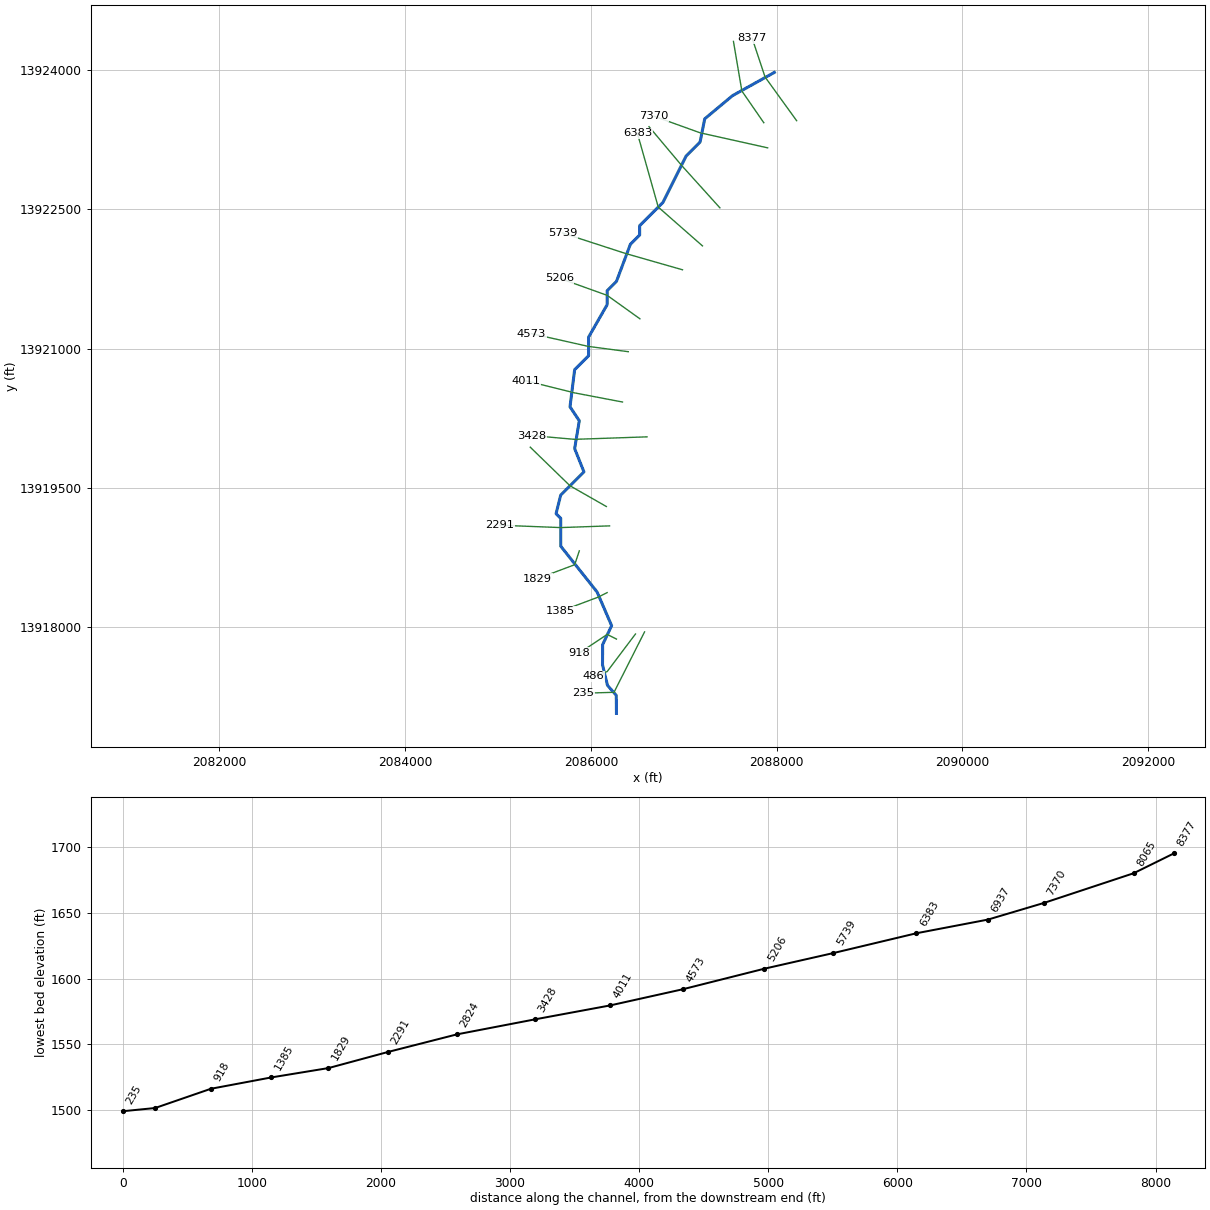
--- Stream0182_DS.prj (project) ---

Proj Title=Stream0182_DS Base Level Engineering
Current Plan=p01
Default Exp/Contr=0.3,0.1
English Units
Geom File=g01
Flow File=f01
Plan File=p01
BEGIN DESCRIPTION:
Stream0182_DS
END DESCRIPTION:

--- Stream0182_DS.p01 (plan) ---

Plan Title=Multiple Run
Short Identifier=Multiple
Geom File=g01
Flow File=f01
Subcritical Flow
K Sum by GR= 0
Std Step Tol= 0.01
Critical Tol= 0.01
Num of Std Step Trials= 20
Max Error Tol= 0.3
Flow Tol Ratio= 0.001
Split Flow NTrial= 30
Split Flow Tol= 0.02
Split Flow Ratio= 0.02
Log Output Level= 0
Friction Slope Method= 1
Unsteady Friction Slope Method= 2
Unsteady Bridges Friction Slope Method= 1
Parabolic Critical Depth
Global Vel Dist=  1 , 1 , 1
Global Log Level= 0
CheckData=True
Encroach Param= -1, 0, 0, 0
BEGIN DESCRIPTION:
Multiple Run
END DESCRIPTION:

--- Stream0182_DS.f01 (steady flow) ---

Flow Title=Multiple
Number of Profiles=7
Profile Names=10-year,25-year,50-year,1pct_min,100-year,1pct_plu,500-year
River Rch & RM= Stream0182_DS,Reach-1,8377
     558     928    1278     858    1712    3416    3036
River Rch & RM= Stream0182_DS,Reach-1,5739
    1551    2742    3926    2729    5445   10864   10382
River Rch & RM= Stream0182_DS,Reach-1,1829
    1571    2772    3964    2751    5489   10951   10432
Boundary for River Rch & Prof#=Stream0182_DS,Reach-1,1
Up Type=0
Dn Type=3
Dn Slope=0.005
Boundary for River Rch & Prof#=Stream0182_DS,Reach-1,2
Up Type=0
Dn Type=3
Dn Slope=0.005
Boundary for River Rch & Prof#=Stream0182_DS,Reach-1,3
Up Type=0
Dn Type=3
Dn Slope=0.005
Boundary for River Rch & Prof#=Stream0182_DS,Reach-1,4
Up Type=0
Dn Type=3
Dn Slope=0.005
Boundary for River Rch & Prof#=Stream0182_DS,Reach-1,5
Up Type=0
Dn Type=3
Dn Slope=0.005
Boundary for River Rch & Prof#=Stream0182_DS,Reach-1,6
Up Type=0
Dn Type=3
Dn Slope=0.005
Boundary for River Rch & Prof#=Stream0182_DS,Reach-1,7
Up Type=0
Dn Type=3
Dn Slope=0.005

--- Stream0182_DS.g01 (geometry) ---

Geom Title=Existing Conditions

River Reach=Stream0182_DS,Reach-1
Reach XY= 30
      2087975.00     13923975.00      2087525.00     13923725.00
      2087225.00     13923475.00      2087175.00     13923225.00
      2087025.00     13923075.00      2086775.00     13922575.00
      2086525.00     13922325.00      2086525.00     13922225.00
      2086425.00     13922125.00      2086275.00     13921725.00
      2086175.00     13921625.00      2086175.00     13921475.00
      2085975.00     13921125.00      2085975.00     13920925.00
      2085825.00     13920775.00      2085775.00     13920375.00
      2085875.00     13920225.00      2085825.00     13919925.00
      2085925.00     13919675.00      2085675.00     13919425.00
      2085625.00     13919225.00      2085675.00     13919175.00
      2085675.00     13918875.00      2086066.84     13918381.05
      2086223.06     13918019.29      2086126.36     13917815.35
      2086124.91     13917597.69      2086178.56     13917376.47
      2086272.94     13917269.15      2086275.00     13917075.00

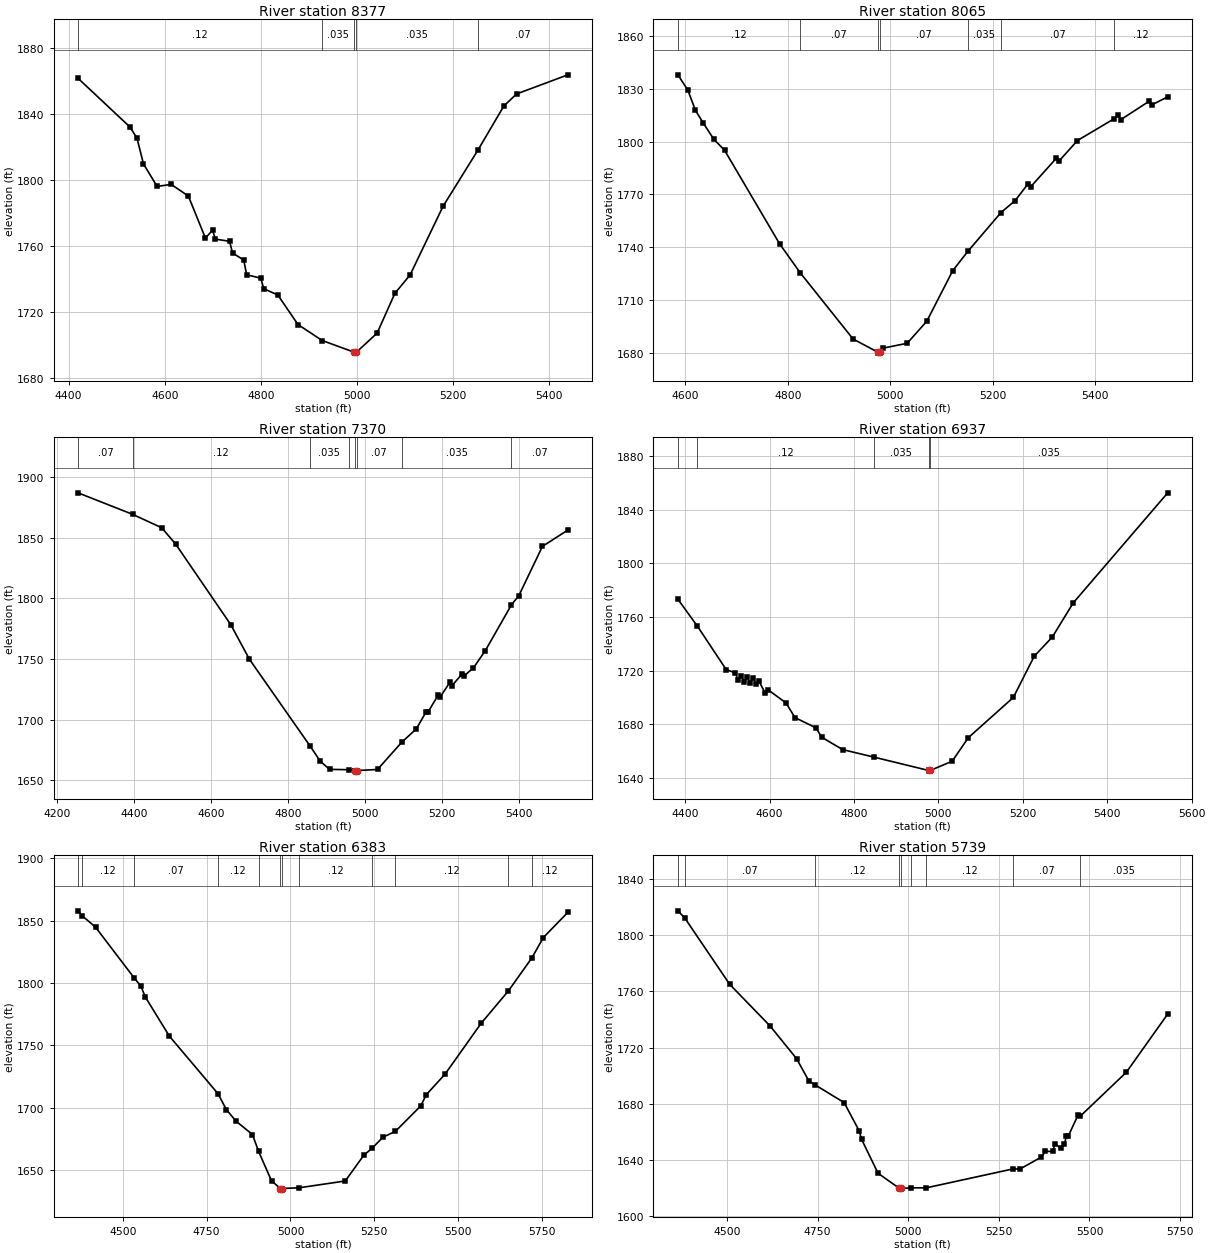
Type RM Length L Ch R = 1,8377,312,312,312
BEGIN DESCRIPTION:
Stream0182_DS 17.0
END DESCRIPTION:
XS GIS Cut Line= 3
      2088214.94     13923454.57      2087875.00     13923925.00
      2087736.35     13924341.74
#Sta/Elev= 30
  4419.6 1861.76  4527.7 1832.26  4542.4 1825.43  4555.8 1809.91  4584.2 1796.27
  4613.6 1797.48  4649.2 1790.47  4684.8 1764.94  4699.5 1769.79  4705.6 1764.33
  4735.0 1763.05  4741.2 1755.93  4764.5 1751.68  4770.6 1742.75  4800.0 1740.70
  4806.2 1734.32  4835.6 1730.46  4877.4 1712.61  4927.9 1702.91  4994.9 1695.78
  4995.2 1695.28  4998.9 1695.78  5042.2 1707.43  5079.1 1731.47  5110.8 1742.66
  5179.3 1784.17  5252.6 1818.56  5305.9 1844.95  5332.3 1852.26  5439.2 1863.87
#Mann=5,-1,0
  4419.6    0.12       0  4927.9   0.035       0  4994.9   0.035       0
  4998.9   0.035       0  5252.6    0.07       0
Bank Sta=4994.9,4998.9
Exp/Cntr=0.3,0.1

Type RM Length L Ch R = 1,8065,695,695,695
BEGIN DESCRIPTION:
Stream0182_DS 16.0
END DESCRIPTION:
XS GIS Cut Line= 3
      2087860.78     13923433.72      2087625.00     13923775.00
      2087534.41     13924308.67
#Sta/Elev= 30
  4585.2 1837.76  4604.6 1829.10  4619.4 1817.69  4634.3 1810.62  4655.3 1801.28
  4676.2 1795.07  4783.7 1742.06  4824.3 1725.52  4927.1 1688.16  4975.7 1680.66
  4975.9 1680.16  4979.7 1680.66  4986.5 1683.03  5032.7 1685.73  5071.0 1698.22
  5121.7 1726.88  5151.0 1737.74  5215.8 1759.76  5243.4 1766.53  5268.8 1776.08
  5273.9 1774.37  5324.1 1790.62  5329.1 1788.93  5365.1 1800.56  5436.5 1812.86
  5444.7 1814.81  5449.8 1812.40  5505.0 1822.78  5510.1 1820.74  5541.3 1825.29
#Mann=7,-1,0
  4585.2    0.12       0  4824.3    0.07       0  4975.7    0.05       0
  4979.7    0.07       0  5151.0   0.035       0  5215.8    0.07       0
  5436.5    0.12       0
Bank Sta=4975.7,4979.7
Exp/Cntr=0.3,0.1

Type RM Length L Ch R = 1,7370,433,433,433
BEGIN DESCRIPTION:
Stream0182_DS 15.0
END DESCRIPTION:
XS GIS Cut Line= 3
      2087902.45     13923162.87      2087175.00     13923325.00
      2086680.20     13923503.16
#Sta/Elev= 30
  4254.7 1887.07  4396.3 1869.34  4471.9 1858.25  4508.2 1844.72  4650.9 1778.44
  4699.5 1749.80  4856.0 1678.67  4883.6 1665.59  4907.8 1658.99  4957.7 1658.71
  4973.7 1658.04  4974.0 1657.54  4977.7 1658.04  5031.9 1658.90  5094.4 1681.23
  5132.8 1692.43  5158.2 1706.54  5163.5 1706.51  5188.9 1720.04  5194.2 1718.56
  5219.6 1730.72  5224.9 1727.92  5250.3 1737.25  5255.7 1735.88  5281.0 1742.76
  5311.7 1756.91  5379.5 1794.71  5398.5 1802.16  5459.9 1842.90  5525.9 1856.37
#Mann=8,-1,0
  4254.7    0.07       0  4396.3    0.12       0  4856.0   0.035       0
  4957.7    0.07       0  4973.7    0.05       0  4977.7    0.07       0
  5094.4   0.035       0  5379.5    0.07       0
Bank Sta=4973.7,4977.7
Exp/Cntr=0.3,0.1

Type RM Length L Ch R = 1,6937,554,554,554
BEGIN DESCRIPTION:
Stream0182_DS 14.0
END DESCRIPTION:
XS GIS Cut Line= 3
      2087388.59     13922517.01      2086975.00     13922975.00
      2086625.55     13923391.00
#Sta/Elev= 30
  4382.9 1773.19  4429.2 1753.08  4497.4 1720.64  4518.4 1718.32  4525.8 1712.95
  4532.6 1715.95  4540.0 1711.72  4546.8 1714.98  4554.2 1710.62  4561.0 1714.43
  4568.4 1710.05  4575.2 1711.99  4589.4 1703.19  4596.1 1705.69  4638.7 1695.90
  4660.3 1684.85  4709.7 1677.24  4723.9 1670.10  4773.2 1660.96  4847.0 1655.36
  4976.7 1645.38  4977.0 1644.88  4980.7 1645.38  5032.7 1652.30  5070.9 1669.84
  5177.6 1699.92  5227.0 1730.66  5269.9 1745.00  5319.3 1770.43  5543.3 1852.67
#Mann=5,-1,0
  4382.9    0.07       0  4429.2    0.12       0  4847.0   0.035       0
  4976.7   0.035       0  4980.7   0.035       0
Bank Sta=4976.7,4980.7
Exp/Cntr=0.3,0.1

Type RM Length L Ch R = 1,6383,644,644,644
BEGIN DESCRIPTION:
Stream0182_DS 13.0
END DESCRIPTION:
XS GIS Cut Line= 3
      2087201.05     13922107.33      2086725.00     13922525.00
      2086500.20     13923320.76
#Sta/Elev= 30
  4366.7 1857.92  4378.1 1854.15  4418.8 1844.83  4534.2 1803.99  4553.5 1797.68
  4567.8 1788.51  4638.9 1757.34  4783.9 1711.10  4808.8 1698.38  4837.3 1689.15
  4886.6 1678.32  4904.9 1664.81  4943.5 1641.13  4970.0 1634.97  4970.2 1634.47
  4974.0 1634.97  5026.5 1635.58  5163.3 1641.00  5218.2 1661.55  5244.3 1667.57
  5275.6 1676.14  5312.7 1680.84  5388.0 1701.17  5405.3 1710.40  5461.1 1726.90
  5568.2 1767.56  5649.6 1793.61  5719.8 1820.20  5753.7 1836.44  5826.9 1856.71
#Mann=12,-1,0
  4366.7    0.07       0  4378.1    0.12       0  4534.2    0.07       0
  4783.9    0.12       0  4904.9   0.035       0  4970.0   0.035       0
  4974.0   0.035       0  5026.5    0.12       0  5244.3   0.035       0
  5312.7    0.12       0  5649.6   0.035       0  5719.8    0.12       0
Bank Sta=4970,4974
Exp/Cntr=0.3,0.1

Type RM Length L Ch R = 1,5739,533,533,533
BEGIN DESCRIPTION:
Stream0182_DS 12.0
END DESCRIPTION:
XS GIS Cut Line= 3
      2086985.82     13921850.36      2086375.00     13922025.00
      2085694.13     13922246.20
#Sta/Elev= 30
  4364.7 1817.31  4383.4 1812.30  4507.4 1765.08  4619.2 1735.35  4692.0 1712.19
  4725.8 1696.41  4743.7 1693.43  4823.2 1680.94  4864.8 1660.82  4871.3 1654.84
  4916.8 1630.66  4975.9 1619.87  4976.2 1619.37  4979.9 1619.87  5006.4 1620.26
  5050.3 1620.31  5288.4 1633.71  5308.8 1633.72  5367.5 1642.19  5378.5 1646.25
  5399.4 1646.19  5404.7 1651.77  5420.6 1648.41  5431.1 1651.44  5436.6 1657.51
  5441.9 1657.25  5468.6 1672.15  5474.3 1671.16  5601.7 1702.49  5715.9 1743.91
#Mann=9,-1,0
  4364.7    0.12       0  4383.4    0.07       0  4743.7    0.12       0
  4975.9    0.05       0  4979.9    0.12       0  5006.4    0.07       0
  5050.3    0.12       0  5288.4    0.07       0  5474.3   0.035       0
Bank Sta=4975.9,4979.9
Exp/Cntr=0.3,0.1

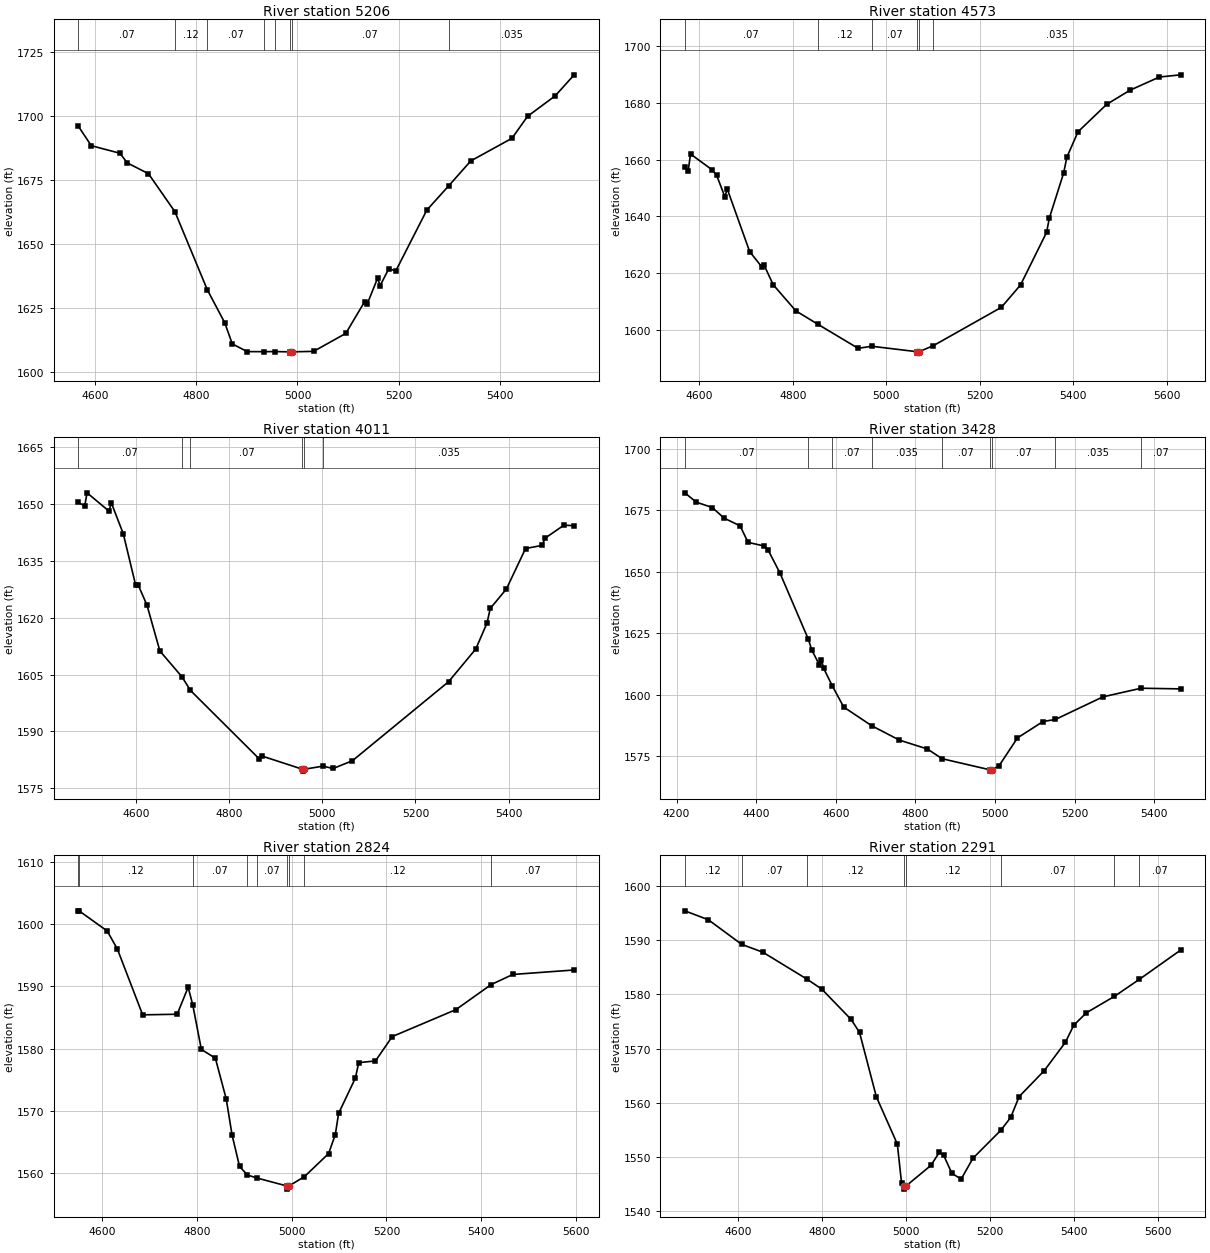
Type RM Length L Ch R = 1,5206,633,633,633
BEGIN DESCRIPTION:
Stream0182_DS 10.0
END DESCRIPTION:
XS GIS Cut Line= 3
      2086527.44     13921322.60      2086175.00     13921575.00
      2085659.79     13921759.95
#Sta/Elev= 30
  4566.5 1696.13  4592.2 1688.53  4648.7 1685.59  4663.4 1681.81  4705.2 1677.60
  4757.6 1662.73  4821.6 1632.26  4856.3 1619.30  4871.0 1611.12  4900.5 1608.08
  4933.9 1608.06  4956.1 1608.09  4984.5 1607.99  4984.7 1607.49  4988.5 1607.99
  5031.9 1608.18  5095.6 1615.19  5133.0 1627.63  5138.3 1626.83  5158.4 1636.71
  5163.7 1633.91  5180.6 1640.42  5194.5 1639.61  5255.9 1663.36  5299.7 1672.96
  5342.8 1682.57  5424.4 1691.43  5455.2 1700.00  5510.0 1708.03  5547.4 1716.22
#Mann=8,-1,0
  4566.5    0.07       0  4757.6    0.12       0  4821.6    0.07       0
  4933.9   0.035       0  4956.1    0.07       0  4984.5    0.05       0
  4988.5    0.07       0  5299.7   0.035       0
Bank Sta=4984.5,4988.5
Exp/Cntr=0.3,0.1

Type RM Length L Ch R = 1,4573,562,562,562
BEGIN DESCRIPTION:
Stream0182_DS 9.0
END DESCRIPTION:
XS GIS Cut Line= 3
      2086402.47     13920968.42      2085975.00     13921025.00
      2085360.78     13921162.87
#Sta/Elev= 30
  4568.8 1657.21  4576.1 1656.12  4581.1 1661.92  4626.8 1656.42  4636.9 1654.44
  4654.5 1646.87  4659.6 1649.63  4707.5 1627.59  4733.0 1622.28  4738.0 1622.96
  4757.9 1615.90  4806.4 1606.69  4852.9 1602.03  4939.5 1593.51  4969.0 1594.22
  5065.6 1592.31  5065.8 1591.81  5069.6 1592.31  5100.7 1594.45  5246.0 1607.94
  5287.0 1615.81  5342.9 1634.39  5348.5 1639.29  5379.2 1655.22  5386.2 1660.83
  5410.0 1669.76  5471.4 1679.43  5521.3 1684.41  5584.2 1689.05  5629.5 1689.82
#Mann=6,-1,0
  4568.8    0.07       0  4852.9    0.12       0  4969.0    0.07       0
  5065.6    0.05       0  5069.6    0.07       0  5100.7   0.035       0
Bank Sta=5065.6,5069.6
Exp/Cntr=0.3,0.1

Type RM Length L Ch R = 1,4011,583,583,583
BEGIN DESCRIPTION:
Stream0182_DS 8.0
END DESCRIPTION:
XS GIS Cut Line= 3
      2086339.91     13920426.77      2085825.00     13920525.00
      2085299.98     13920655.51
#Sta/Elev= 30
  4475.8 1650.42  4489.5 1649.53  4494.6 1652.97  4541.6 1648.14  4546.7 1650.32
  4572.4 1642.15  4598.8 1628.66  4603.9 1628.77  4623.3 1623.31  4651.0 1611.22
  4698.3 1604.43  4716.6 1600.82  4864.6 1582.72  4869.7 1583.52  4957.3 1580.01
  4957.5 1579.51  4961.3 1580.01  5001.1 1580.82  5023.2 1580.21  5064.6 1582.25
  5271.3 1603.12  5329.7 1611.76  5353.9 1618.64  5360.7 1622.44  5395.3 1627.56
  5436.6 1638.27  5472.8 1639.11  5477.9 1640.95  5519.3 1644.45  5541.0 1644.27
#Mann=6,-1,0
  4475.8    0.07       0  4698.3    0.12       0  4716.6    0.07       0
  4957.3    0.05       0  4961.3    0.07       0  5001.1   0.035       0
Bank Sta=4957.3,4961.3
Exp/Cntr=0.3,0.1

Type RM Length L Ch R = 1,3428,604,604,604
BEGIN DESCRIPTION:
Stream0182_DS 7.0
END DESCRIPTION:
XS GIS Cut Line= 3
      2086603.84     13920051.76      2085825.00     13920025.00
      2085360.78     13920065.65
#Sta/Elev= 30
  4220.7 1682.01  4249.6 1678.21  4289.6 1676.04  4319.6 1671.71  4359.6 1668.58
  4379.6 1661.86  4419.7 1660.41  4429.7 1658.83  4459.7 1649.41  4530.8 1622.57
  4539.7 1618.10  4558.9 1612.01  4563.9 1613.94  4569.7 1610.60  4591.5 1603.42
  4619.8 1594.93  4690.0 1587.34  4759.9 1581.47  4829.9 1577.89  4867.0 1573.92
  4988.0 1569.38  4988.2 1568.88  4992.0 1569.38  5010.0 1571.06  5056.3 1582.39
  5120.5 1589.05  5151.4 1589.88  5271.0 1599.08  5366.8 1602.58  5466.0 1602.31
#Mann=9,-1,0
  4220.7    0.07       0  4530.8   0.035       0  4591.5    0.07       0
  4690.0   0.035       0  4867.0    0.07       0  4988.0    0.05       0
  4992.0    0.07       0  5151.4   0.035       0  5366.8    0.07       0
Bank Sta=4988,4992
Exp/Cntr=0.3,0.1

Type RM Length L Ch R = 1,2824,533,533,533
BEGIN DESCRIPTION:
Stream0182_DS 6.0
END DESCRIPTION:
XS GIS Cut Line= 3
      2086166.31     13919301.78      2085775.00     13919525.00
      2085347.25     13919940.31
#Sta/Elev= 30
  4549.5 1602.11  4551.0 1602.11  4610.4 1598.88  4632.0 1595.96  4685.3 1585.42
  4758.2 1585.52  4781.3 1589.85  4790.9 1587.08  4809.2 1579.87  4838.8 1578.47
  4861.8 1571.89  4874.0 1566.16  4889.8 1561.10  4906.5 1559.72  4927.7 1559.22
  4990.1 1557.96  4990.3 1557.46  4994.1 1557.96  5026.9 1559.47  5077.8 1563.16
  5092.0 1566.22  5098.9 1569.60  5134.4 1575.29  5141.4 1577.75  5176.8 1578.03
  5212.1 1581.93  5346.6 1586.26  5421.0 1590.28  5466.7 1591.90  5596.2 1592.62
#Mann=9,-1,0
  4549.5    0.07       0  4551.0    0.12       0  4790.9    0.07       0
  4906.5   0.035       0  4927.7    0.07       0  4990.1    0.05       0
  4994.1    0.07       0  5026.9    0.12       0  5421.0    0.07       0
Bank Sta=4990.1,4994.1
Exp/Cntr=0.3,0.1

Type RM Length L Ch R = 1,2291,462,462,462
BEGIN DESCRIPTION:
Stream0182_DS 5.0
END DESCRIPTION:
XS GIS Cut Line= 3
      2086201.08     13919093.43      2085675.00     13919075.00
      2085020.49     13919100.37
#Sta/Elev= 30
  4473.6 1595.40  4529.7 1593.75  4609.3 1589.21  4659.8 1587.76  4764.7 1582.80
  4799.9 1580.97  4869.9 1575.37  4889.9 1572.98  4930.0 1561.11  4980.0 1552.39
  4990.0 1545.28  4995.5 1544.58  4995.7 1544.08  4999.5 1544.58  5060.0 1548.45
  5080.1 1550.88  5090.1 1550.37  5110.1 1546.98  5132.1 1545.93  5160.1 1549.77
  5226.6 1554.93  5250.2 1557.31  5270.2 1561.14  5330.2 1565.94  5380.3 1571.14
  5400.3 1574.29  5430.3 1576.59  5497.3 1579.63  5556.2 1582.74  5655.0 1588.16
#Mann=8,-1,0
  4473.6    0.12       0  4609.3    0.07       0  4764.7    0.12       0
  4995.5    0.05       0  4999.5    0.12       0  5226.6    0.07       0
  5497.3    0.12       0  5556.2    0.07       0
Bank Sta=4995.5,4999.5
Exp/Cntr=0.3,0.1

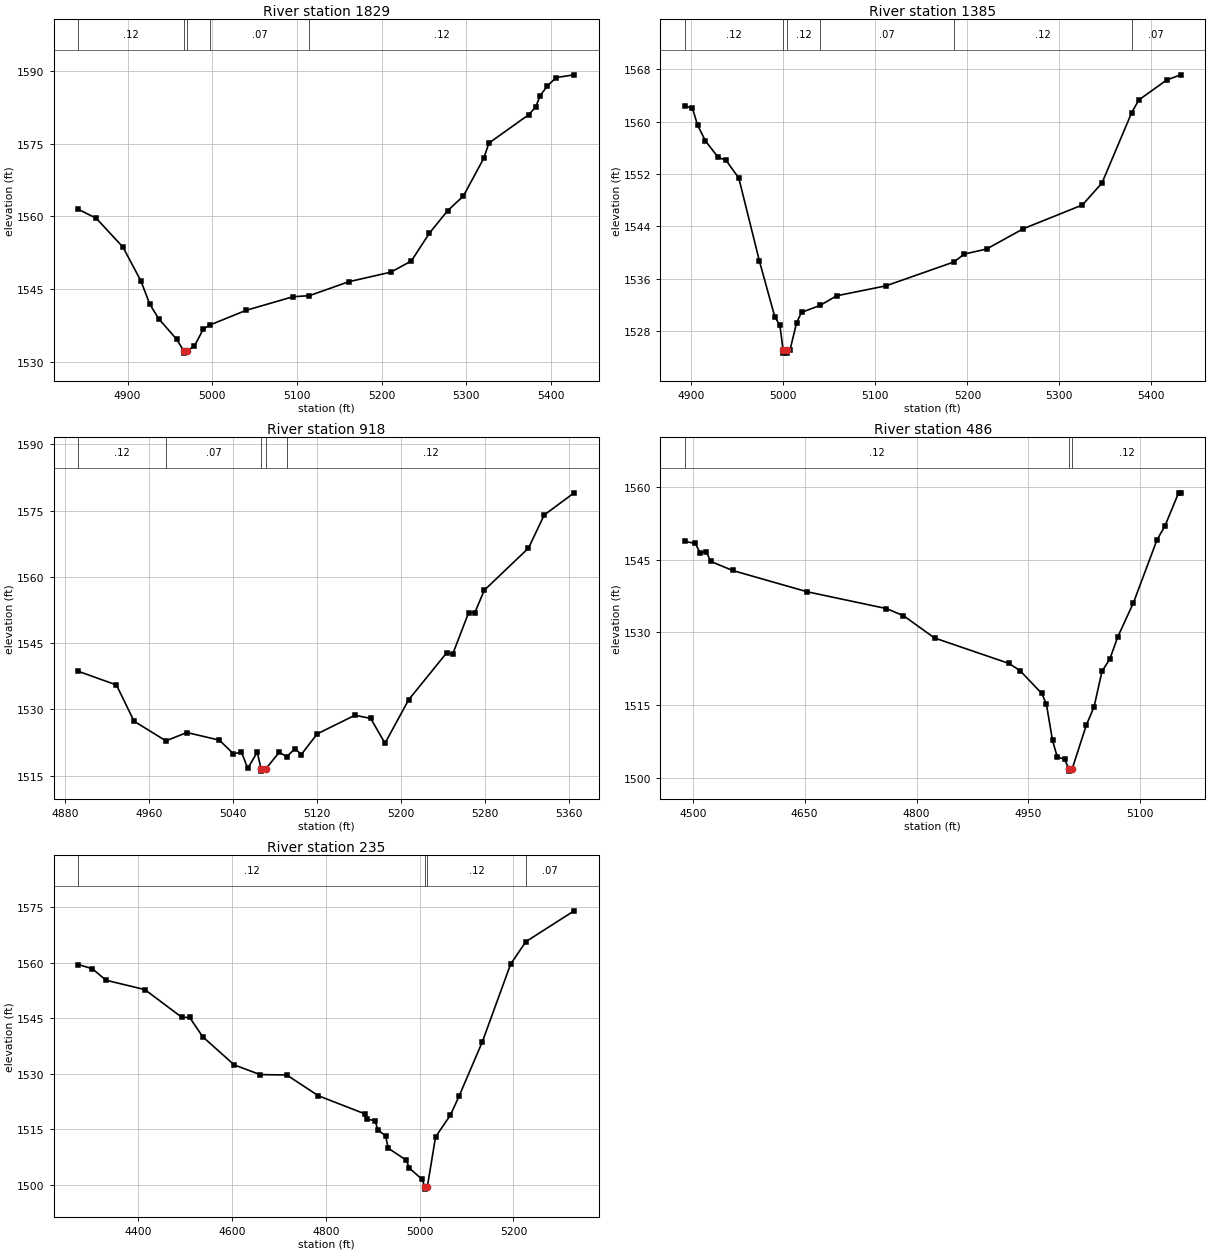
Type RM Length L Ch R = 1,1829,444,444,444
BEGIN DESCRIPTION:
Stream0182_DS 4.0
END DESCRIPTION:
XS GIS Cut Line= 3
      2085875.00     13918825.00      2085825.00     13918675.00
      2085425.02     13918525.01
#Sta/Elev= 30
  4841.9 1561.45  4863.0 1559.62  4894.6 1553.66  4915.7 1546.70  4926.2 1541.91
  4936.8 1538.88  4957.9 1534.66  4966.2 1532.29  4966.5 1531.79  4970.6 1532.29
  4978.9 1533.24  4989.5 1536.77  4997.8 1537.64  5040.1 1540.63  5095.2 1543.42
  5114.7 1543.65  5161.1 1546.52  5210.9 1548.50  5235.0 1550.80  5256.3 1556.53
  5277.7 1561.15  5296.4 1564.20  5320.4 1571.96  5326.6 1575.13  5373.8 1581.01
  5381.8 1582.59  5387.2 1584.93  5395.2 1586.85  5405.9 1588.65  5427.2 1589.21
#Mann=5,-1,0
  4841.9    0.12       0  4966.2    0.05       0  4970.6    0.12       0
  4997.8    0.07       0  5114.7    0.12       0
Bank Sta=4966.2,4970.6
Exp/Cntr=0.3,0.1

Type RM Length L Ch R = 1,1385,467,467,467
BEGIN DESCRIPTION:
Stream0182_DS 3.0
END DESCRIPTION:
XS GIS Cut Line= 3
      2086174.97     13918374.98      2086075.00     13918325.00
      2085674.97     13918174.99
#Sta/Elev= 30
  4892.8 1562.38  4901.1 1562.02  4906.7 1559.46  4915.1 1557.07  4929.1 1554.52
  4937.5 1554.10  4951.5 1551.37  4973.8 1538.76  4990.6 1530.20  4996.2 1528.87
  4999.6 1525.14  4999.9 1524.64  5003.7 1524.64  5004.0 1525.14  5007.2 1525.14
  5014.4 1529.31  5019.7 1530.86  5039.8 1531.92  5058.0 1533.40  5111.4 1534.91
  5185.2 1538.55  5196.8 1539.77  5220.8 1540.53  5260.9 1543.64  5325.0 1547.26
  5346.3 1550.61  5378.6 1561.36  5386.4 1563.30  5416.6 1566.33  5431.8 1567.13
#Mann=6,-1,0
  4892.8    0.12       0  4999.6    0.05       0  5004.0    0.12       0
  5039.8    0.07       0  5185.2    0.12       0  5378.6    0.07       0
Bank Sta=4999.6,5004
Exp/Cntr=0.3,0.1

Type RM Length L Ch R = 1,918,432,432,432
BEGIN DESCRIPTION:
Stream0182_DS 2.0
END DESCRIPTION:
XS GIS Cut Line= 3
      2086274.99     13917875.01      2086175.00     13917925.00
      2085875.04     13917725.03
#Sta/Elev= 30
  4892.8 1538.62  4929.1 1535.53  4945.9 1527.32  4976.2 1522.88  4996.2 1524.76
  5027.1 1523.04  5040.6 1519.94  5048.2 1520.32  5054.2 1516.64  5063.2 1520.30
  5066.9 1516.52  5067.2 1516.02  5071.4 1516.52  5084.2 1520.31  5091.2 1519.29
  5099.2 1521.10  5105.2 1519.78  5120.3 1524.45  5156.3 1528.68  5171.3 1527.95
  5184.9 1522.33  5207.4 1532.16  5243.5 1542.76  5249.5 1542.58  5264.5 1551.85
  5270.5 1551.92  5279.5 1556.98  5321.6 1566.53  5336.6 1574.03  5365.1 1579.04
#Mann=5,-1,0
  4892.8    0.12       0  4976.2    0.07       0  5066.9    0.05       0
  5071.4    0.07       0  5091.2    0.12       0
Bank Sta=5066.9,5071.4
Exp/Cntr=0.3,0.1

Type RM Length L Ch R = 1,486,251,251,251
BEGIN DESCRIPTION:
Stream0182_DS 1.0
END DESCRIPTION:
XS GIS Cut Line= 3
      2086479.73     13917929.53      2086175.00     13917525.00
      2086024.98     13917474.99
#Sta/Elev= 30
  4489.4 1548.83  4503.5 1548.39  4509.7 1546.50  4518.0 1546.69  4524.3 1544.68
  4553.4 1542.81  4653.4 1538.41  4759.6 1534.94  4782.4 1533.48  4824.1 1528.87
  4924.0 1523.60  4938.6 1522.14  4967.8 1517.42  4974.0 1515.26  4982.3 1507.69
  4988.6 1504.33  4998.5 1503.80  5004.1 1501.86  5004.5 1501.36  5008.7 1501.86
  5027.5 1510.82  5038.0 1514.66  5048.6 1521.98  5059.1 1524.51  5069.7 1529.08
  5090.7 1536.12  5122.4 1549.16  5132.9 1551.97  5151.3 1558.85  5154.0 1558.85
#Mann=3,-1,0
  4489.4    0.12       0  5004.1    0.05       0  5008.7    0.12       0
Bank Sta=5004.1,5008.7
Exp/Cntr=0.3,0.1

Type RM Length L Ch R = 1,235,0,0,0
BEGIN DESCRIPTION:
Stream0182_DS 0.0
END DESCRIPTION:
XS GIS Cut Line= 3
      2086577.18     13917951.67      2086248.77     13917301.85
      2085919.51     13917292.06
#Sta/Elev= 30
  4271.9 1559.46  4301.8 1558.31  4331.0 1555.22  4413.8 1552.69  4492.6 1545.23
  4509.3 1545.19  4537.2 1539.98  4604.3 1532.40  4659.7 1529.78  4716.4 1529.69
  4783.6 1524.09  4882.6 1519.22  4888.2 1517.75  4904.9 1517.36  4910.5 1514.90
  4927.2 1513.26  4932.8 1509.94  4971.8 1506.67  4977.4 1504.62  5004.4 1501.62
  5011.5 1499.41  5011.8 1498.91  5016.1 1499.41  5033.8 1512.99  5065.5 1518.88
  5083.8 1523.93  5133.8 1538.69  5193.9 1559.56  5226.5 1565.63  5329.4 1573.93
#Mann=4,-1,0
  4271.9    0.12       0  5011.5    0.05       0  5016.1    0.12       0
  5226.5    0.07       0
Bank Sta=5011.5,5016.1
Exp/Cntr=0.3,0.1

Chan Stop Cuts=-1