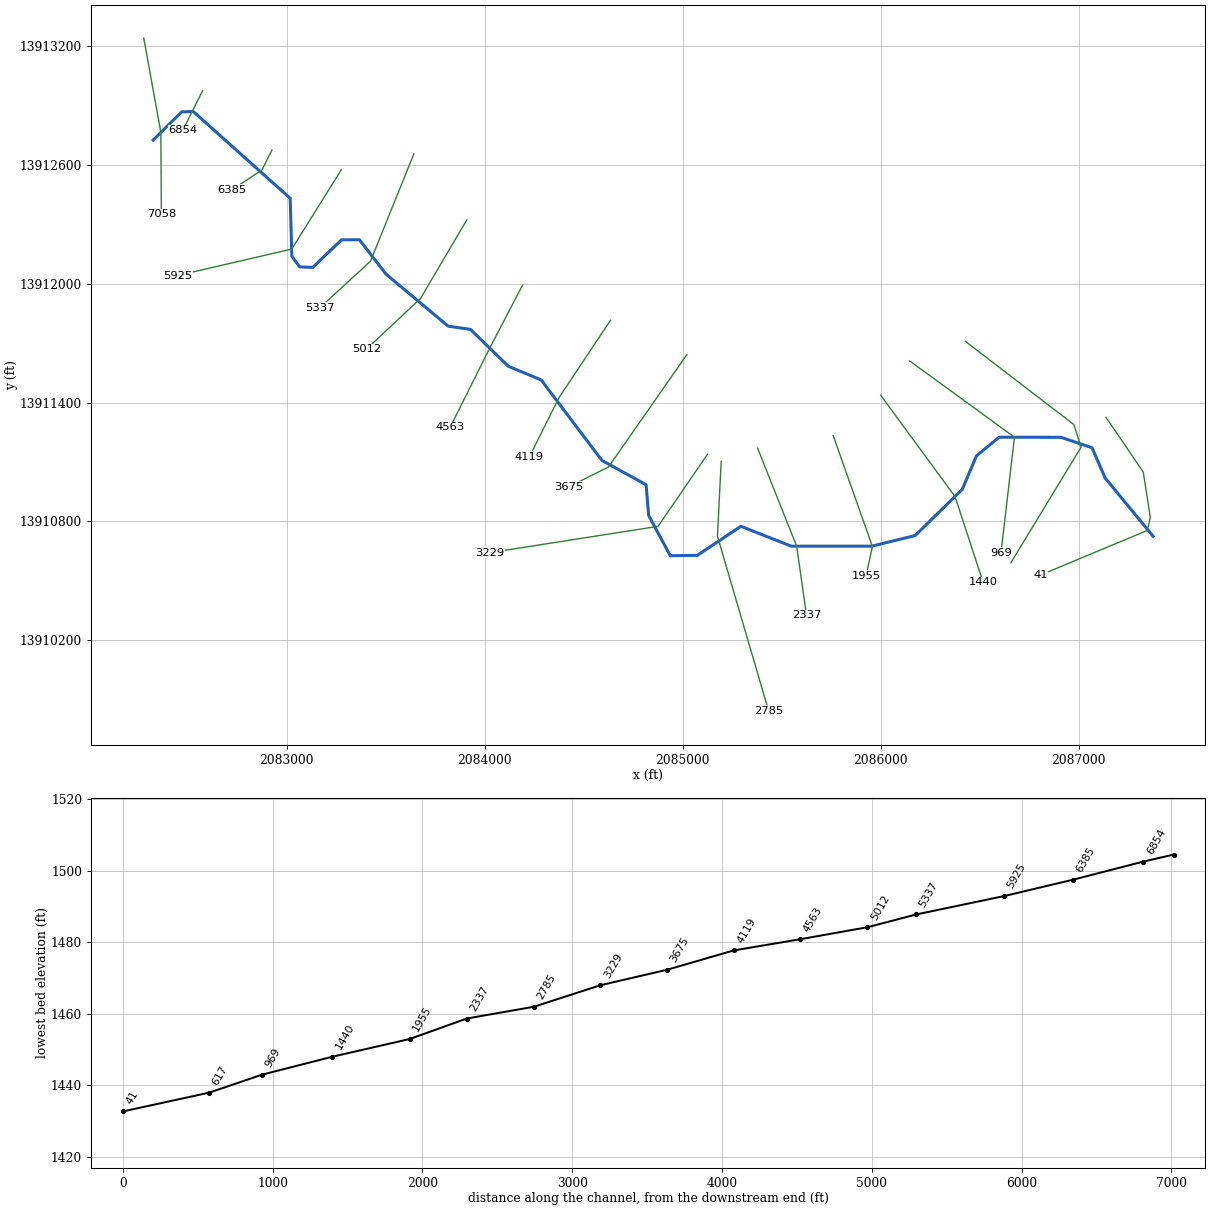
--- Stream0183_DS.prj (project) ---

Proj Title=Stream0183_DS Base Level Engineering
Current Plan=p01
Default Exp/Contr=0.3,0.1
English Units
Geom File=g01
Flow File=f01
Plan File=p01
BEGIN DESCRIPTION:
Stream0183_DS
END DESCRIPTION:

--- Stream0183_DS.p01 (plan) ---

Plan Title=Multiple Run
Short Identifier=Multiple
Geom File=g01
Flow File=f01
Subcritical Flow
K Sum by GR= 0
Std Step Tol= 0.01
Critical Tol= 0.01
Num of Std Step Trials= 20
Max Error Tol= 0.3
Flow Tol Ratio= 0.001
Split Flow NTrial= 30
Split Flow Tol= 0.02
Split Flow Ratio= 0.02
Log Output Level= 0
Friction Slope Method= 1
Unsteady Friction Slope Method= 2
Unsteady Bridges Friction Slope Method= 1
Parabolic Critical Depth
Global Vel Dist=  1 , 1 , 1
Global Log Level= 0
CheckData=True
Encroach Param= -1, 0, 0, 0
BEGIN DESCRIPTION:
Multiple Run
END DESCRIPTION:

--- Stream0183_DS.f01 (steady flow) ---

Flow Title=Multiple
Number of Profiles=7
Profile Names=10-year,25-year,50-year,1pct_min,100-year,1pct_plu,500-year
River Rch & RM= Stream0183_DS,Reach-1,7058
    2130    3775    5409    3749    7481   14927   14171
Boundary for River Rch & Prof#=Stream0183_DS,Reach-1,1
Up Type=0
Dn Type=3
Dn Slope=0.005
Boundary for River Rch & Prof#=Stream0183_DS,Reach-1,2
Up Type=0
Dn Type=3
Dn Slope=0.005
Boundary for River Rch & Prof#=Stream0183_DS,Reach-1,3
Up Type=0
Dn Type=3
Dn Slope=0.005
Boundary for River Rch & Prof#=Stream0183_DS,Reach-1,4
Up Type=0
Dn Type=3
Dn Slope=0.005
Boundary for River Rch & Prof#=Stream0183_DS,Reach-1,5
Up Type=0
Dn Type=3
Dn Slope=0.005
Boundary for River Rch & Prof#=Stream0183_DS,Reach-1,6
Up Type=0
Dn Type=3
Dn Slope=0.005
Boundary for River Rch & Prof#=Stream0183_DS,Reach-1,7
Up Type=0
Dn Type=3
Dn Slope=0.005

--- Stream0183_DS.g01 (geometry) ---

Geom Title=Existing Conditions

River Reach=Stream0183_DS,Reach-1
Reach XY= 30
      2082325.00     13912725.00      2082468.95     13912867.55
      2082527.29     13912869.94      2083017.19     13912431.19
      2083025.48     13912138.69      2083064.95     13912085.02
      2083131.03     13912082.45      2083276.57     13912221.57
      2083366.95     13912221.86      2083501.53     13912048.01
      2083815.21     13911785.52      2083927.43     13911769.48
      2084118.94     13911583.14      2084284.68     13911514.24
      2084591.42     13911107.92      2084814.65     13910985.12
      2084827.36     13910830.52      2084936.81     13910626.60
      2085073.52     13910628.54      2085293.43     13910775.19
      2085547.69     13910674.90      2085954.97     13910675.07
      2086173.53     13910728.54      2086411.38     13910961.79
      2086483.13     13911131.07      2086597.64     13911225.20
      2086909.79     13911224.48      2087066.68     13911171.85
      2087133.14     13911018.95      2087375.00     13910725.00

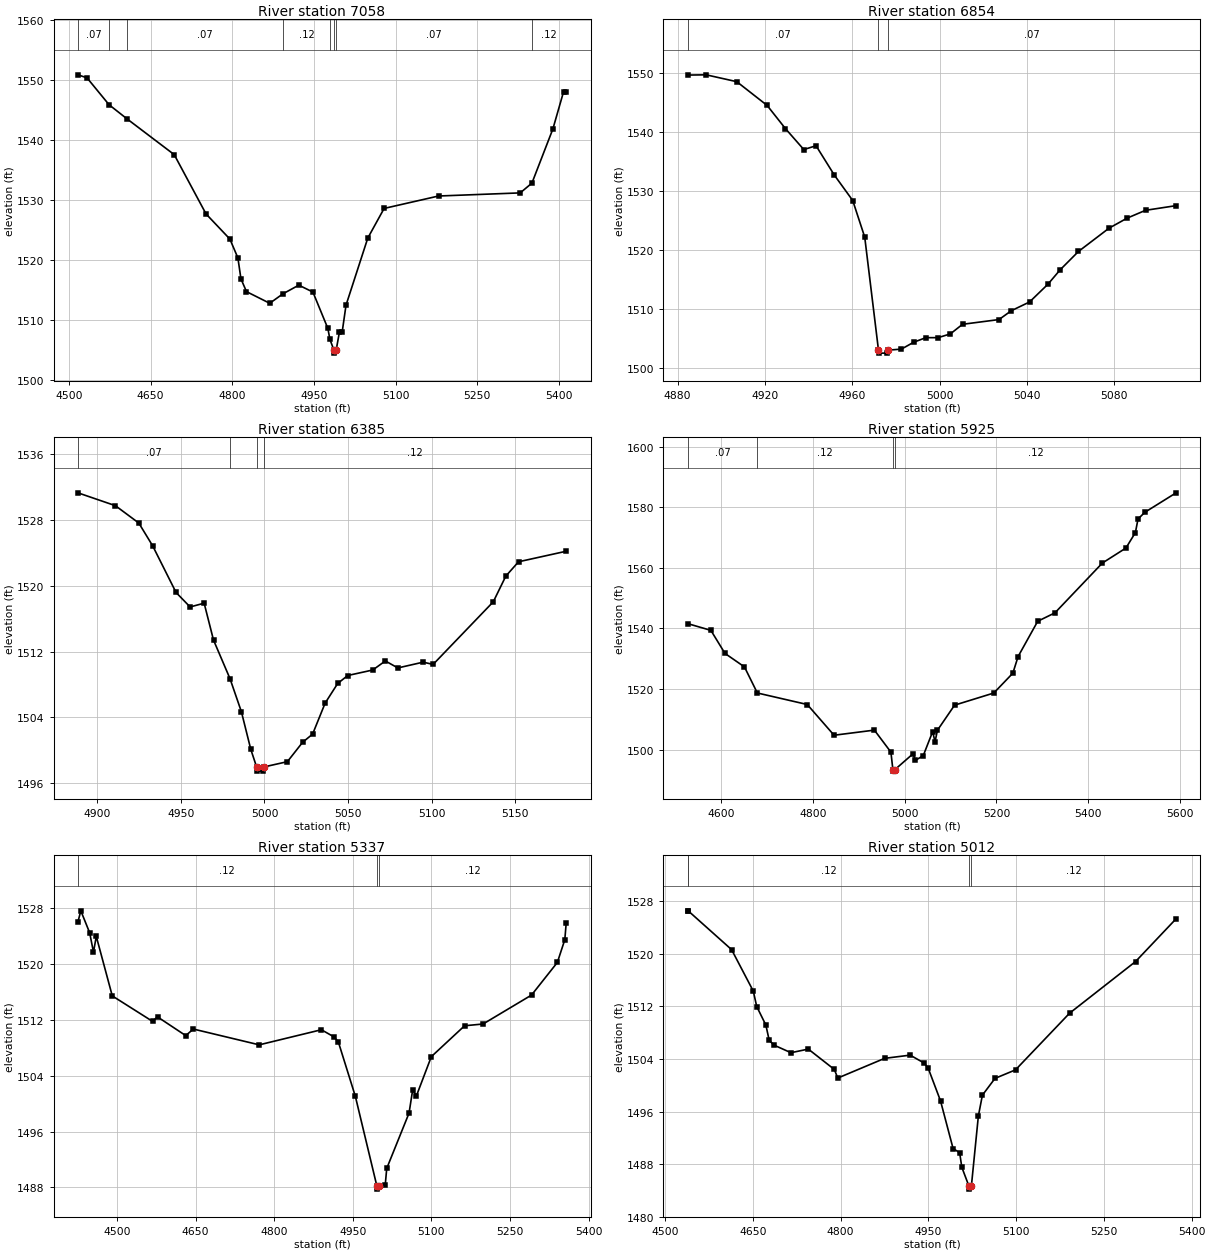
Type RM Length L Ch R = 1,7058,204,204,204
BEGIN DESCRIPTION:
Stream0183_DS 16.0
END DESCRIPTION:
XS GIS Cut Line= 3
      2082277.65     13913239.64      2082363.94     13912764.00
      2082366.53     13912350.61
#Sta/Elev= 30
  4516.6 1550.90  4533.2 1550.40  4573.8 1545.91  4606.0 1543.61  4693.4 1537.60
  4751.9 1527.71  4795.7 1523.52  4810.4 1520.38  4816.0 1516.89  4826.2 1514.76
  4868.9 1512.82  4893.2 1514.40  4922.3 1515.84  4948.2 1514.69  4975.7 1508.62
  4979.4 1506.81  4986.8 1505.01  4987.0 1504.51  4990.9 1505.01  4997.0 1508.06
  5002.0 1508.06  5009.0 1512.50  5049.0 1523.69  5079.0 1528.63  5179.0 1530.70
  5329.0 1531.22  5350.5 1532.85  5389.0 1541.88  5408.7 1548.11  5413.4 1548.11
#Mann=8,-1,0
  4516.6    0.07       0  4573.8   0.035       0  4606.0    0.07       0
  4893.2    0.12       0  4979.4    0.07       0  4986.8    0.05       0
  4990.9    0.07       0  5350.5    0.12       0
Bank Sta=4986.8,4990.9
Exp/Cntr=0.3,0.1

Type RM Length L Ch R = 1,6854,469,469,469
BEGIN DESCRIPTION:
Stream0183_DS 15.0
END DESCRIPTION:
XS GIS Cut Line= 3
      2082575.00     13912974.99      2082525.00     13912875.00
      2082475.00     13912775.00
#Sta/Elev= 30
  4884.7 1549.59  4893.1 1549.63  4907.1 1548.47  4921.0 1544.45  4929.4 1540.52
  4937.8 1536.98  4943.4 1537.63  4951.8 1532.65  4960.2 1528.36  4965.7 1522.16
  4972.0 1503.03  4972.3 1502.53  4976.0 1502.53  4976.2 1503.03  4982.5 1503.21
  4988.1 1504.37  4993.7 1505.15  4999.3 1505.15  5004.9 1505.78  5010.5 1507.41
  5027.2 1508.21  5032.8 1509.70  5041.2 1511.19  5049.6 1514.19  5055.2 1516.63
  5063.6 1519.74  5077.6 1523.68  5085.9 1525.38  5094.3 1526.70  5108.3 1527.49
#Mann=3,-1,0
  4884.7    0.07       0  4972.0    0.05       0  4976.2    0.07       0
Bank Sta=4972,4976.2
Exp/Cntr=0.3,0.1

Type RM Length L Ch R = 1,6385,460,460,460
BEGIN DESCRIPTION:
Stream0183_DS 14.0
END DESCRIPTION:
XS GIS Cut Line= 3
      2082925.01     13912675.02      2082875.00     13912575.00
      2082725.00     13912475.00
#Sta/Elev= 30
  4888.4 1531.30  4910.8 1529.74  4924.8 1527.63  4933.1 1524.86  4947.1 1519.19
  4955.5 1517.43  4963.9 1517.89  4969.5 1513.41  4979.4 1508.70  4986.2 1504.69
  4991.8 1500.13  4995.3 1497.98  4995.6 1497.48  4999.3 1497.48  4999.5 1497.98
  5013.7 1498.63  5022.8 1500.98  5028.8 1501.98  5036.3 1505.75  5043.8 1508.13
  5049.8 1509.10  5064.8 1509.77  5072.3 1510.87  5079.8 1510.02  5094.9 1510.72
  5100.9 1510.45  5136.9 1518.06  5144.4 1521.18  5152.0 1522.92  5180.5 1524.20
#Mann=4,-1,0
  4888.4    0.07       0  4979.4    0.12       0  4995.3    0.05       0
  4999.5    0.12       0
Bank Sta=4995.3,4999.5
Exp/Cntr=0.3,0.1

Type RM Length L Ch R = 1,5925,588,588,588
BEGIN DESCRIPTION:
Stream0183_DS 13.0
END DESCRIPTION:
XS GIS Cut Line= 3
      2083274.99     13912574.98      2083025.00     13912175.00
      2082448.65     13912041.43
#Sta/Elev= 30
  4527.9 1541.56  4578.0 1539.35  4608.7 1531.75  4651.1 1527.30  4679.2 1518.69
  4787.9 1514.89  4846.3 1504.75  4934.1 1506.44  4970.1 1499.18  4974.4 1493.41
  4974.7 1492.91  4978.8 1493.41  5018.3 1498.64  5023.5 1496.46  5040.6 1498.04
  5061.0 1505.93  5066.2 1502.58  5071.4 1506.39  5108.8 1514.68  5194.2 1518.68
  5235.7 1525.23  5247.1 1530.72  5289.8 1542.35  5327.4 1545.14  5430.7 1561.57
  5482.0 1566.52  5502.6 1571.63  5508.3 1576.10  5523.1 1578.30  5591.2 1584.73
#Mann=4,-1,0
  4527.9    0.07       0  4679.2    0.12       0  4974.4    0.05       0
  4978.8    0.12       0
Bank Sta=4974.4,4978.8
Exp/Cntr=0.3,0.1

Type RM Length L Ch R = 1,5337,325,325,325
BEGIN DESCRIPTION:
Stream0183_DS 12.0
END DESCRIPTION:
XS GIS Cut Line= 3
      2083641.78     13912655.75      2083423.01     13912114.04
      2083167.22     13911878.99
#Sta/Elev= 30
  4425.5 1526.01  4431.0 1527.57  4447.9 1524.42  4455.1 1521.66  4460.5 1523.91
  4491.0 1515.40  4567.8 1511.76  4577.3 1512.40  4631.2 1509.72  4645.6 1510.66
  4771.4 1508.40  4890.0 1510.56  4914.0 1509.54  4922.4 1508.81  4954.8 1501.04
  4995.7 1488.26  4996.0 1487.76  5000.1 1488.26  5011.8 1488.31  5014.7 1490.72
  5057.3 1498.64  5064.1 1501.91  5071.5 1501.13  5099.8 1506.71  5163.3 1511.13
  5198.5 1511.38  5291.0 1515.52  5340.3 1520.19  5354.5 1523.44  5357.1 1525.76
#Mann=3,-1,0
  4425.5    0.12       0  4995.7    0.05       0  5000.1    0.12       0
Bank Sta=4995.7,5000.1
Exp/Cntr=0.3,0.1

Type RM Length L Ch R = 1,5012,449,449,449
BEGIN DESCRIPTION:
Stream0183_DS 11.0
END DESCRIPTION:
XS GIS Cut Line= 3
      2083909.12     13912322.38      2083675.00     13911925.00
      2083402.42     13911669.83
#Sta/Elev= 30
  4538.8 1526.55  4539.3 1526.55  4613.5 1520.65  4650.6 1514.34  4656.5 1511.99
  4672.1 1509.17  4677.9 1506.82  4686.6 1506.09  4715.0 1504.96  4744.7 1505.51
  4789.2 1502.41  4795.0 1501.10  4875.1 1504.10  4918.8 1504.59  4942.0 1503.42
  4949.3 1502.68  4970.7 1497.63  4992.2 1490.37  5003.4 1489.75  5007.1 1487.53
  5019.1 1484.70  5019.4 1484.20  5023.5 1484.70  5035.4 1495.33  5042.3 1498.50
  5063.8 1501.05  5098.9 1502.35  5191.3 1510.97  5304.1 1518.83  5373.4 1525.34
#Mann=4,-1,0
  4538.8    0.07       0  4539.3    0.12       0  5019.1    0.05       0
  5023.5    0.12       0
Bank Sta=5019.1,5023.5
Exp/Cntr=0.3,0.1

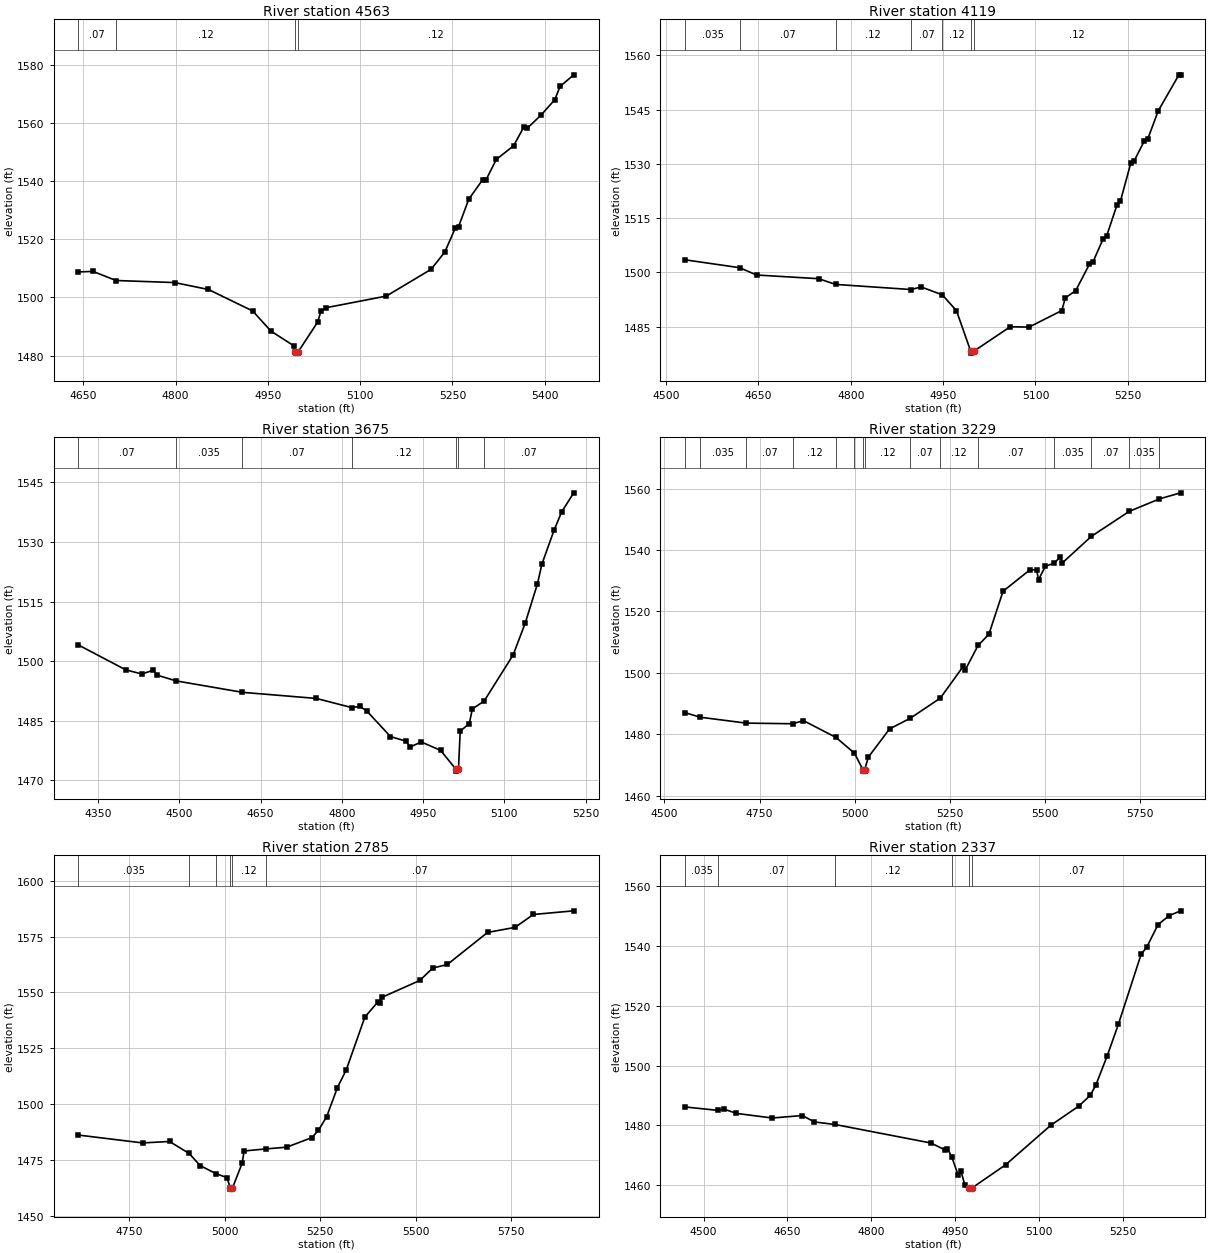
Type RM Length L Ch R = 1,4563,444,444,444
BEGIN DESCRIPTION:
Stream0183_DS 10.0
END DESCRIPTION:
XS GIS Cut Line= 3
      2084190.38     13911992.52      2084025.00     13911675.00
      2083825.01     13911275.02
#Sta/Elev= 30
  4642.0 1508.80  4665.9 1508.98  4703.3 1505.85  4798.5 1505.14  4853.4 1502.76
  4925.5 1495.35  4954.9 1488.46  4991.8 1483.43  4994.8 1481.35  4995.2 1480.85
  4999.5 1481.35  5030.8 1491.48  5036.3 1495.20  5044.7 1496.48  5142.6 1500.49
  5215.2 1509.68  5237.6 1515.62  5254.4 1523.76  5260.0 1524.41  5276.7 1533.87
  5299.1 1540.51  5304.7 1540.54  5321.4 1547.54  5349.4 1552.21  5366.2 1558.72
  5371.8 1558.29  5394.1 1562.80  5416.5 1568.12  5424.9 1572.65  5447.2 1576.65
#Mann=4,-1,0
  4642.0    0.07       0  4703.3    0.12       0  4994.8    0.05       0
  4999.5    0.12       0
Bank Sta=4994.8,4999.5
Exp/Cntr=0.3,0.1

Type RM Length L Ch R = 1,4119,444,444,444
BEGIN DESCRIPTION:
Stream0183_DS 9.0
END DESCRIPTION:
XS GIS Cut Line= 3
      2084634.81     13911815.42      2084375.00     13911425.00
      2084224.99     13911124.98
#Sta/Elev= 30
  4531.3 1503.49  4619.9 1501.31  4647.1 1499.30  4748.0 1498.28  4775.4 1496.70
  4897.7 1495.29  4914.6 1495.99  4948.8 1493.81  4971.7 1489.45  4994.9 1478.22
  4995.2 1477.72  4999.6 1478.22  5059.0 1485.00  5089.7 1484.92  5142.8 1489.48
  5148.4 1493.00  5165.2 1494.94  5187.5 1502.24  5193.1 1502.81  5209.9 1509.30
  5215.5 1510.05  5232.3 1518.63  5237.8 1519.62  5254.6 1530.10  5260.2 1530.82
  5277.0 1536.42  5282.6 1537.00  5299.3 1544.63  5332.9 1554.59  5335.7 1554.59
#Mann=7,-1,0
  4531.3   0.035       0  4619.9    0.07       0  4775.4    0.12       0
  4897.7    0.07       0  4948.8    0.12       0  4994.9    0.05       0
  4999.6    0.12       0
Bank Sta=4994.9,4999.6
Exp/Cntr=0.3,0.1

Type RM Length L Ch R = 1,3675,446,446,446
BEGIN DESCRIPTION:
Stream0183_DS 8.0
END DESCRIPTION:
XS GIS Cut Line= 3
      2085020.25     13911641.84      2084625.00     13911075.00
      2084425.04     13910975.02
#Sta/Elev= 30
  4313.4 1504.10  4401.1 1497.82  4430.8 1496.78  4451.7 1497.74  4457.8 1496.54
  4493.8 1495.05  4616.3 1492.17  4752.7 1490.63  4818.6 1488.31  4833.0 1488.65
  4846.0 1487.46  4889.7 1481.03  4919.1 1479.84  4925.5 1478.36  4946.4 1479.68
  4982.2 1477.55  5010.4 1472.83  5010.8 1472.33  5015.2 1472.83  5018.4 1482.38
  5035.2 1484.31  5040.8 1487.99  5062.6 1489.97  5116.2 1501.60  5138.6 1509.66
  5161.0 1519.50  5169.3 1524.47  5191.7 1533.00  5205.7 1537.59  5228.0 1542.39
#Mann=7,-1,0
  4313.4    0.07       0  4493.8   0.035       0  4616.3    0.07       0
  4818.6    0.12       0  5010.4    0.05       0  5015.2    0.12       0
  5062.6    0.07       0
Bank Sta=5010.4,5015.2
Exp/Cntr=0.3,0.1

Type RM Length L Ch R = 1,3229,444,444,444
BEGIN DESCRIPTION:
Stream0183_DS 7.0
END DESCRIPTION:
XS GIS Cut Line= 3
      2085124.43     13911138.39      2084875.00     13910775.00
      2084023.71     13910641.82
#Sta/Elev= 30
  4554.5 1487.03  4593.6 1485.56  4714.6 1483.64  4837.3 1483.43  4865.3 1484.45
  4951.0 1478.96  4999.4 1473.84  5021.6 1468.50  5022.0 1468.00  5026.5 1468.50
  5035.7 1472.52  5091.9 1481.77  5145.9 1485.20  5225.2 1491.79  5285.1 1502.08
  5290.1 1500.84  5324.5 1508.96  5352.8 1512.57  5390.0 1526.58  5460.9 1533.58
  5478.3 1533.55  5483.3 1530.37  5501.3 1534.71  5523.1 1535.69  5541.0 1537.73
  5546.0 1535.83  5622.4 1544.48  5721.7 1552.59  5801.3 1556.67  5856.9 1558.64
#Mann=15,-1,0
  4554.5    0.07       0  4593.6   0.035       0  4714.6    0.07       0
  4837.3    0.12       0  4951.0    0.07       0  4999.4    0.12       0
  5021.6    0.05       0  5026.5    0.12       0  5145.9    0.07       0
  5225.2    0.12       0  5324.5    0.07       0  5523.1   0.035       0
  5622.4    0.07       0  5721.7   0.035       0  5801.3    0.07       0
Bank Sta=5021.6,5026.5
Exp/Cntr=0.3,0.1

Type RM Length L Ch R = 1,2785,448,448,448
BEGIN DESCRIPTION:
Stream0183_DS 6.0
END DESCRIPTION:
XS GIS Cut Line= 3
      2085193.84     13911103.60      2085175.00     13910725.00
      2085433.41     13909843.26
#Sta/Elev= 30
  4616.6 1486.19  4785.4 1482.66  4855.5 1483.31  4907.1 1477.94  4935.6 1472.53
  4977.8 1468.87  5006.1 1467.15  5014.7 1462.49  5015.2 1461.99  5020.4 1462.49
  5045.8 1473.60  5051.0 1479.06  5107.6 1479.98  5162.4 1480.75  5228.5 1485.03
  5245.8 1488.35  5267.1 1494.34  5295.3 1507.39  5318.7 1515.42  5367.3 1538.99
  5400.7 1545.60  5405.9 1545.26  5412.5 1547.84  5511.4 1555.37  5544.8 1560.88
  5583.4 1562.51  5688.8 1576.85  5760.9 1579.11  5808.5 1584.87  5914.5 1586.51
#Mann=6,-1,0
  4616.6   0.035       0  4907.1    0.07       0  4977.8    0.12       0
  5014.7    0.05       0  5020.4    0.12       0  5107.6    0.07       0
Bank Sta=5014.7,5020.4
Exp/Cntr=0.3,0.1

Type RM Length L Ch R = 1,2337,382,382,382
BEGIN DESCRIPTION:
Stream0183_DS 5.0
END DESCRIPTION:
XS GIS Cut Line= 3
      2085377.88     13911169.58      2085575.00     13910675.00
      2085625.01     13910324.96
#Sta/Elev= 30
  4467.2 1486.17  4525.6 1485.03  4536.7 1485.44  4558.8 1484.02  4622.8 1482.48
  4676.7 1483.31  4698.2 1481.16  4734.8 1480.32  4906.6 1474.12  4930.9 1471.90
  4936.2 1472.25  4944.0 1469.41  4955.1 1463.55  4960.5 1464.63  4967.3 1460.06
  4975.2 1459.20  4975.7 1458.70  4980.9 1459.20  5040.0 1466.81  5120.8 1480.02
  5171.3 1486.49  5191.5 1490.05  5201.6 1493.50  5221.8 1503.23  5242.0 1513.88
  5282.5 1537.21  5292.6 1539.61  5312.8 1547.16  5333.0 1550.17  5353.2 1551.75
#Mann=6,-1,0
  4467.2   0.035       0  4525.6    0.07       0  4734.8    0.12       0
  4944.0    0.07       0  4975.2    0.05       0  4980.9    0.07       0
Bank Sta=4975.2,4980.9
Exp/Cntr=0.3,0.1

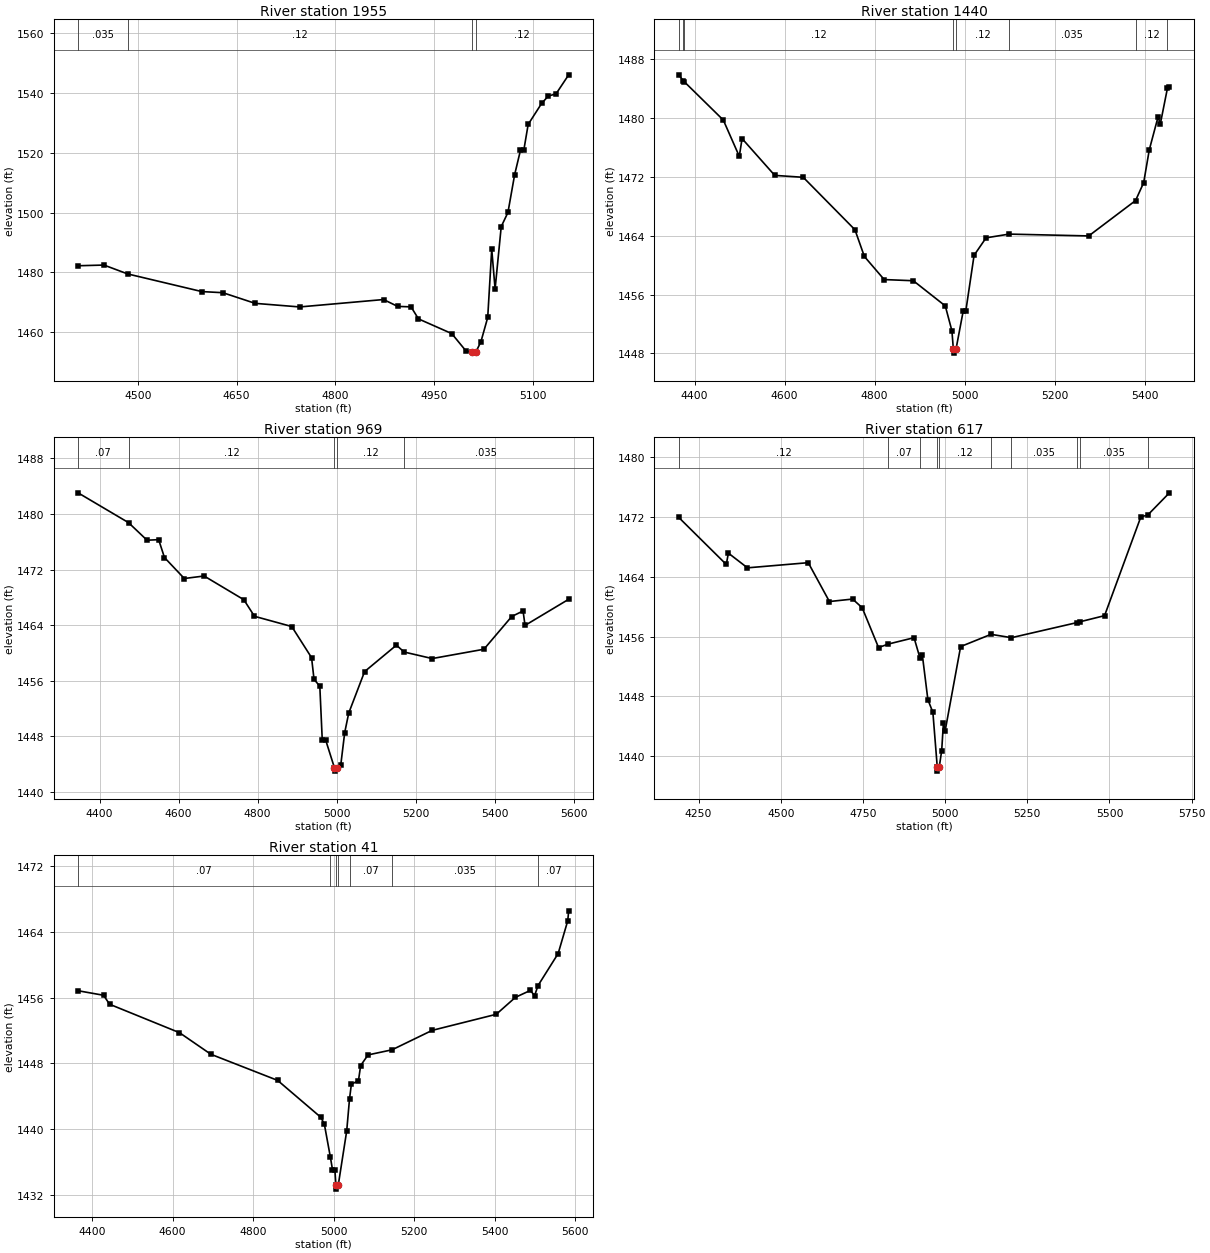
Type RM Length L Ch R = 1,1955,515,515,515
BEGIN DESCRIPTION:
Stream0183_DS 4.0
END DESCRIPTION:
XS GIS Cut Line= 3
      2085759.82     13911232.09      2085957.73     13910673.07
      2085924.99     13910524.97
#Sta/Elev= 30
  4409.3 1482.22  4448.6 1482.45  4484.6 1479.48  4597.2 1473.57  4629.0 1473.20
  4678.1 1469.63  4745.7 1468.43  4873.0 1470.91  4894.4 1468.61  4914.7 1468.46
  4926.0 1464.43  4976.5 1459.51  4998.6 1453.57  5007.7 1453.47  5008.2 1452.97
  5013.4 1453.47  5020.8 1456.80  5031.1 1464.91  5037.2 1487.76  5042.3 1474.42
  5051.6 1495.32  5061.8 1500.06  5072.0 1512.75  5080.8 1520.86  5085.9 1520.92
  5092.5 1529.53  5113.0 1536.58  5123.2 1539.06  5134.7 1539.72  5154.0 1546.13
#Mann=4,-1,0
  4409.3   0.035       0  4484.6    0.12       0  5007.7    0.05       0
  5013.4    0.12       0
Bank Sta=5007.7,5013.4
Exp/Cntr=0.3,0.1

Type RM Length L Ch R = 1,1440,471,471,471
BEGIN DESCRIPTION:
Stream0183_DS 3.0
END DESCRIPTION:
XS GIS Cut Line= 3
      2085999.42     13911436.94      2086375.00     13910925.00
      2086516.77     13910492.48
#Sta/Elev= 30
  4364.8 1485.87  4374.6 1485.06  4376.8 1484.94  4463.7 1479.72  4499.2 1474.79
  4505.4 1477.20  4578.0 1472.20  4641.3 1471.94  4756.2 1464.81  4777.1 1461.18
  4821.1 1458.04  4885.9 1457.88  4956.9 1454.46  4971.6 1451.08  4974.9 1448.54
  4975.4 1448.04  4980.6 1448.54  4996.6 1453.72  5002.4 1453.72  5020.9 1461.34
  5047.5 1463.71  5098.7 1464.22  5275.6 1463.97  5379.7 1468.78  5397.7 1471.21
  5410.2 1475.68  5429.5 1480.11  5434.8 1479.22  5450.5 1484.05  5454.9 1484.16
#Mann=8,-1,0
  4364.8   0.035       0  4374.6    0.07       0  4376.8    0.12       0
  4974.9    0.05       0  4980.6    0.12       0  5098.7   0.035       0
  5379.7    0.12       0  5450.5    0.07       0
Bank Sta=4974.9,4980.6
Exp/Cntr=0.3,0.1

Type RM Length L Ch R = 1,969,352,352,352
BEGIN DESCRIPTION:
Stream0183_DS 2.0
END DESCRIPTION:
XS GIS Cut Line= 3
      2086145.60     13911610.44      2086675.00     13911225.00
      2086607.04     13910641.80
#Sta/Elev= 30
  4345.3 1483.06  4473.0 1478.77  4519.9 1476.24  4549.3 1476.32  4564.0 1473.75
  4614.2 1470.73  4664.4 1471.09  4764.9 1467.68  4791.9 1465.29  4886.2 1463.82
  4936.4 1459.34  4942.6 1456.23  4957.3 1455.22  4963.4 1447.56  4971.9 1447.52
  4994.2 1443.51  4994.6 1443.01  5000.0 1443.51  5010.2 1443.84  5020.3 1448.56
  5030.4 1451.35  5070.6 1457.33  5151.2 1461.14  5170.7 1460.15  5241.8 1459.21
  5372.7 1460.55  5443.1 1465.26  5471.8 1466.06  5476.8 1463.98  5587.3 1467.74
#Mann=5,-1,0
  4345.3    0.07       0  4473.0    0.12       0  4994.2    0.05       0
  5000.0    0.12       0  5170.7   0.035       0
Bank Sta=4994.2,5000
Exp/Cntr=0.3,0.1

Type RM Length L Ch R = 1,617,576,576,576
BEGIN DESCRIPTION:
Stream0183_DS 1.0
END DESCRIPTION:
XS GIS Cut Line= 4
      2086426.93     13911709.18      2086974.90     13911289.00
      2087011.58     13911174.98      2086657.21     13910591.92
#Sta/Elev= 30
  4189.7 1471.95  4334.2 1465.66  4340.5 1467.18  4398.6 1465.21  4583.5 1465.90
  4647.9 1460.70  4718.5 1461.03  4747.6 1459.87  4797.4 1454.54  4827.2 1455.01
  4905.4 1455.86  4923.8 1453.08  4930.6 1453.55  4947.5 1447.56  4962.7 1445.87
  4976.1 1438.50  4976.5 1438.00  4981.9 1438.50  4989.5 1440.75  4994.8 1444.48
  5000.0 1443.39  5047.1 1454.67  5139.6 1456.31  5201.8 1455.86  5400.0 1457.87
  5411.1 1458.00  5485.0 1458.81  5595.4 1472.03  5616.4 1472.28  5682.3 1475.25
#Mann=10,-1,0
  4189.7    0.12       0  4827.2    0.07       0  4923.8    0.12       0
  4976.1    0.05       0  4981.9    0.12       0  5139.6    0.07       0
  5201.8   0.035       0  5400.0    0.07       0  5411.1   0.035       0
  5616.4    0.07       0
Bank Sta=4976.1,4981.9
Exp/Cntr=0.3,0.1

Type RM Length L Ch R = 1,41,0,0,0
BEGIN DESCRIPTION:
Stream0183_DS 0.0
END DESCRIPTION:
XS GIS Cut Line= 5
      2087136.89     13911326.02      2087325.36     13911049.44
      2087361.04     13910820.74      2087345.58     13910754.27
      2086807.26     13910529.38
#Sta/Elev= 30
  4365.6 1456.83  4428.9 1456.28  4443.8 1455.19  4617.3 1451.74  4695.2 1449.12
  4860.9 1445.95  4968.4 1441.46  4977.0 1440.61  4991.9 1436.63  4997.1 1435.12
  5003.0 1435.12  5005.6 1433.25  5006.1 1432.75  5011.5 1433.25  5032.4 1439.81
  5039.4 1443.71  5044.0 1445.48  5061.6 1445.92  5067.0 1447.75  5085.4 1449.04
  5144.9 1449.66  5244.5 1452.02  5403.6 1453.97  5451.2 1456.03  5488.3 1456.87
  5498.8 1456.23  5507.2 1457.45  5557.3 1461.35  5581.1 1465.33  5583.4 1466.53
#Mann=7,-1,0
  4365.6    0.07       0  4991.9    0.12       0  5005.6    0.05       0
  5011.5    0.12       0  5039.4    0.07       0  5144.9   0.035       0
  5507.2    0.07       0
Bank Sta=5005.6,5011.5
Exp/Cntr=0.3,0.1

Chan Stop Cuts=-1