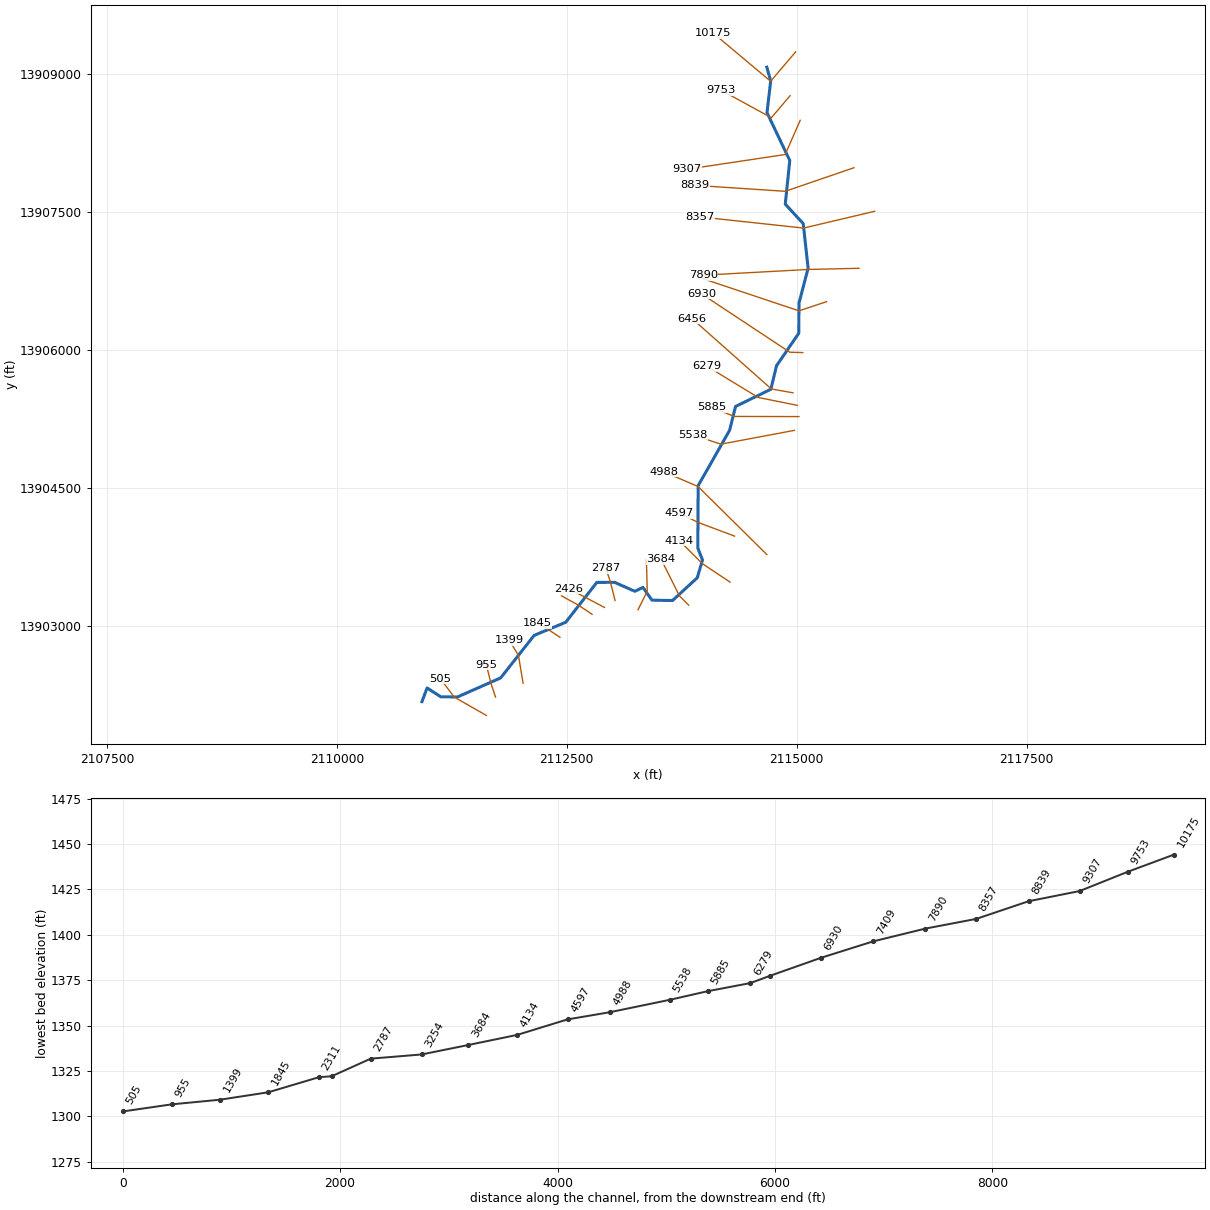
--- Stream0184_DS.prj (project) ---

Proj Title=Stream0184_DS Base Level Engineering
Current Plan=p01
Default Exp/Contr=0.3,0.1
English Units
Geom File=g01
Flow File=f01
Plan File=p01
Y Axis Title=Elevation
X Axis Title(PF)=Main Channel Distance
X Axis Title(XS)=Station
BEGIN DESCRIPTION:
Stream0184_DS
END DESCRIPTION:
DSS Export Rating Curves= 0
DSS Export Rating Curve Sorted= 0
DSS Export Volume Flow Curves= 0
DXF OffsetX= 0
DXF OffsetY= 0
DXF ScaleX= 1
DXF ScaleY= 10

--- Stream0184_DS.p01 (plan) ---

Plan Title=Multiple Run
Short Identifier=Multiple
Geom File=g01
Flow File=f01
Subcritical Flow
K Sum by GR= 0
Std Step Tol= 0.01
Critical Tol= 0.01
Num of Std Step Trials= 20
Max Error Tol= 0.3
Flow Tol Ratio= 0.001
Split Flow NTrial= 30
Split Flow Tol= 0.02
Split Flow Ratio= 0.02
Log Output Level= 0
Friction Slope Method= 1
Unsteady Friction Slope Method= 2
Unsteady Bridges Friction Slope Method= 1
Parabolic Critical Depth
Global Vel Dist=  1 , 1 , 1
Global Log Level= 0
CheckData=True
Encroach Param= -1, 0, 0, 0
BEGIN DESCRIPTION:
Multiple Run
END DESCRIPTION:

--- Stream0184_DS.f01 (steady flow) ---

Flow Title=Multiple
Program Version=4.10
Number of Profiles= 7
Profile Names=10-year,25-year,50-year,1pct_min,100-year,1pct_plu,500-year
River Rch & RM=Stream0184_DS,Reach-1         ,10175
    1323    2275    3196    2177    4343    8666    7930
River Rch & RM=Stream0184_DS,Reach-1         ,7890
    1725    3004    4255    2918    5821   11615   10782
Boundary for River Rch & Prof#=Stream0184_DS,Reach-1         , 1
Up Type= 0
Dn Type= 3
Dn Slope=0.005
Boundary for River Rch & Prof#=Stream0184_DS,Reach-1         , 2
Up Type= 0
Dn Type= 3
Dn Slope=0.005
Boundary for River Rch & Prof#=Stream0184_DS,Reach-1         , 3
Up Type= 0
Dn Type= 3
Dn Slope=0.005
Boundary for River Rch & Prof#=Stream0184_DS,Reach-1         , 4
Up Type= 0
Dn Type= 3
Dn Slope=0.005
Boundary for River Rch & Prof#=Stream0184_DS,Reach-1         , 5
Up Type= 0
Dn Type= 3
Dn Slope=0.005
Boundary for River Rch & Prof#=Stream0184_DS,Reach-1         , 6
Up Type= 0
Dn Type= 3
Dn Slope=0.005
Boundary for River Rch & Prof#=Stream0184_DS,Reach-1         , 7
Up Type= 0
Dn Type= 3
Dn Slope=0.005
DSS Import GetInterval= 0
DSS Import GetPeak= 0
DSS Import FillOption= 0

--- Stream0184_DS.g01 (geometry) ---

Geom Title=Existing Conditions
Program Version=4.10

River Reach=Stream0184_DS   ,Reach-1
Reach XY= 30
        2114675.       13909075.      2114717.49     13908925.01
      2114677.26     13908580.94      2114924.92     13908059.61
      2114876.04     13907585.44      2115071.46     13907373.53
      2115124.32     13906888.92      2115025.52     13906509.78
      2115022.76     13906180.93      2114780.52     13905827.43
      2114719.58     13905572.32      2114335.11     13905384.95
      2114271.17     13905126.58      2113928.55     13904523.53
      2113925.07     13903845.03      2113975.78     13903715.86
      2113919.48     13903522.57      2113650.12      13903274.7
      2113426.25     13903278.45      2113328.66     13903417.28
      2113240.42     13903375.15      2113019.06     13903472.74
      2112826.46     13903471.47      2112488.65     13903038.26
      2112144.77     13902895.42      2111781.07     13902433.15
      2111311.08     13902225.68      2111130.86     13902227.07
      2110980.85     13902323.52        2110925.       13902175.

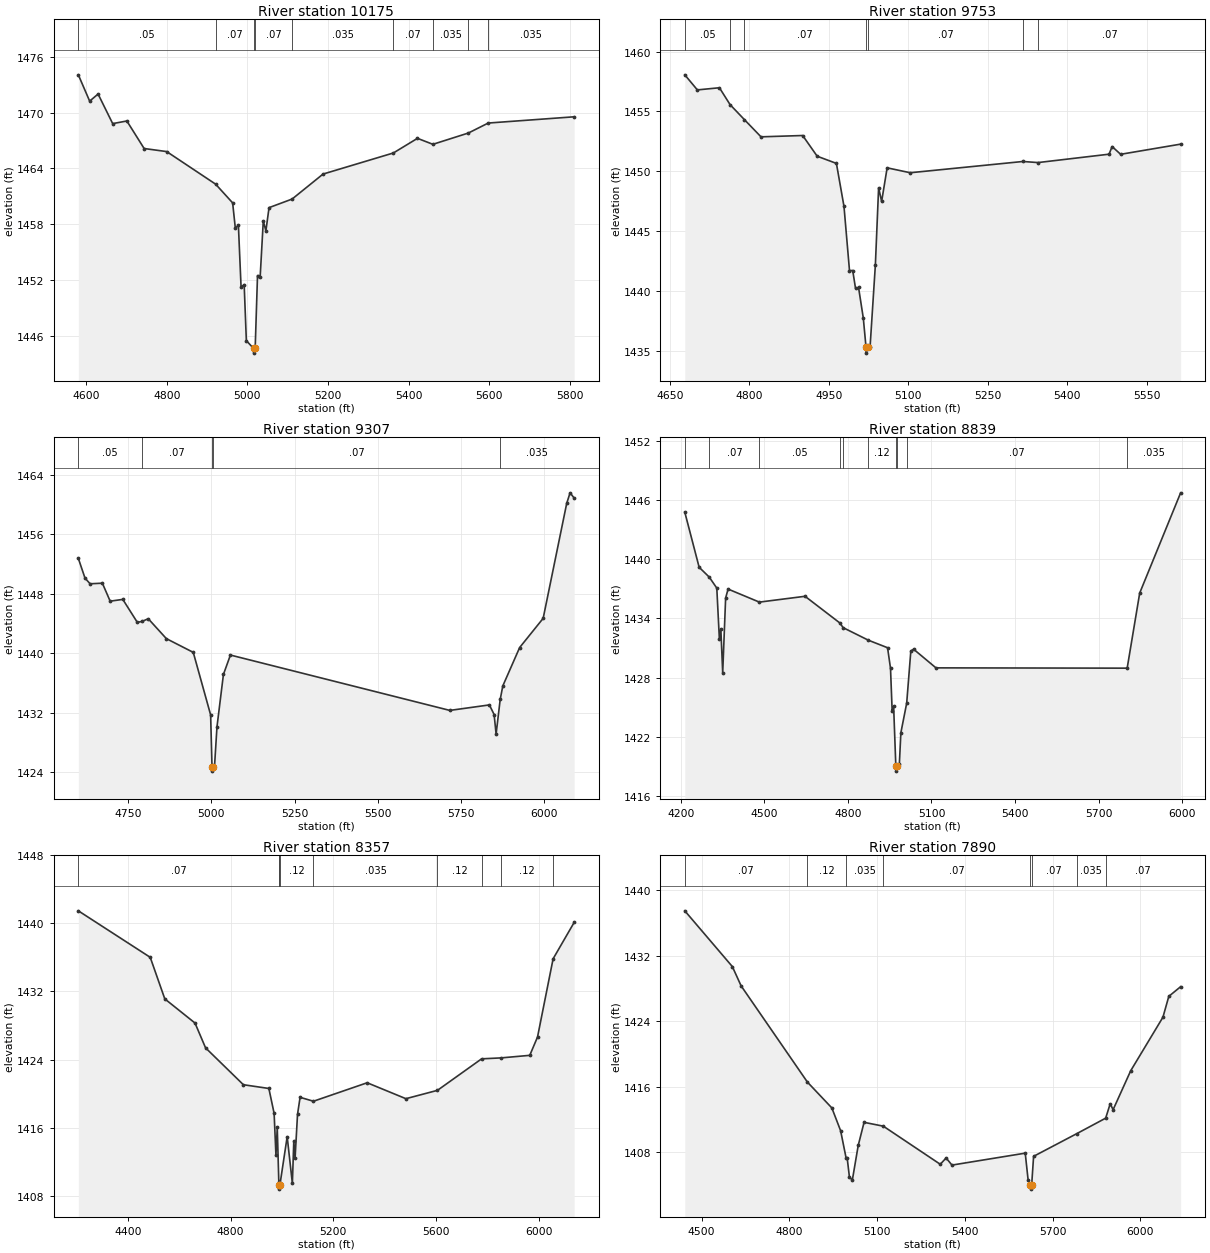
Type RM Length L Ch R = 1 ,10175   ,422,422,422
BEGIN DESCRIPTION:
Stream0184_DS 22.0
END DESCRIPTION:
XS GIS Cut Line= 3
      2114988.53     13909241.04      2114716.95     13908921.71
      2114095.62      13909442.6
#Sta/Elev= 30
  4580.8 1474.04  4608.9 1471.22  4629.8 1471.98    4666 1468.81  4701.2 1469.09
    4744 1466.14    4800 1465.81  4921.3 1462.32  4963.6 1460.31  4970.2 1457.62
  4977.9 1457.89  4984.5 1451.27  4992.2 1451.55  4997.6 1445.54  5015.5  1444.7
  5015.8  1444.2  5019.5  1444.7  5025.3 1452.52  5031.8 1452.32  5039.6 1458.36
  5046.1 1457.32  5053.9  1459.8  5111.1 1460.72  5187.9  1463.4  5362.3 1465.66
  5422.1 1467.23  5460.4 1466.59  5548.4  1467.8  5597.7 1468.87  5810.8 1469.54
#Mann= 9 ,-1 , 0
  4580.8     .05       0  4921.3     .07       0  5015.5     .05       0
  5019.5     .07       0  5111.1    .035       0  5362.3     .07       0
  5460.4    .035       0  5548.4     .07       0  5597.7    .035       0
Bank Sta=5015.5,5019.5
XS Rating Curve= 0 ,0
Exp/Cntr=0.3,0.1

Type RM Length L Ch R = 1 ,9753    ,446,446,446
BEGIN DESCRIPTION:
Stream0184_DS 21.0
END DESCRIPTION:
XS GIS Cut Line= 3
      2114928.14     13908764.83        2114725.       13908525.
      2114179.42     13908823.72
#Sta/Elev= 30
  4678.1 1458.06  4701.8  1456.8  4743.5 1456.98  4763.6 1455.57  4790.6 1454.32
    4822 1452.88  4900.7 1452.99  4928.1 1451.26  4964.4 1450.66  4978.7 1447.07
  4989.1 1441.71  4995.2 1441.71  5000.5 1440.22  5006.2  1440.3  5015.2 1437.73
  5020.3 1435.31  5020.5 1434.81  5024.3 1435.31    5028 1435.35    5038  1442.2
  5044.1 1448.63  5049.8 1447.48  5060.2 1450.29  5103.8 1449.88  5316.5 1450.82
  5345.1 1450.73  5479.3 1451.43    5485 1452.07  5501.1 1451.42  5614.4 1452.27
#Mann= 7 ,-1 , 0
  4678.1     .05       0  4763.6    .035       0  4790.6     .07       0
  5020.3     .05       0  5024.3     .07       0  5316.5    .035       0
  5345.1     .07       0
Bank Sta=5020.3,5024.3
XS Rating Curve= 0 ,0
Exp/Cntr=0.3,0.1

Type RM Length L Ch R = 1 ,9307    ,468,468,468
BEGIN DESCRIPTION:
Stream0184_DS 20.0
END DESCRIPTION:
XS GIS Cut Line= 3
      2115038.53     13908497.46        2114875.       13908125.
      2113802.87     13907964.16
#Sta/Elev= 30
    4600 1452.75  4620.1 1450.09  4635.4 1449.33  4672.3 1449.41  4695.7 1446.99
  4733.7 1447.23  4777.4 1444.14  4791.9 1444.27  4810.2 1444.63  4864.7 1441.95
  4945.6  1440.1  4997.8 1431.69    5002 1424.62  5002.3 1424.12    5006 1424.62
  5009.3 1424.62  5016.9 1430.08  5036.3 1437.13  5057.3 1439.74  5717.1 1432.29
    5836 1433.03  5850.2 1431.74  5856.2 1429.11  5868.5 1433.76  5876.4 1435.59
    5927 1440.75  5997.7 1444.68  6068.5 1460.15  6078.6 1461.57  6090.9 1460.87
#Mann= 5 ,-1 , 0
    4600     .05       0  4791.9     .07       0    5002     .05       0
    5006     .07       0  5868.5    .035       0
Bank Sta=5002,5006
XS Rating Curve= 0 ,0
Exp/Cntr=0.3,0.1

Type RM Length L Ch R = 1 ,8839    ,482,482,482
BEGIN DESCRIPTION:
Stream0184_DS 19.0
END DESCRIPTION:
XS GIS Cut Line= 3
      2115623.72      13907981.5        2114875.       13907725.
      2113888.39     13907790.18
#Sta/Elev= 30
  4214.4 1444.76  4265.9 1439.18  4302.3 1438.18  4329.3 1437.07  4338.5 1431.94
  4343.8 1432.94  4350.5 1428.49    4361 1436.06  4369.8 1436.97  4482.1 1435.65
  4646.1 1436.24  4770.5 1433.55  4783.1 1433.06  4873.6 1431.79  4942.4 1431.03
    4953 1428.94  4958.9 1424.62  4964.2 1425.09  4972.1 1419.03  4972.4 1418.53
  4976.1 1419.03  4984.7 1419.23  4990.2 1422.42  5011.1 1425.42  5025.9 1430.69
  5035.9 1430.88  5116.1 1428.99  5802.7 1428.96  5847.7 1436.57  5994.6 1446.72
#Mann= 10 ,-1 , 0
  4214.4     .12       0  4302.3     .07       0  4482.1     .05       0
  4770.5     .07       0  4783.1     .05       0  4873.6     .12       0
  4972.1     .05       0  4976.1     .12       0  5011.1     .07       0
  5802.7    .035       0
Bank Sta=4972.1,4976.1
XS Rating Curve= 0 ,0
Exp/Cntr=0.3,0.1

Type RM Length L Ch R = 1 ,8357    ,467,467,467
BEGIN DESCRIPTION:
Stream0184_DS 18.0
END DESCRIPTION:
XS GIS Cut Line= 3
      2115847.66     13907507.54        2115075.       13907325.
      2113943.01     13907447.23
#Sta/Elev= 30
  4206.4 1441.47  4486.6 1436.01  4543.4 1431.13  4661.2 1428.29  4702.3 1425.38
  4849.7 1421.05    4949 1420.61  4969.5 1417.69  4976.6 1412.78  4981.7 1416.03
  4987.8 1409.61  4988.1 1409.29  4988.3 1408.79  4992.1 1409.29  5020.4 1414.95
  5040.6 1409.46  5046.2 1414.43  5051.3 1412.48  5060.7 1417.57  5070.7 1419.57
  5122.8 1419.11  5332.2 1421.28  5483.1 1419.41  5606.1 1420.39  5778.2 1424.09
    5854  1424.2  5965.9  1424.5  5996.1 1426.65  6056.9 1435.84  6138.9 1440.11
#Mann= 9 ,-1 , 0
  4206.4     .07       0  4987.8     .12       0  4988.1     .05       0
  4992.1     .12       0  5122.8    .035       0  5606.1     .12       0
  5778.2     .07       0    5854     .12       0  6056.9     .07       0
Bank Sta=4988.1,4992.1
XS Rating Curve= 0 ,0
Exp/Cntr=0.3,0.1

Type RM Length L Ch R = 1 ,7890    ,481,481,481
BEGIN DESCRIPTION:
Stream0184_DS 17.0
END DESCRIPTION:
XS GIS Cut Line= 3
      2115677.45     13906887.77        2115125.       13906875.
      2113984.69     13906812.85
#Sta/Elev= 30
  4442.7 1437.49  4605.2 1430.67  4635.2 1428.31  4861.8 1416.54  4945.3 1413.38
  4975.3 1410.59  4994.2 1407.22  4997.8 1407.22  5005.3 1404.94  5015.3 1404.55
  5035.4 1408.79  5055.4 1411.62  5121.2 1411.15  5315.8 1406.49  5335.8 1407.26
  5355.8 1406.39  5606.2 1407.85  5616.2 1404.53  5624.2 1403.95  5624.5 1403.45
  5628.2 1403.95  5634.8 1407.46  5782.6 1410.24  5881.1 1412.13  5896.6 1413.89
  5906.6 1413.17  5966.7 1417.93  6076.9 1424.48  6096.9 1427.03  6137.3 1428.21
#Mann= 8 ,-1 , 0
  4442.7     .07       0  4861.8     .12       0  4994.2    .035       0
  5121.2     .07       0  5624.2    .035       0  5628.2     .07       0
  5782.6    .035       0  5881.1     .07       0
Bank Sta=5624.2,5628.2
XS Rating Curve= 0 ,0
Exp/Cntr=0.3,0.1

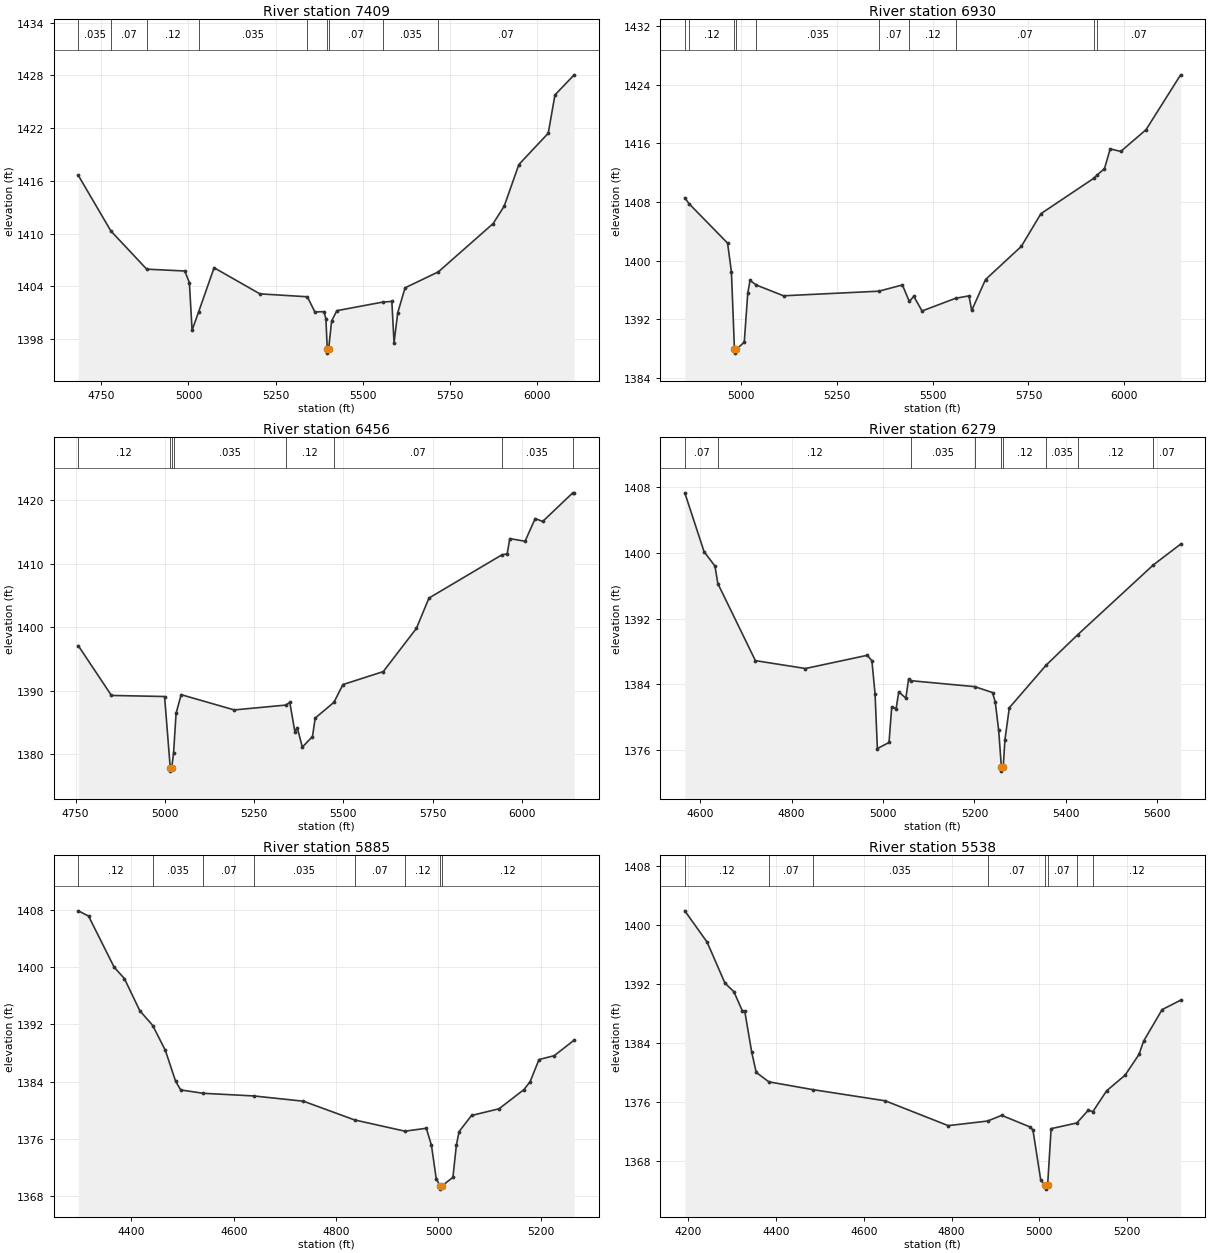
Type RM Length L Ch R = 1 ,7409    ,479,479,479
BEGIN DESCRIPTION:
Stream0184_DS 16.0
END DESCRIPTION:
XS GIS Cut Line= 3
      2115324.99       13906525.        2115025.       13906425.
      2113974.43     13906776.41
#Sta/Elev= 30
  4683.7 1416.61  4777.2 1410.29    4880 1405.95  4989.4 1405.74  5002.6 1404.42
  5010.4 1399.01    5029 1401.07  5073.6 1406.11  5205.2 1403.14  5341.4 1402.81
  5363.1 1401.08  5389.4 1401.12  5394.7 1400.29  5398.6  1396.9  5398.9  1396.4
  5402.6  1396.9  5411.2 1400.06  5426.2 1401.23  5558.6 1402.21  5584.1 1402.28
  5590.4 1397.57    5601 1400.99  5622.1 1403.83  5717.6 1405.64  5875.1 1411.14
  5906.8 1413.12  5948.9 1417.85  6033.3 1421.41  6052.5 1425.76  6107.7 1428.05
#Mann= 9 ,-1 , 0
  4683.7    .035       0  4777.2     .07       0    4880     .12       0
    5029    .035       0  5341.4     .07       0  5398.6     .05       0
  5402.6     .07       0  5558.6    .035       0  5717.6     .07       0
Bank Sta=5398.6,5402.6
XS Rating Curve= 0 ,0
Exp/Cntr=0.3,0.1

Type RM Length L Ch R = 1 ,6930    ,474,474,474
BEGIN DESCRIPTION:
Stream0184_DS 15.0
END DESCRIPTION:
XS GIS Cut Line= 3
      2115066.43     13905971.07        2114925.       13905975.
       2113964.8      13906609.9
#Sta/Elev= 30
  4854.1 1408.55  4865.2 1407.75  4965.6 1402.38  4975.6 1398.49  4983.6 1387.87
  4983.8 1387.37  4987.6 1387.87  5009.1 1388.85  5018.2 1395.53  5024.2 1397.28
  5040.9 1396.65  5111.5 1395.19  5360.1 1395.82  5421.4 1396.67  5439.4 1394.42
  5451.1 1395.12  5472.6 1393.12    5560 1394.85    5595 1395.18    5602 1393.19
  5638.1 1397.41  5731.4 1401.93  5782.5 1406.39  5921.8 1411.27  5928.8 1411.67
  5948.1 1412.51  5963.1 1415.23  5990.6 1414.88  6056.4 1417.84  6146.7 1425.33
#Mann= 10 ,-1 , 0
  4854.1     .07       0  4865.2     .12       0  4983.6     .05       0
  4987.6     .12       0  5040.9    .035       0  5360.1     .07       0
  5439.4     .12       0    5560     .07       0  5921.8    .035       0
  5928.8     .07       0
Bank Sta=4983.6,4987.6
XS Rating Curve= 0 ,0
Exp/Cntr=0.3,0.1

Type RM Length L Ch R = 1 ,6456    ,177,177,177
BEGIN DESCRIPTION:
Stream0184_DS 14.0
END DESCRIPTION:
XS GIS Cut Line= 3
       2114959.6     13905533.58        2114725.       13905575.
      2113864.55     13906338.99
#Sta/Elev= 30
  4757.7 1397.07  4850.4 1389.25  4999.3 1389.08  5015.2 1377.84  5015.5 1377.34
  5019.2 1377.84  5024.4 1380.13  5031.5 1386.43  5045.7 1389.37  5194.5 1386.97
  5338.2 1387.73  5350.1 1388.14  5364.3 1383.53    5371 1384.18  5385.2 1381.12
  5413.6 1382.78  5421.2 1385.69  5473.7 1388.17  5498.9 1390.96  5611.8    1393
  5704.7  1399.8  5739.8 1404.57  5944.7 1411.39  5958.9 1411.52  5966.4 1413.93
  6009.1 1413.51  6037.5 1417.09  6058.4 1416.62  6142.7 1421.13  6146.6 1421.11
#Mann= 8 ,-1 , 0
  4757.7     .12       0  5015.2     .05       0  5019.2     .12       0
  5024.4    .035       0  5338.2     .12       0  5473.7     .07       0
  5944.7    .035       0  6142.7     .07       0
Bank Sta=5015.2,5019.2
XS Rating Curve= 0 ,0
Exp/Cntr=0.3,0.1

Type RM Length L Ch R = 1 ,6279    ,394,394,394
BEGIN DESCRIPTION:
Stream0184_DS 13.5
END DESCRIPTION:
XS GIS Cut Line= 3
      2115006.41     13905397.29      2114581.08      13905483.1
      2114024.99     13905822.15
#Sta/Elev= 30
  4566.1 1407.31  4608.3 1400.14  4632.1 1398.39  4638.4 1396.26  4720.6 1386.87
  4830.2 1385.91  4965.4 1387.52  4975.6 1386.86  4982.5 1382.83  4987.6 1376.16
  5013.1  1376.9    5019 1381.24  5028.6 1381.02  5034.4 1383.06  5049.9  1382.3
  5055.8 1384.58  5062.1 1384.42  5200.7  1383.7  5239.6 1382.98  5245.5 1381.85
  5253.1 1378.38    5259 1373.91  5259.2 1373.41    5263 1373.91  5266.8 1377.24
  5276.4 1381.13  5357.3 1386.34  5426.3 1390.04  5591.6 1398.53  5651.3 1401.06
#Mann= 9 ,-1 , 0
  4566.1     .07       0  4638.4     .12       0  5062.1    .035       0
  5200.7     .12       0    5259     .05       0    5263     .12       0
  5357.3    .035       0  5426.3     .12       0  5591.6     .07       0
Bank Sta=5259,5263
XS Rating Curve= 0 ,0
Exp/Cntr=0.3,0.1

Type RM Length L Ch R = 1 ,5885    ,347,347,347
BEGIN DESCRIPTION:
Stream0184_DS 13.0
END DESCRIPTION:
XS GIS Cut Line= 3
      2115024.97       13905275.      2114321.17     13905276.59
      2114075.01     13905374.99
#Sta/Elev= 30
  4296.2 1407.92  4316.2 1407.18  4366.2 1400.02  4386.2 1398.43  4416.2 1393.94
  4441.6 1391.85  4466.2 1388.37  4486.2 1384.06  4496.2 1382.82  4540.2 1382.35
  4638.8 1381.98  4736.2 1381.24  4835.9 1378.62  4934.5 1377.04  4976.2 1377.45
  4986.2 1375.08  4995.6 1370.36  5002.7 1369.42  5003.1 1368.92  5007.7 1369.42
  5028.2 1370.58  5034.9 1375.06  5040.2 1376.98  5064.5 1379.24  5118.3 1380.18
  5166.8 1382.86    5179 1383.97  5196.4 1387.08  5226.1 1387.62  5265.1  1389.8
#Mann= 8 ,-1 , 0
  4296.2     .12       0  4441.6    .035       0  4540.2     .07       0
  4638.8    .035       0  4835.9     .07       0  4934.5     .12       0
  5002.7     .05       0  5007.7     .12       0
Bank Sta=5002.7,5007.7
XS Rating Curve= 0 ,0
Exp/Cntr=0.3,0.1

Type RM Length L Ch R = 1 ,5538    ,550,550,550
BEGIN DESCRIPTION:
Stream0184_DS 12.0
END DESCRIPTION:
XS GIS Cut Line= 3
        2114975.       13905125.        2114175.       13904975.
      2113874.97     13905075.01
#Sta/Elev= 30
  4191.7 1401.88  4242.6 1397.64  4283.3 1392.08  4303.6 1390.93  4323.1  1388.3
  4328.2 1388.35  4344.3 1382.71  4354.5    1380  4383.3 1378.72    4483 1377.67
  4648.7 1376.15    4792 1372.79  4881.8 1373.41  4914.1 1374.18  4979.4 1372.59
  4985.3 1372.19  5003.1 1365.39  5013.6 1364.69    5014 1364.19  5018.7 1364.69
  5026.7 1372.38  5085.3 1373.15    5111 1374.85    5122  1374.7  5153.2 1377.51
  5195.4 1379.63    5227 1382.43  5237.5 1384.23  5279.7  1388.5  5321.9 1389.78
#Mann= 8 ,-1 , 0
  4191.7     .12       0  4383.3     .07       0    4483    .035       0
  4881.8     .07       0  5013.6     .05       0  5018.7     .07       0
  5085.3     .07       0    5122     .12       0
Bank Sta=5013.6,5018.7
XS Rating Curve= 0 ,0
Exp/Cntr=0.3,0.1

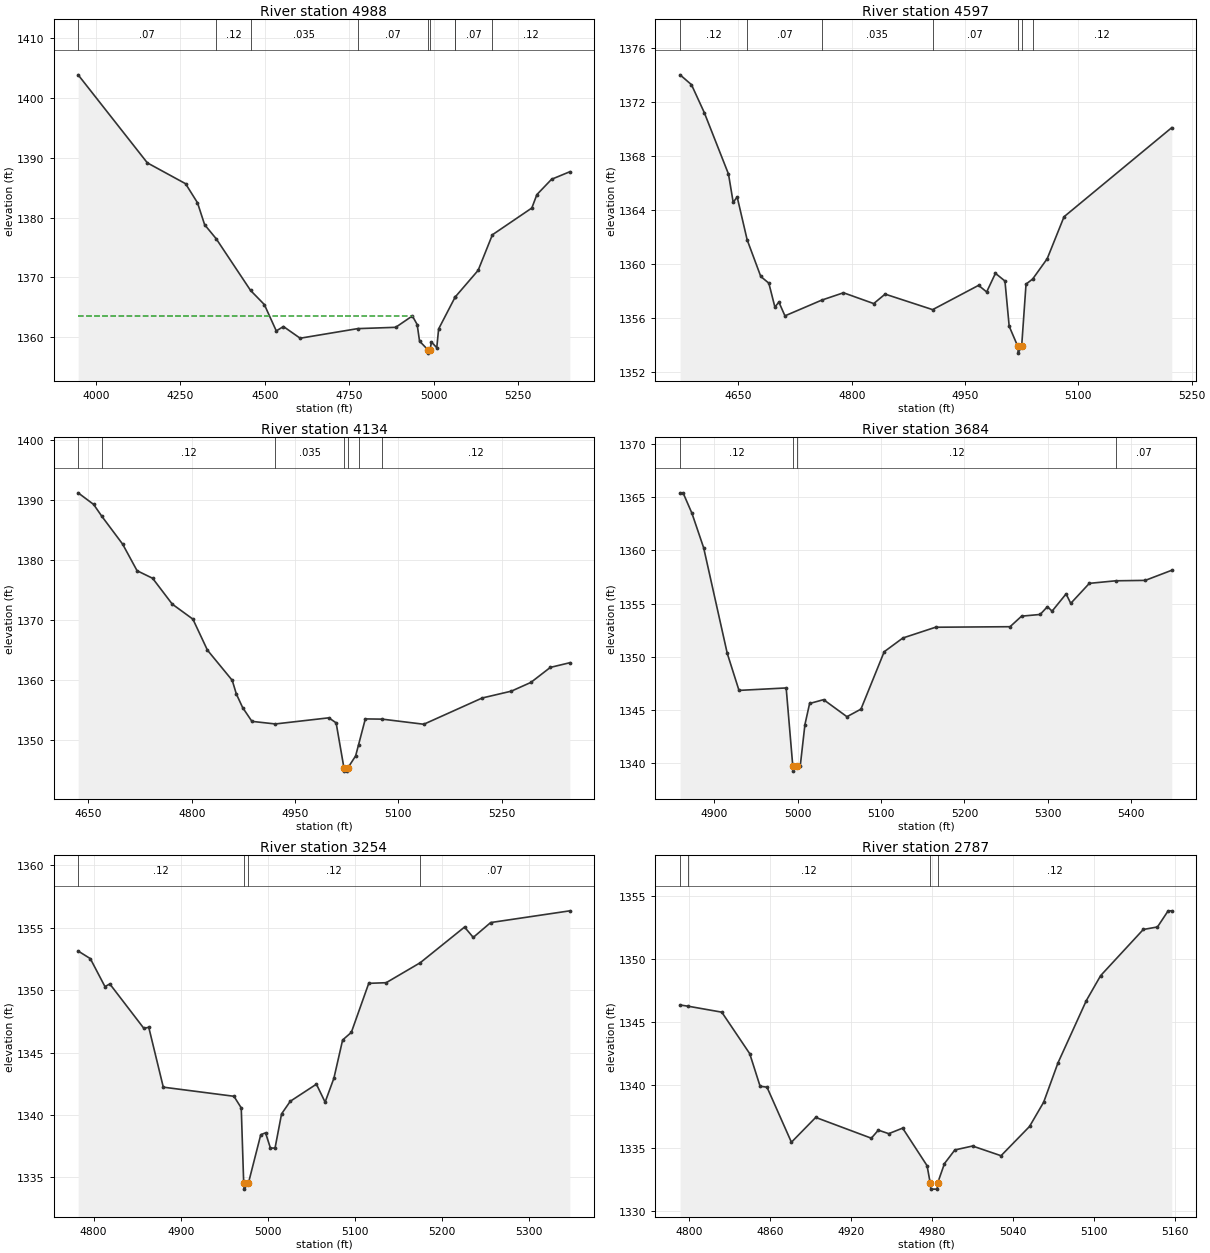
Type RM Length L Ch R = 1 ,4988    ,391,391,391
BEGIN DESCRIPTION:
Stream0184_DS 11.0
END DESCRIPTION:
XS GIS Cut Line= 3
      2114674.97     13903775.03      2113926.21     13904515.41
      2113555.27      13904673.7
#Sta/Elev= 30
    3947 1403.84    4152 1389.14  4265.2 1385.66  4300.5 1382.48  4321.7 1378.81
  4355.9 1376.47  4457.7 1367.84  4498.5 1365.48  4533.9 1361.08  4555.1 1361.81
  4604.6 1359.86  4774.8 1361.46  4887.5 1361.68  4936.9 1363.58  4951.1 1362.15
  4958.2 1359.37  4983.9 1357.87  4984.3 1357.37    4989 1357.87  4993.5 1359.22
  5009.2 1358.28  5014.7 1361.41  5063.7 1366.74  5064.5 1366.79  5131.8  1371.2
  5173.9 1377.13  5290.7  1381.6  5305.7 1383.84  5349.2  1386.4  5403.3 1387.66
#Mann= 9 ,-1 , 0
    3947     .07       0  4355.9     .12       0  4457.7    .035       0
  4774.8     .07       0  4983.9     .05       0    4989     .07       0
  5063.7    .035       0  5064.5     .07       0  5173.9     .12       0
#XS Ineff= 2 , 0
       0 4938.02 1363.63               0
Permanent Ineff=
       F       F
Bank Sta=4983.9,4989
XS Rating Curve= 0 ,0
Exp/Cntr=0.3,0.1

Type RM Length L Ch R = 1 ,4597    ,463,463,463
BEGIN DESCRIPTION:
Stream0184_DS 10.0
END DESCRIPTION:
XS GIS Cut Line= 3
      2114324.98     13903975.01        2113925.       13904125.
      2113724.99       13904225.
#Sta/Elev= 30
  4572.8    1374  4587.9 1373.27  4604.8 1371.21  4636.9 1366.65  4643.1 1364.56
  4648.4 1364.95  4661.6 1361.78  4679.6 1359.07  4690.3 1358.57  4698.3  1356.8
  4703.6 1357.17  4711.6 1356.15  4760.5 1357.32  4789.1 1357.86  4829.1 1357.06
  4844.2 1357.76  4907.1 1356.61  4967.9 1358.41  4978.6 1357.92  4990.2  1359.3
  5002.8 1358.73  5008.4 1355.38  5019.8 1353.89  5020.2 1353.39  5024.9 1353.89
  5030.7  1358.5  5039.5 1358.88  5058.7 1360.38    5081 1363.49  5223.6 1370.09
#Mann= 7 ,-1 , 0
  4572.8     .12       0  4661.6     .07       0  4760.5    .035       0
  4907.1     .07       0  5019.8     .05       0  5024.9     .07       0
  5039.5     .12       0
Bank Sta=5019.8,5024.9
XS Rating Curve= 0 ,0
Exp/Cntr=0.3,0.1

Type RM Length L Ch R = 1 ,4134    ,450,450,450
BEGIN DESCRIPTION:
Stream0184_DS 9.0
END DESCRIPTION:
XS GIS Cut Line= 3
      2114274.99       13903475.        2113975.       13903675.
        2113725.       13903925.
#Sta/Elev= 30
    4635 1391.16  4657.5 1389.23  4669.6 1387.23  4699.6 1382.63  4720.6  1378.2
  4743.2 1376.94  4771.7 1372.64  4801.7 1370.14  4822.8 1364.98  4858.8 1359.96
  4864.8 1357.68  4873.9 1355.43  4887.4 1353.13  4921.4  1352.7  4999.1 1353.72
  5009.7 1352.88  5021.1 1345.35  5021.6 1344.85  5026.1 1344.85  5026.5 1345.35
    5038 1347.38  5042.2 1349.21  5052.1 1353.54  5076.7  1353.5    5137 1352.65
  5221.8 1357.02  5264.2 1358.16  5292.5 1359.61  5320.8 1362.11  5349.1 1362.89
#Mann= 7 ,-1 , 0
    4635     .07       0  4669.6     .12       0  4921.4    .035       0
  5021.1    .035       0  5026.5    .035       0  5042.2     .07       0
  5076.7     .12       0
Bank Sta=5021.1,5026.5
XS Rating Curve= 0 ,0
Exp/Cntr=0.3,0.1

Type RM Length L Ch R = 1 ,3684    ,430,430,430
BEGIN DESCRIPTION:
Stream0184_DS 8.0
END DESCRIPTION:
XS GIS Cut Line= 3
      2113825.02     13903224.98        2113725.       13903325.
      2113524.74     13903726.25
#Sta/Elev= 30
  4858.8 1365.41  4862.4 1365.41    4873  1363.5  4887.1 1360.25  4915.4 1350.34
  4929.5 1346.86  4986.1 1347.09    4994 1339.78  4994.4 1339.28  4999.4 1339.78
    5003 1339.78  5008.6 1343.65  5014.2 1345.63    5031 1345.99    5059 1344.39
  5075.8  1345.1  5103.7 1350.49  5126.1 1351.78  5165.3 1352.79  5254.7 1352.84
  5268.5 1353.83  5290.8 1353.99  5299.5 1354.72  5305.1  1354.3  5321.9 1355.92
  5327.5 1355.03  5349.8 1356.91  5381.4 1357.15  5416.9 1357.19  5448.7 1358.14
#Mann= 4 ,-1 , 0
  4858.8     .12       0    4994     .05       0  4999.4     .12       0
  5381.4     .07       0
Bank Sta=4994,4999.4
XS Rating Curve= 0 ,0
Exp/Cntr=0.3,0.1

Type RM Length L Ch R = 1 ,3254    ,467,467,467
BEGIN DESCRIPTION:
Stream0184_DS 7.0
END DESCRIPTION:
XS GIS Cut Line= 3
      2113274.99     13903174.98        2113375.       13903375.
      2113365.87     13903715.85
#Sta/Elev= 30
  4782.3 1353.14  4796.3 1352.53  4813.1 1350.29  4818.7  1350.5  4857.8 1346.94
  4863.4 1347.03  4880.1 1342.23  4961.2  1341.5  4969.6 1340.57  4972.4 1334.56
  4972.9 1334.06  4977.9 1334.56    4992 1338.42  4997.5 1338.57  5003.1 1337.35
  5008.4 1337.35  5015.9 1340.09  5025.9  1341.1  5055.9 1342.47  5065.9 1341.03
    5076 1342.95    5086 1346.01    5096 1346.62    5116 1350.55    5136  1350.6
  5175.1  1352.2    5226 1355.06    5236 1354.23    5256 1355.42  5346.9 1356.36
#Mann= 4 ,-1 , 0
  4782.3     .12       0  4972.4     .05       0  4977.9     .12       0
  5175.1     .07       0
Bank Sta=4972.4,4977.9
XS Rating Curve= 0 ,0
Exp/Cntr=0.3,0.1

Type RM Length L Ch R = 1 ,2787    ,361,361,361
BEGIN DESCRIPTION:
Stream0184_DS 6.0
END DESCRIPTION:
XS GIS Cut Line= 3
        2113025.     13903274.99        2112975.       13903475.
      2112924.99     13903625.02
#Sta/Elev= 30
  4793.4 1346.37  4799.5 1346.27  4824.3  1345.8    4845 1342.51  4852.7 1339.92
  4857.8 1339.85  4875.9 1335.48  4893.9 1337.45  4935.1  1335.8  4940.3 1336.44
    4948 1336.16  4958.3  1336.6  4976.4 1333.62  4978.7 1332.26  4979.2 1331.76
  4983.9 1331.76  4984.3 1332.26  4989.3 1333.79    4997 1334.87  5010.1 1335.18
  5031.2 1334.41  5052.3 1336.73  5062.8 1338.66  5073.4 1341.78  5094.4 1346.72
    5105  1348.7  5136.6 1352.36  5147.1 1352.56    5155 1353.84  5157.7 1353.84
#Mann= 4 ,-1 , 0
  4793.4    .035       0  4799.5     .12       0  4978.7     .05       0
  4984.3     .12       0
Bank Sta=4978.7,4984.3
XS Rating Curve= 0 ,0
Exp/Cntr=0.3,0.1

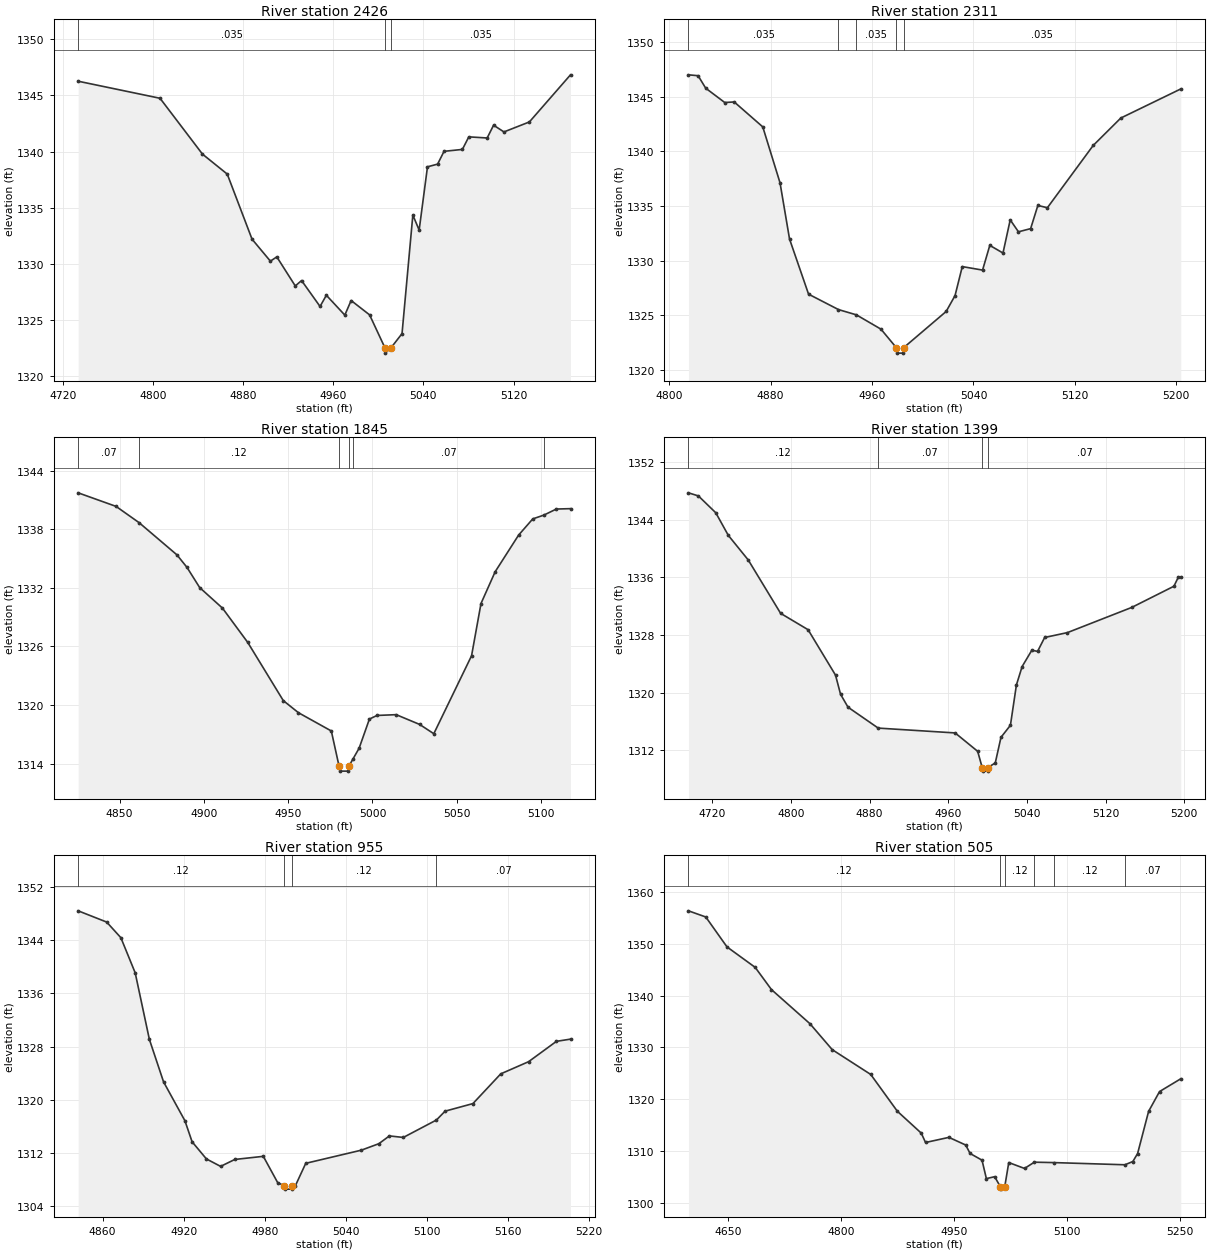
Type RM Length L Ch R = 1 ,2426    ,115,115,115
BEGIN DESCRIPTION:
Stream0184_DS 5.5
END DESCRIPTION:
XS GIS Cut Line= 2
      2112909.31     13903199.37      2112522.72     13903403.56
#Sta/Elev= 30
  4733.4 1346.27  4806.1 1344.75  4843.8 1339.77  4865.8 1337.99  4887.8 1332.19
  4904.1 1330.23  4909.8 1330.61  4926.2 1328.02  4931.8  1328.5  4948.2 1326.19
  4953.8 1327.19  4970.2 1325.42  4975.8 1326.72  4992.2 1325.44  5005.7 1322.53
  5006.2 1322.03  5011.4 1322.53    5021 1323.77  5030.6 1334.34  5036.2    1333
  5043.6 1338.64  5052.6 1338.88  5058.3 1340.02  5074.6 1340.19  5080.3 1341.31
  5096.6 1341.21  5102.3 1342.35  5111.5 1341.75  5134.1 1342.64  5170.6 1346.84
#Mann= 3 ,-1 , 0
  4733.4    .035       0  5005.7    .035       0  5011.4    .035       0
Bank Sta=5005.7,5011.4
XS Rating Curve= 0 ,0
Exp/Cntr=0.3,0.1

Type RM Length L Ch R = 1 ,2311    ,466,466,466
BEGIN DESCRIPTION:
Stream0184_DS 5.0
END DESCRIPTION:
XS GIS Cut Line= 3
      2112775.04     13903124.97        2112625.       13903225.
      2112442.87      13903325.2
#Sta/Elev= 30
  4815.3 1346.99  4822.9 1346.91  4828.9 1345.77  4843.9 1344.46  4851.4 1344.51
  4873.9 1342.23  4887.5 1337.12    4895 1331.98    4910 1326.94  4933.6 1325.53
  4947.7 1325.05  4967.1 1323.74  4979.2 1322.05  4979.7 1321.55  4984.5 1321.55
    4985 1322.05  5018.5 1325.36  5025.5 1326.81  5031.2 1329.46  5047.2 1329.14
  5052.9  1331.4  5063.3  1330.7    5069 1333.73  5075.5 1332.64  5085.1 1332.93
  5090.8 1335.05  5098.3 1334.84  5134.4 1340.53  5156.2 1343.04  5203.5  1345.7
#Mann= 5 ,-1 , 0
  4815.3    .035       0  4933.6     .07       0  4947.7    .035       0
  4979.2    .035       0    4985    .035       0
Bank Sta=4979.2,4985
XS Rating Curve= 0 ,0
Exp/Cntr=0.3,0.1

Type RM Length L Ch R = 1 ,1845    ,446,446,446
BEGIN DESCRIPTION:
Stream0184_DS 4.0
END DESCRIPTION:
XS GIS Cut Line= 3
      2112424.99       13902875.        2112275.       13902975.
      2112174.98     13903025.01
#Sta/Elev= 30
  4825.4 1341.72  4847.9 1340.33  4861.6 1338.66    4884 1335.37    4890 1334.08
  4897.5 1332.02    4911 1329.92    4926 1326.41  4947.1 1320.45  4956.1 1319.21
  4975.6 1317.34  4980.2 1313.73  4980.7 1313.23  4985.6 1313.23    4986 1313.73
  4988.5 1314.49  4992.1 1315.58  4998.2 1318.56  5002.7 1318.93  5014.1 1319.01
    5028 1318.01  5036.4 1317.06  5058.8 1325.04  5064.4 1330.39  5072.8 1333.64
  5086.7 1337.39  5095.1 1339.05  5101.7 1339.44  5109.1 1340.06  5117.5  1340.1
#Mann= 6 ,-1 , 0
  4825.4     .07       0  4861.6     .12       0  4980.2     .05       0
    4986     .12       0  4988.5     .07       0  5101.7    .035       0
Bank Sta=4980.2,4986
XS Rating Curve= 0 ,0
Exp/Cntr=0.3,0.1

Type RM Length L Ch R = 1 ,1399    ,444,444,444
BEGIN DESCRIPTION:
Stream0184_DS 3.0
END DESCRIPTION:
XS GIS Cut Line= 3
      2112024.99     13902375.04        2111975.       13902675.
      2111875.44      13902844.3
#Sta/Elev= 30
  4695.9 1347.73    4706  1347.3  4723.7 1344.96  4736.4 1341.83  4756.7 1338.41
  4789.6 1331.01  4817.5 1328.74  4845.4 1322.44  4850.5 1319.79  4858.1 1317.99
  4888.8 1315.09    4967 1314.42  4989.9 1311.87  4994.5 1309.62    4995 1309.12
  4999.9 1309.12  5000.4 1309.62  5007.8 1310.26  5013.6 1313.81  5023.2 1315.48
  5029.3 1321.08  5035.1 1323.63    5045  1325.9  5050.8 1325.73    5058 1327.66
  5081.2 1328.34  5146.5 1331.83  5189.4 1334.77  5193.9 1336.03  5196.4 1336.03
#Mann= 4 ,-1 , 0
  4695.9     .12       0  4888.8     .07       0  4994.5     .05       0
  5000.4     .07       0
Bank Sta=4994.5,5000.4
XS Rating Curve= 0 ,0
Exp/Cntr=0.3,0.1

Type RM Length L Ch R = 1 ,955     ,450,450,450
BEGIN DESCRIPTION:
Stream0184_DS 2.0
END DESCRIPTION:
XS GIS Cut Line= 3
        2111725.     13902225.01        2111675.       13902375.
      2111624.99     13902575.04
#Sta/Elev= 30
  4841.9  1348.4    4863 1346.71  4873.5 1344.36  4884.1 1339.08  4894.6 1329.07
  4905.1 1322.68  4920.9 1316.84  4926.2 1313.68  4936.8  1311.1  4947.3 1309.98
  4957.8 1311.02  4978.9 1311.49  4989.5 1307.55  4994.4 1307.06  4994.9 1306.56
  4999.8 1306.56  5000.3 1307.06  5002.6 1307.06  5010.3 1310.44  5051.5 1312.42
  5064.4 1313.39  5072.2 1314.56  5082.5 1314.33    5107 1316.95  5113.4 1318.28
    5134 1319.42  5154.6 1323.89  5175.2 1325.72  5195.8 1328.78  5206.2 1329.11
#Mann= 4 ,-1 , 0
  4841.9     .12       0  4994.4     .05       0  5000.3     .12       0
    5107     .07       0
Bank Sta=4994.4,5000.3
XS Rating Curve= 0 ,0
Exp/Cntr=0.3,0.1

Type RM Length L Ch R = 1 ,505     ,0,0,0
BEGIN DESCRIPTION:
Stream0184_DS 1.0
END DESCRIPTION:
XS GIS Cut Line= 3
      2111624.97     13902025.02        2111275.       13902225.
      2111124.98     13902425.02
#Sta/Elev= 30
  4597.7 1356.36  4620.7 1355.17  4648.8  1349.4  4686.2 1345.45  4707.8 1341.16
  4758.9 1334.57  4788.4 1329.57  4839.5 1324.78  4874.8 1317.68  4906.5 1313.46
  4912.2 1311.65  4943.2 1312.64  4965.5 1311.16  4971.3 1309.53  4987.1 1308.24
  4992.9 1304.68  5003.9 1305.05  5011.3 1303.15  5011.8 1302.65  5017.3 1303.15
  5022.6 1307.78  5043.5 1306.64  5056.5 1307.85  5082.8 1307.77  5176.7 1307.35
  5187.2 1307.98  5193.5 1309.52  5208.1 1317.66  5222.6 1321.48  5250.8 1323.95
#Mann= 6 ,-1 , 0
  4597.7     .12       0  5011.3     .05       0  5017.3     .12       0
  5056.5     .07       0  5082.8     .12       0  5176.7     .07       0
Bank Sta=5011.3,5017.3
XS Rating Curve= 0 ,0
Exp/Cntr=0.3,0.1

Chan Stop Cuts=-1
Use User Specified Reach Order=0
Composite Channel Slope=5