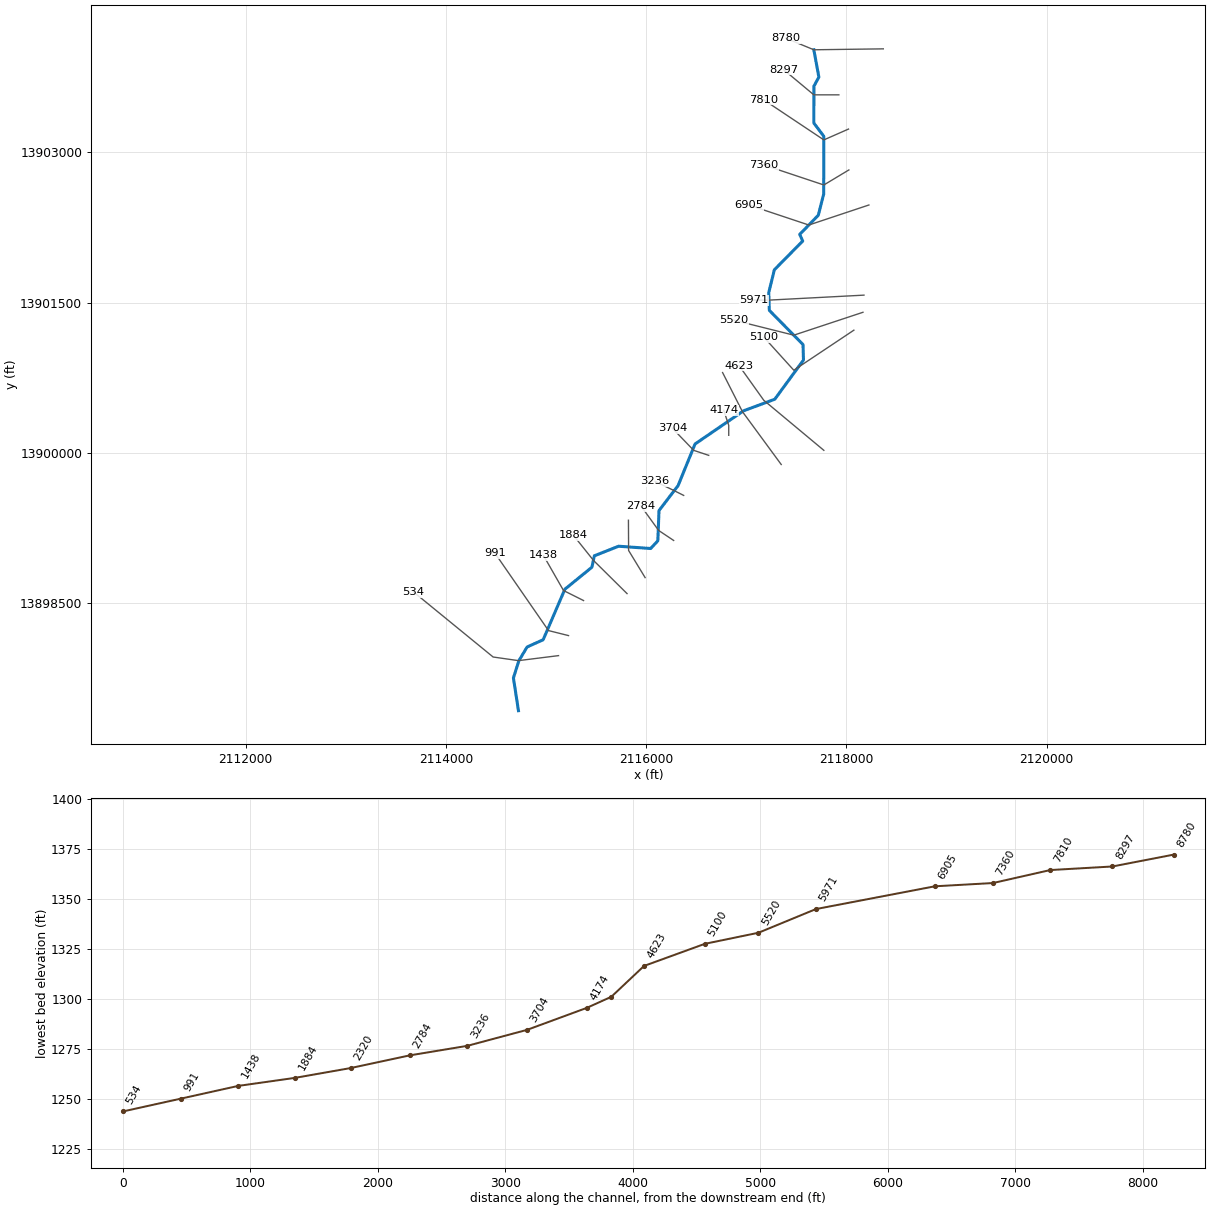
--- Stream0185_DS.prj (project) ---

Proj Title=Stream0185_DS Base Level Engineering
Current Plan=p01
Default Exp/Contr=0.3,0.1
English Units
Geom File=g01
Flow File=f01
Plan File=p01
BEGIN DESCRIPTION:
Stream0185_DS
END DESCRIPTION:

--- Stream0185_DS.p01 (plan) ---

Plan Title=Multiple Run
Short Identifier=Multiple
Geom File=g01
Flow File=f01
Subcritical Flow
K Sum by GR= 0
Std Step Tol= 0.01
Critical Tol= 0.01
Num of Std Step Trials= 20
Max Error Tol= 0.3
Flow Tol Ratio= 0.001
Split Flow NTrial= 30
Split Flow Tol= 0.02
Split Flow Ratio= 0.02
Log Output Level= 0
Friction Slope Method= 1
Unsteady Friction Slope Method= 2
Unsteady Bridges Friction Slope Method= 1
Parabolic Critical Depth
Global Vel Dist=  1 , 1 , 1
Global Log Level= 0
CheckData=True
Encroach Param= -1, 0, 0, 0
BEGIN DESCRIPTION:
Multiple Run
END DESCRIPTION:

--- Stream0185_DS.f01 (steady flow) ---

Flow Title=Multiple
Number of Profiles=7
Profile Names=10-year,25-year,50-year,1pct_min,100-year,1pct_plu,500-year
River Rch & RM= Stream0185_DS,Reach-1,8780
     997    1681    2330    1567    3127    6239    5564
River Rch & RM= Stream0185_DS,Reach-1,8297
    1358    2329    3264    2216    4421    8820    8022
River Rch & RM= Stream0185_DS,Reach-1,3704
    1857    3235    4580    3138    6260   12491   11576
Boundary for River Rch & Prof#=Stream0185_DS,Reach-1,1
Up Type=0
Dn Type=3
Dn Slope=0.005
Boundary for River Rch & Prof#=Stream0185_DS,Reach-1,2
Up Type=0
Dn Type=3
Dn Slope=0.005
Boundary for River Rch & Prof#=Stream0185_DS,Reach-1,3
Up Type=0
Dn Type=3
Dn Slope=0.005
Boundary for River Rch & Prof#=Stream0185_DS,Reach-1,4
Up Type=0
Dn Type=3
Dn Slope=0.005
Boundary for River Rch & Prof#=Stream0185_DS,Reach-1,5
Up Type=0
Dn Type=3
Dn Slope=0.005
Boundary for River Rch & Prof#=Stream0185_DS,Reach-1,6
Up Type=0
Dn Type=3
Dn Slope=0.005
Boundary for River Rch & Prof#=Stream0185_DS,Reach-1,7
Up Type=0
Dn Type=3
Dn Slope=0.005

--- Stream0185_DS.g01 (geometry) ---

Geom Title=Existing Conditions

River Reach=Stream0185_DS,Reach-1
Reach XY= 30
      2117675.00     13904025.00      2117725.38     13903752.19
      2117675.70     13903661.09      2117675.09     13903293.22
      2117774.46     13903161.14      2117773.62     13902584.66
      2117719.53     13902372.55      2117534.30     13902181.67
      2117563.76     13902115.00      2117280.47     13901827.45
      2117224.80     13901600.08      2117230.46     13901422.55
      2117567.19     13901081.19      2117571.46     13900926.47
      2117285.10     13900535.39      2116972.57     13900419.48
      2116488.61     13900088.24      2116319.15     13899672.71
      2116128.55     13899423.53      2116117.01     13899121.65
      2116045.25     13899044.60      2115724.99     13899067.47
      2115482.72     13898971.81      2115458.69     13898857.90
      2115188.63     13898638.21      2114971.50     13898133.46
      2114811.43     13898061.53      2114728.82     13897923.42
      2114674.62     13897752.19      2114725.00     13897425.00

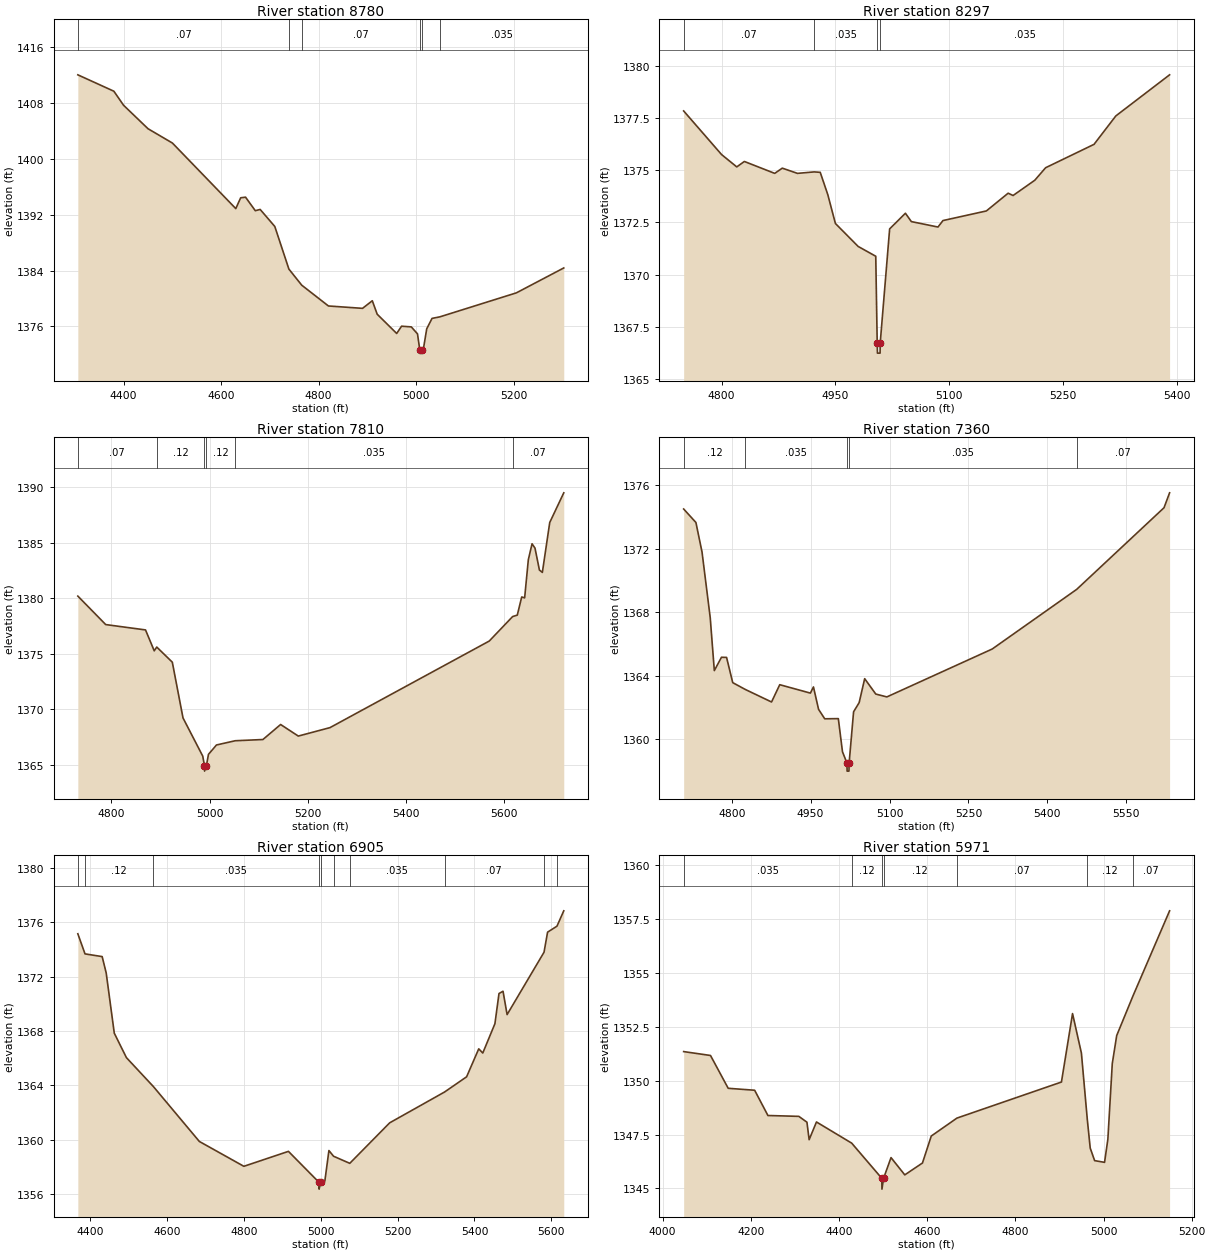
Type RM Length L Ch R = 1,8780,483,483,483
BEGIN DESCRIPTION:
Stream0185_DS 18.0
END DESCRIPTION:
XS GIS Cut Line= 3
      2118368.94     13904034.18      2117675.00     13904025.00
      2117395.20     13904140.49
#Sta/Elev= 30
  4306.0 1412.08  4379.9 1409.73  4399.9 1407.71  4450.0 1404.35  4500.0 1402.30
  4630.0 1392.90  4640.0 1394.45  4650.0 1394.54  4670.0 1392.60  4680.0 1392.78
  4710.0 1390.34  4738.9 1384.23  4765.3 1381.92  4820.0 1378.94  4890.0 1378.60
  4910.0 1379.69  4920.0 1377.76  4960.0 1375.00  4970.0 1376.04  4990.0 1375.94
  5002.7 1374.94  5007.3 1372.68  5007.5 1372.18  5011.3 1372.68  5014.7 1372.74
  5021.6 1375.66  5032.5 1377.16  5048.5 1377.38  5205.5 1380.82  5302.7 1384.39
#Mann=6,-1,0
  4306.0    0.07       0  4738.9   0.035       0  4765.3    0.07       0
  5007.3    0.05       0  5011.3    0.07       0  5048.5   0.035       0
Bank Sta=5007.3,5011.3
Exp/Cntr=0.3,0.1

Type RM Length L Ch R = 1,8297,487,487,487
BEGIN DESCRIPTION:
Stream0185_DS 17.0
END DESCRIPTION:
XS GIS Cut Line= 3
      2117924.99     13903575.00      2117675.00     13903575.00
      2117375.00     13903825.00
#Sta/Elev= 30
  4749.9 1377.84  4799.9 1375.75  4819.9 1375.16  4829.9 1375.42  4869.9 1374.85
  4879.9 1375.10  4899.9 1374.85  4921.9 1374.92  4929.9 1374.90  4939.9 1373.83
  4949.9 1372.45  4979.9 1371.35  5003.1 1370.88  5005.0 1366.74  5005.3 1366.24
  5008.8 1366.24  5009.0 1366.74  5021.4 1372.19  5042.2 1372.94  5050.0 1372.54
  5085.1 1372.28  5091.7 1372.59  5148.9 1373.05  5177.6 1373.90  5184.1 1373.79
  5212.7 1374.52  5227.0 1375.12  5290.8 1376.24  5319.5 1377.60  5390.4 1379.57
#Mann=4,-1,0
  4749.9    0.07       0  4921.9   0.035       0  5005.0   0.035       0
  5009.0   0.035       0
Bank Sta=5005,5009
Exp/Cntr=0.3,0.1

Type RM Length L Ch R = 1,7810,450,450,450
BEGIN DESCRIPTION:
Stream0185_DS 16.0
END DESCRIPTION:
XS GIS Cut Line= 3
      2118021.21     13903233.21      2117775.00     13903125.00
      2117174.96     13903525.03
#Sta/Elev= 30
  4731.5 1380.19  4788.3 1377.63  4869.4 1377.15  4887.2 1375.27  4892.3 1375.61
  4924.0 1374.25  4945.8 1369.24  4986.0 1365.81  4989.5 1364.96  4989.7 1364.46
  4993.5 1364.96  4997.7 1365.97  5014.0 1366.81  5052.2 1367.19  5108.6 1367.30
  5144.7 1368.65  5180.7 1367.61  5245.3 1368.37  5569.8 1376.15  5617.4 1378.35
  5626.9 1378.48  5635.9 1380.11  5641.9 1380.03  5649.4 1383.46  5657.0 1384.89
  5663.0 1384.50  5672.0 1382.53  5678.0 1382.32  5693.0 1386.80  5721.6 1389.47
#Mann=6,-1,0
  4731.5    0.07       0  4892.3    0.12       0  4989.5    0.05       0
  4993.5    0.12       0  5052.2   0.035       0  5617.4    0.07       0
Bank Sta=4989.5,4993.5
Exp/Cntr=0.3,0.1

Type RM Length L Ch R = 1,7360,455,455,455
BEGIN DESCRIPTION:
Stream0185_DS 15.0
END DESCRIPTION:
XS GIS Cut Line= 3
      2118024.97     13902824.98      2117775.00     13902675.00
      2117174.97     13902875.01
#Sta/Elev= 30
  4708.6 1374.50  4731.9 1373.65  4743.5 1371.79  4759.1 1367.65  4766.9 1364.31
  4780.5 1365.15  4790.2 1365.14  4801.9 1363.55  4825.8 1363.12  4875.7 1362.33
  4891.3 1363.42  4949.6 1362.89  4955.4 1363.28  4965.1 1361.87  4976.8 1361.27
  5002.7 1361.28  5010.6 1359.19  5019.2 1358.47  5019.4 1357.97  5022.9 1357.97
  5023.2 1358.47  5031.7 1361.71  5042.3 1362.29  5052.8 1363.80  5073.9 1362.83
  5095.0 1362.65  5295.3 1365.67  5455.9 1369.43  5622.0 1374.58  5632.6 1375.52
#Mann=5,-1,0
  4708.6    0.12       0  4825.8   0.035       0  5019.2   0.035       0
  5023.2   0.035       0  5455.9    0.07       0
Bank Sta=5019.2,5023.2
Exp/Cntr=0.3,0.1

Type RM Length L Ch R = 1,6905,934,934,934
BEGIN DESCRIPTION:
Stream0185_DS 14.0
END DESCRIPTION:
XS GIS Cut Line= 3
      2118225.02     13902475.01      2117625.00     13902275.00
      2117025.03     13902474.99
#Sta/Elev= 30
  4367.5 1375.15  4386.2 1373.67  4430.8 1373.47  4441.3 1372.27  4462.4 1367.83
  4494.0 1366.03  4564.2 1363.90  4683.8 1359.86  4799.7 1358.03  4915.7 1359.13
  4995.3 1356.85  4995.6 1356.35  4999.3 1356.85  5010.5 1356.95  5021.1 1359.19
  5033.2 1358.77  5075.4 1358.25  5179.2 1361.23  5322.1 1363.50  5379.5 1364.62
  5411.1 1366.68  5421.6 1366.37  5453.2 1368.53  5463.8 1370.75  5474.3 1370.92
  5484.9 1369.20  5581.0 1373.79  5590.3 1375.27  5614.7 1375.71  5632.4 1376.84
#Mann=10,-1,0
  4367.5    0.07       0  4386.2    0.12       0  4564.2   0.035       0
  4995.3   0.035       0  4999.3   0.035       0  5033.2    0.07       0
  5075.4   0.035       0  5322.1    0.07       0  5581.0   0.035       0
  5614.7    0.07       0
Bank Sta=4995.3,4999.3
Exp/Cntr=0.3,0.1

Type RM Length L Ch R = 1,5971,451,451,451
BEGIN DESCRIPTION:
Stream0185_DS 13.0
END DESCRIPTION:
XS GIS Cut Line= 3
      2118175.83     13901574.80      2117225.00     13901525.00
      2117075.03     13901525.00
#Sta/Elev= 30
  4047.7 1351.34  4108.6 1351.16  4148.7 1349.64  4208.7 1349.55  4238.8 1348.38
  4308.9 1348.34  4327.3 1348.07  4332.3 1347.26  4348.9 1348.08  4428.8 1347.10
  4497.1 1345.47  4497.4 1344.97  4501.1 1345.47  4518.0 1346.43  4549.2 1345.63
  4589.3 1346.18  4609.3 1347.43  4667.5 1348.26  4904.5 1349.93  4929.7 1353.10
  4949.8 1351.27  4963.1 1348.21  4969.8 1346.87  4979.8 1346.29  5002.3 1346.21
  5009.8 1347.28  5019.8 1350.78  5029.8 1352.08  5066.8 1353.92  5149.8 1357.86
#Mann=7,-1,0
  4047.7   0.035       0  4428.8    0.12       0  4497.1    0.05       0
  4501.1    0.12       0  4667.5    0.07       0  4963.1    0.12       0
  5066.8    0.07       0
Bank Sta=4497.1,4501.1
Exp/Cntr=0.3,0.1

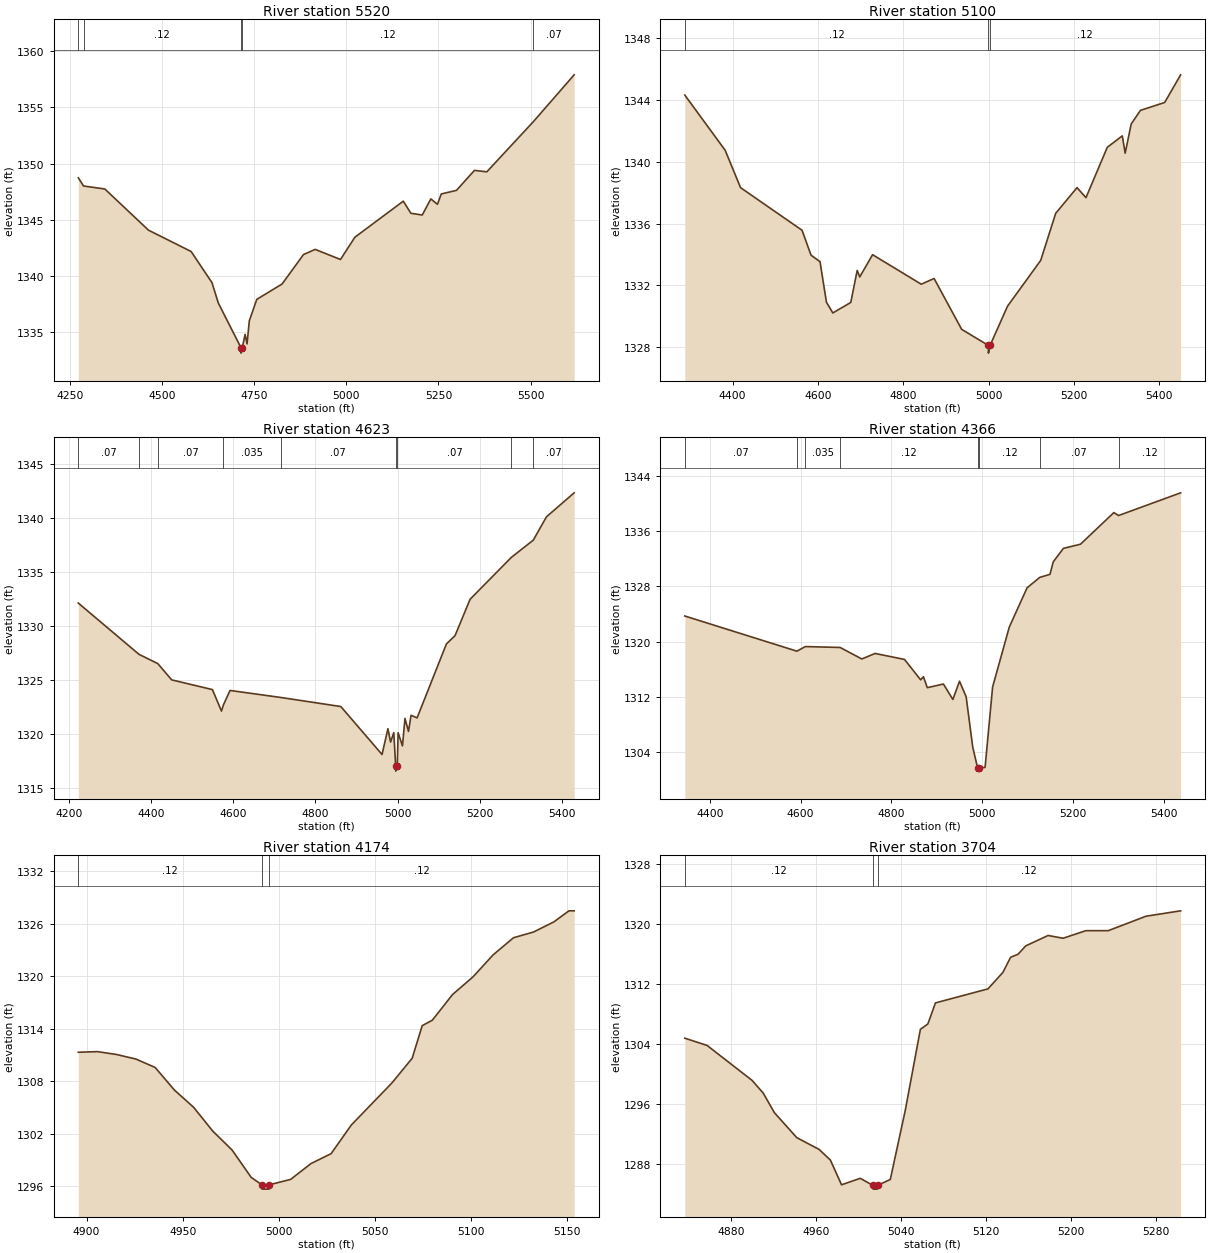
Type RM Length L Ch R = 1,5520,420,420,420
BEGIN DESCRIPTION:
Stream0185_DS 12.0
END DESCRIPTION:
XS GIS Cut Line= 3
      2118165.72     13901403.56      2117475.00     13901175.00
      2116875.01     13901325.00
#Sta/Elev= 30
  4272.5 1348.74  4286.7 1348.01  4344.6 1347.74  4462.9 1344.08  4578.7 1342.18
  4635.3 1339.41  4652.5 1337.60  4713.7 1333.64  4713.9 1333.14  4717.7 1333.64
  4725.2 1334.81  4730.5 1333.96  4736.7 1336.02  4756.9 1337.92  4825.6 1339.29
  4883.8 1341.91  4915.5 1342.37  4984.2 1341.47  5023.2 1343.45  5154.7 1346.66
  5175.3 1345.58  5206.2 1345.43  5229.4 1346.86  5247.4 1346.38  5257.7 1347.30
  5299.0 1347.62  5347.9 1349.40  5381.4 1349.27  5507.7 1353.73  5618.5 1357.90
#Mann=5,-1,0
  4272.5   0.035       0  4286.7    0.12       0  4713.7    0.05       0
  4717.7    0.12       0  5507.7    0.07       0
Bank Sta=4713.7,4717.7
Exp/Cntr=0.3,0.1

Type RM Length L Ch R = 1,5100,477,477,477
BEGIN DESCRIPTION:
Stream0185_DS 11.0
END DESCRIPTION:
XS GIS Cut Line= 3
      2118074.99     13901224.99      2117475.00     13900825.00
      2117178.77     13901151.97
#Sta/Elev= 30
  4288.0 1344.32  4382.6 1340.75  4418.7 1338.33  4562.9 1335.57  4583.9 1333.96
  4605.0 1333.54  4620.0 1330.92  4635.0 1330.22  4677.1 1330.90  4692.1 1332.97
  4698.1 1332.55  4728.2 1333.99  4842.3 1332.08  4872.4 1332.45  4937.0 1329.16
  4999.6 1328.12  4999.8 1327.62  5003.6 1328.12  5044.6 1330.66  5122.3 1333.62
  5157.5 1336.67  5207.5 1338.33  5228.4 1337.68  5278.4 1340.94  5313.6 1341.68
  5320.3 1340.56  5334.5 1342.45  5356.1 1343.33  5412.9 1343.84  5450.3 1345.63
#Mann=3,-1,0
  4288.0    0.12       0  4999.6    0.05       0  5003.6    0.12       0
Bank Sta=4999.6,5003.6
Exp/Cntr=0.3,0.1

Type RM Length L Ch R = 1,4623,257,257,257
BEGIN DESCRIPTION:
Stream0185_DS 10.0
END DESCRIPTION:
XS GIS Cut Line= 3
      2117774.99     13900025.01      2117175.00     13900525.00
      2116928.27     13900871.04
#Sta/Elev= 30
  4223.6 1332.14  4371.3 1327.39  4416.8 1326.54  4450.7 1325.03  4549.7 1324.13
  4571.8 1322.14  4576.6 1322.72  4592.6 1324.05  4716.1 1323.40  4862.1 1322.56
  4962.3 1318.12  4976.6 1320.51  4983.1 1319.27  4990.9 1320.15  4995.4 1317.08
  4995.7 1316.58  4999.4 1317.08  5001.4 1320.14  5012.0 1318.92  5018.1 1321.46
  5026.7 1320.26  5032.9 1321.75  5047.6 1321.51  5118.9 1328.36  5139.8 1329.12
  5176.6 1332.50  5276.8 1336.37  5330.2 1337.97  5362.3 1340.13  5429.6 1342.35
#Mann=9,-1,0
  4223.6    0.07       0  4371.3   0.035       0  4416.8    0.07       0
  4576.6   0.035       0  4716.1    0.07       0  4995.4    0.05       0
  4999.4    0.07       0  5276.8    0.12       0  5330.2    0.07       0
Bank Sta=4995.4,4999.4
Exp/Cntr=0.3,0.1

Type RM Length L Ch R = 1,4366,192,192,192
BEGIN DESCRIPTION:
Stream0185_DS 9.5
END DESCRIPTION:
XS GIS Cut Line= 3
      2117349.31     13899883.48      2116961.70     13900411.59
      2116763.63     13900801.69
#Sta/Elev= 30
  4344.9 1323.71  4592.0 1318.60  4610.5 1319.27  4687.2 1319.14  4735.0 1317.47
  4764.3 1318.27  4829.1 1317.40  4864.6 1314.44  4870.8 1314.89  4879.3 1313.30
  4914.8 1313.83  4935.6 1311.59  4950.3 1314.24  4964.9 1311.98  4979.4 1304.67
  4990.0 1301.68  4990.2 1301.18  4994.0 1301.68  5006.6 1301.72  5023.2 1313.40
  5059.9 1322.09  5099.1 1327.80  5127.2 1329.32  5149.6 1329.76  5156.8 1331.57
  5179.1 1333.53  5216.9 1334.14  5290.4 1338.73  5300.7 1338.30  5437.5 1341.60
#Mann=8,-1,0
  4344.9    0.07       0  4592.0    0.12       0  4610.5   0.035       0
  4687.2    0.12       0  4990.0    0.05       0  4994.0    0.12       0
  5127.2    0.07       0  5300.7    0.12       0
Bank Sta=4990,4994
Exp/Cntr=0.3,0.1

Type RM Length L Ch R = 1,4174,470,470,470
BEGIN DESCRIPTION:
Stream0185_DS 9.0
END DESCRIPTION:
XS GIS Cut Line= 3
      2116825.00     13900175.03      2116825.00     13900275.00
      2116775.00     13900425.01
#Sta/Elev= 30
  4895.7 1311.29  4905.7 1311.36  4915.7 1311.03  4925.7 1310.51  4935.7 1309.55
  4945.7 1306.97  4955.7 1305.00  4965.7 1302.27  4975.7 1300.12  4985.7 1296.98
  4991.2 1296.14  4991.4 1295.64  4994.9 1295.64  4995.2 1296.14  5006.2 1296.75
  5016.8 1298.56  5027.3 1299.70  5037.8 1302.97  5058.9 1307.77  5069.5 1310.61
  5074.7 1314.33  5080.0 1314.96  5090.5 1317.89  5101.1 1319.90  5111.6 1322.42
  5122.2 1324.38  5132.7 1325.04  5143.2 1326.19  5151.1 1327.46  5153.8 1327.46
#Mann=3,-1,0
  4895.7    0.12       0  4991.2    0.05       0  4995.2    0.12       0
Bank Sta=4991.2,4995.2
Exp/Cntr=0.3,0.1

Type RM Length L Ch R = 1,3704,468,468,468
BEGIN DESCRIPTION:
Stream0185_DS 8.0
END DESCRIPTION:
XS GIS Cut Line= 3
      2116624.96     13899975.01      2116475.00     13900025.00
      2116260.84     13900247.10
#Sta/Elev= 30
  4836.8 1304.79  4857.8 1303.82  4900.0 1299.17  4910.5 1297.48  4921.1 1294.85
  4942.2 1291.51  4963.2 1289.94  4973.8 1288.52  4984.3 1285.22  5001.9 1286.08
  5013.9 1285.14  5014.2 1284.64  5017.9 1284.64  5018.2 1285.14  5030.2 1285.93
  5044.4 1295.24  5058.5 1305.97  5065.5 1306.68  5072.7 1309.50  5122.1 1311.37
  5136.2 1313.58  5143.4 1315.59  5150.4 1315.99  5157.6 1317.11  5178.7 1318.50
  5192.8 1318.13  5214.2 1319.14  5235.3 1319.14  5270.8 1321.07  5303.4 1321.79
#Mann=3,-1,0
  4836.8    0.12       0  5013.9    0.05       0  5018.2    0.12       0
Bank Sta=5013.9,5018.2
Exp/Cntr=0.3,0.1

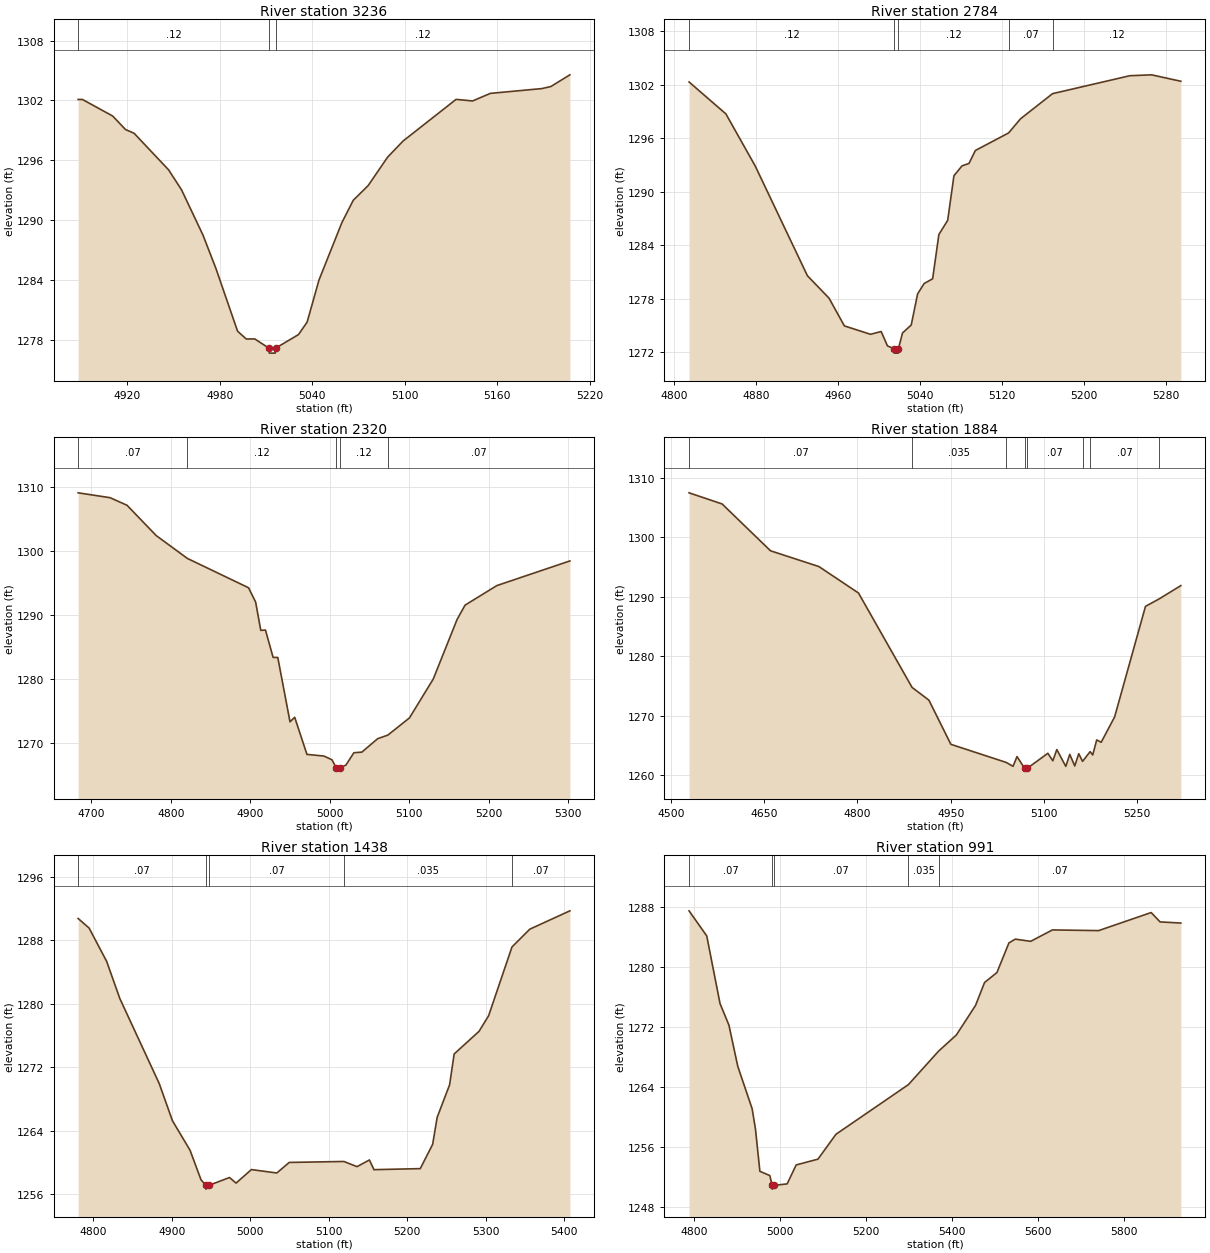
Type RM Length L Ch R = 1,3236,452,452,452
BEGIN DESCRIPTION:
Stream0185_DS 7.0
END DESCRIPTION:
XS GIS Cut Line= 3
      2116374.99     13899575.00      2116275.00     13899625.00
      2116088.57     13899715.21
#Sta/Elev= 30
  4888.2 1302.10  4891.0 1302.10  4910.6 1300.44  4918.9 1299.09  4924.5 1298.71
  4946.9 1295.04  4955.3 1293.03  4969.2 1288.49  4977.6 1285.14  4991.6 1278.87
  4997.2 1278.09  5002.8 1278.09  5011.9 1277.17  5012.2 1276.67  5016.0 1276.67
  5016.3 1277.17  5031.1 1278.53  5036.7 1279.78  5044.4 1284.00  5059.2 1289.74
  5066.6 1291.99  5076.3 1293.47  5088.9 1296.32  5098.9 1297.93  5133.3 1302.11
  5144.0 1301.95  5155.5 1302.71  5188.9 1303.19  5194.8 1303.40  5207.1 1304.57
#Mann=3,-1,0
  4888.2    0.12       0  5011.9    0.05       0  5016.3    0.12       0
Bank Sta=5011.9,5016.3
Exp/Cntr=0.3,0.1

Type RM Length L Ch R = 1,2784,464,464,464
BEGIN DESCRIPTION:
Stream0185_DS 6.0
END DESCRIPTION:
XS GIS Cut Line= 3
      2116274.97     13899125.02      2116125.00     13899225.00
      2115949.18     13899468.16
#Sta/Elev= 30
  4814.6 1302.29  4850.6 1298.71  4879.2 1292.88  4930.2 1280.58  4951.3 1278.07
  4966.3 1274.96  4991.8 1274.02  5002.2 1274.33  5008.4 1272.72  5014.7 1272.41
  5015.0 1271.91  5018.8 1271.91  5019.1 1272.41  5023.1 1274.17  5031.6 1275.06
  5037.8 1278.54  5044.2 1279.71  5052.5 1280.24  5058.6 1285.20  5067.2 1286.79
  5073.3 1291.78  5081.2 1292.89  5088.0 1293.16  5094.2 1294.61  5126.7 1296.58
  5138.3 1298.16  5169.6 1300.98  5245.1 1302.99  5266.3 1303.09  5294.9 1302.37
#Mann=5,-1,0
  4814.6    0.12       0  5014.7    0.05       0  5019.1    0.12       0
  5126.7    0.07       0  5169.6    0.12       0
Bank Sta=5014.7,5019.1
Exp/Cntr=0.3,0.1

Type RM Length L Ch R = 1,2320,436,436,436
BEGIN DESCRIPTION:
Stream0185_DS 5.0
END DESCRIPTION:
XS GIS Cut Line= 3
      2115989.98     13898754.08      2115825.00     13899025.00
      2115823.33     13899326.99
#Sta/Elev= 30
  4683.2 1309.13  4723.4 1308.37  4744.8 1307.18  4781.5 1302.44  4820.8 1298.86
  4897.8 1294.27  4906.7 1292.03  4913.2 1287.60  4919.1 1287.65  4928.7 1283.37
  4934.6 1283.36  4950.0 1273.29  4955.9 1274.00  4971.3 1268.19  4992.7 1267.93
  5002.9 1267.34  5008.2 1266.07  5008.5 1265.57  5012.7 1266.07  5020.4 1266.52
  5030.4 1268.45  5040.4 1268.54  5060.4 1270.65  5073.2 1271.21  5100.4 1273.90
  5130.4 1280.00  5160.4 1289.32  5170.4 1291.55  5210.4 1294.61  5302.4 1298.47
#Mann=5,-1,0
  4683.2    0.07       0  4820.8    0.12       0  5008.2    0.05       0
  5012.7    0.12       0  5073.2    0.07       0
Bank Sta=5008.2,5012.7
Exp/Cntr=0.3,0.1

Type RM Length L Ch R = 1,1884,446,446,446
BEGIN DESCRIPTION:
Stream0185_DS 4.0
END DESCRIPTION:
XS GIS Cut Line= 3
      2115809.42     13898594.36      2115475.00     13898925.00
      2115275.02     13899174.98
#Sta/Elev= 30
  4529.5 1307.50  4582.6 1305.63  4660.4 1297.75  4738.1 1295.10  4801.8 1290.65
  4887.9 1274.77  4915.0 1272.62  4950.3 1265.19  5039.1 1262.15  5050.2 1261.49
  5056.6 1263.13  5068.7 1261.18  5069.0 1260.68  5073.4 1261.18  5106.2 1263.68
  5114.2 1262.42  5120.6 1264.31  5135.0 1261.48  5141.4 1263.50  5149.4 1261.55
  5155.8 1263.61  5162.0 1262.32  5174.1 1263.96  5178.3 1263.40  5184.7 1265.93
  5191.9 1265.53  5213.5 1269.80  5263.1 1288.40  5285.0 1289.65  5319.9 1291.89
#Mann=8,-1,0
  4529.5    0.07       0  4887.9   0.035       0  5039.1    0.07       0
  5068.7   0.035       0  5073.4    0.07       0  5162.0    0.12       0
  5174.1    0.07       0  5285.0   0.035       0
Bank Sta=5068.7,5073.4
Exp/Cntr=0.3,0.1

Type RM Length L Ch R = 1,1438,447,447,447
BEGIN DESCRIPTION:
Stream0185_DS 3.0
END DESCRIPTION:
XS GIS Cut Line= 3
      2115375.03     13898524.99      2115175.00     13898625.00
      2114975.02     13898974.96
#Sta/Elev= 30
  4780.7 1290.73  4794.7 1289.52  4817.1 1285.32  4833.8 1280.66  4884.1 1269.94
  4900.9 1265.27  4923.3 1261.56  4937.3 1257.84  4943.3 1257.16  4943.6 1256.66
  4948.0 1257.16  4973.6 1258.12  4982.0 1257.42  5001.5 1259.12  5033.9 1258.69
  5049.7 1260.02  5119.4 1260.14  5136.1 1259.49  5151.9 1260.33  5157.7 1259.11
  5216.7 1259.24  5232.5 1262.30  5238.3 1265.71  5254.1 1269.79  5259.9 1273.67
  5291.6 1276.52  5303.8 1278.48  5333.6 1287.14  5356.3 1289.38  5407.4 1291.69
#Mann=5,-1,0
  4780.7    0.07       0  4943.3    0.05       0  4948.0    0.07       0
  5119.4   0.035       0  5333.6    0.07       0
Bank Sta=4943.3,4948
Exp/Cntr=0.3,0.1

Type RM Length L Ch R = 1,991,457,457,457
BEGIN DESCRIPTION:
Stream0185_DS 2.0
END DESCRIPTION:
XS GIS Cut Line= 3
      2115224.99     13898175.00      2115025.00     13898225.00
      2114490.87     13898997.11
#Sta/Elev= 30
  4788.3 1287.49  4829.5 1284.14  4860.4 1275.11  4881.1 1272.24  4901.7 1266.74
  4935.2 1261.06  4942.9 1258.37  4953.2 1252.72  4976.4 1252.15  4981.7 1250.84
  4982.1 1250.34  4986.5 1250.84  5016.7 1251.04  5037.7 1253.57  5088.4 1254.34
  5130.3 1257.66  5299.0 1264.29  5369.1 1268.75  5410.7 1270.92  5455.3 1274.86
  5476.3 1277.92  5505.1 1279.25  5533.1 1283.21  5547.9 1283.71  5583.7 1283.42
  5634.4 1284.94  5741.9 1284.85  5864.2 1287.26  5885.1 1286.01  5933.3 1285.86
#Mann=5,-1,0
  4788.3    0.07       0  4981.7    0.05       0  4986.5    0.07       0
  5299.0   0.035       0  5369.1    0.07       0
Bank Sta=4981.7,4986.5
Exp/Cntr=0.3,0.1

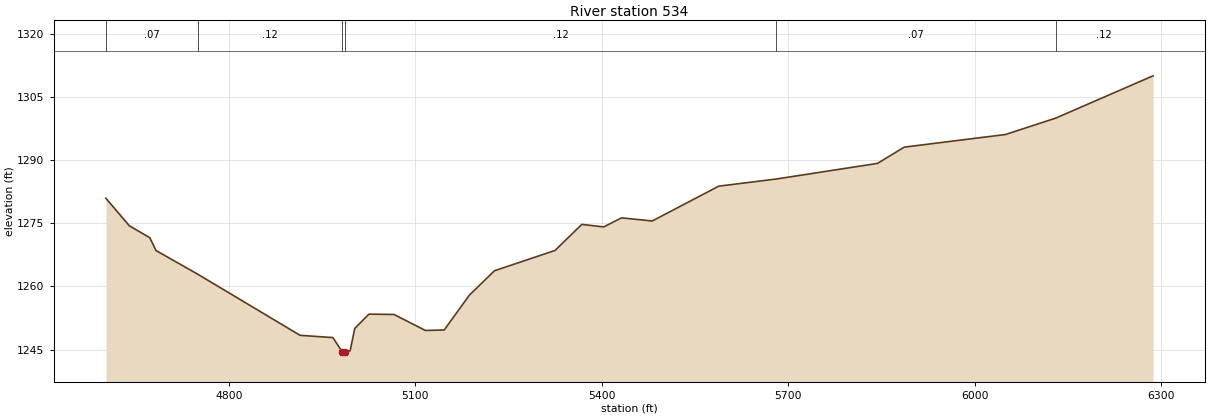
Type RM Length L Ch R = 1,534,0,0,0
BEGIN DESCRIPTION:
Stream0185_DS 1.0
END DESCRIPTION:
XS GIS Cut Line= 4
      2115125.04     13897975.01      2114725.00     13897925.00
      2114471.96     13897961.15      2113676.80     13898610.85
#Sta/Elev= 30
  4601.8 1280.94  4639.6 1274.39  4672.4 1271.58  4682.5 1268.52  4750.4 1262.83
  4914.3 1248.38  4967.2 1247.84  4982.4 1244.41  4982.8 1243.91  4987.2 1244.41
  4994.9 1244.69  5002.4 1250.01  5025.2 1253.41  5065.6 1253.33  5116.1 1249.53
  5146.4 1249.65  5186.8 1257.90  5227.2 1263.71  5324.8 1268.54  5367.9 1274.73
  5403.1 1274.13  5431.8 1276.28  5481.3 1275.54  5588.3 1283.81  5681.1 1285.51
  5843.9 1289.22  5886.9 1293.08  6049.9 1296.08  6130.6 1299.97  6287.4 1310.02
#Mann=6,-1,0
  4601.8    0.07       0  4750.4    0.12       0  4982.4    0.05       0
  4987.2    0.12       0  5681.1    0.07       0  6130.6    0.12       0
Bank Sta=4982.4,4987.2
Exp/Cntr=0.3,0.1

Chan Stop Cuts=-1