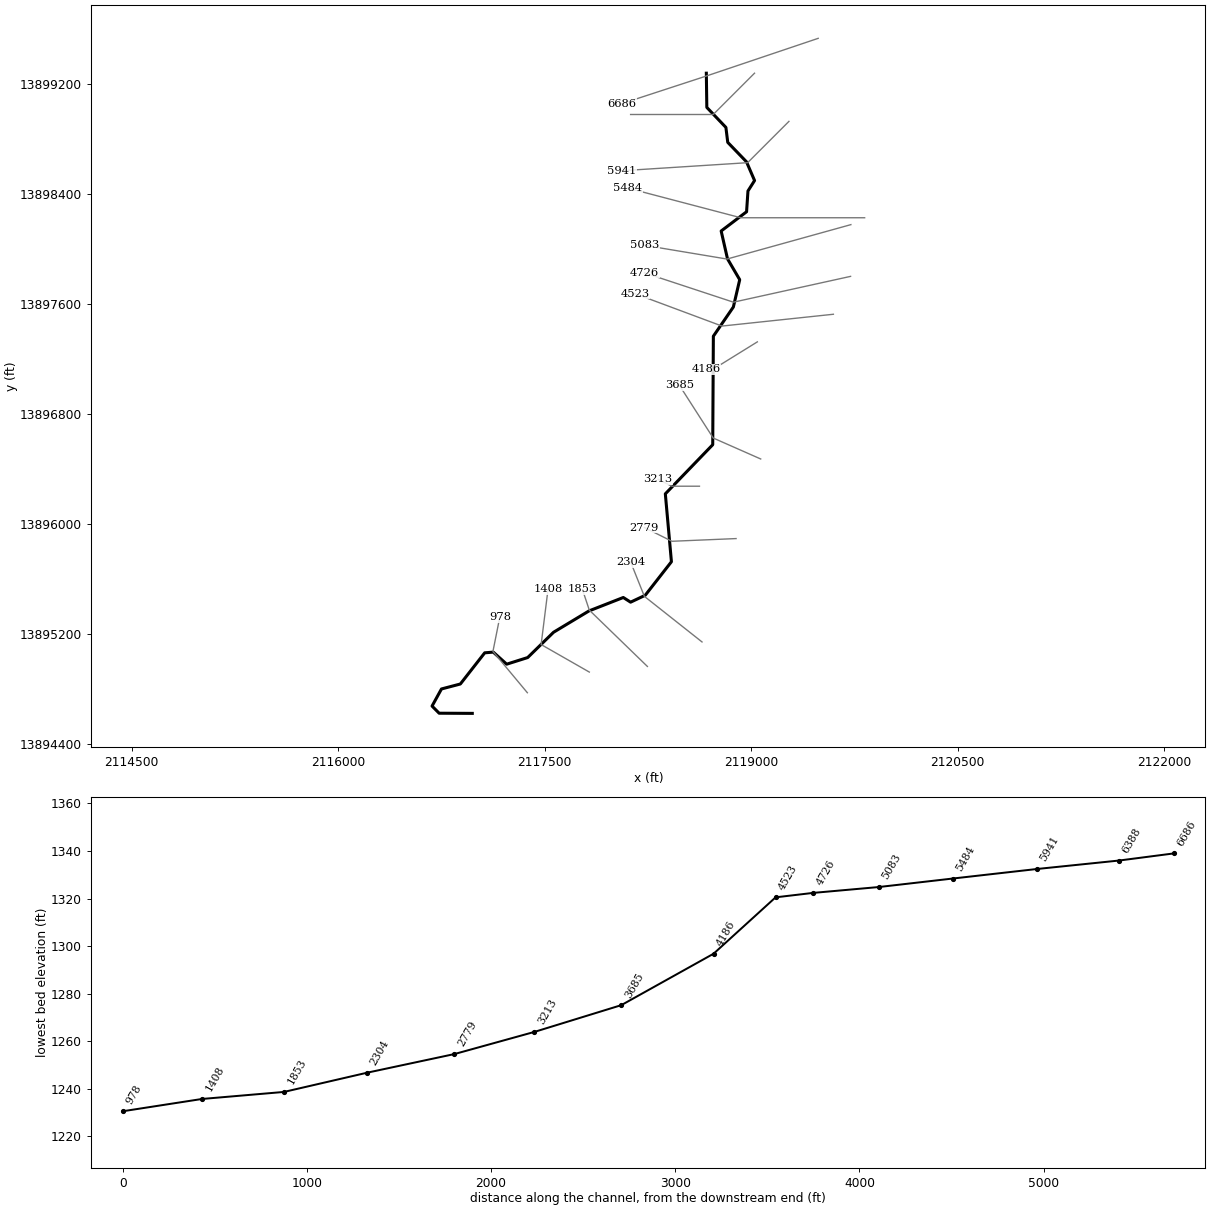
--- Stream0186_DS.prj (project) ---

Proj Title=Stream0186_DS Base Level Engineering
Current Plan=p01
Default Exp/Contr=0.3,0.1
English Units
Geom File=g01
Flow File=f01
Plan File=p01
BEGIN DESCRIPTION:
Stream0186_DS
END DESCRIPTION:

--- Stream0186_DS.p01 (plan) ---

Plan Title=Multiple Run
Short Identifier=Multiple
Geom File=g01
Flow File=f01
Subcritical Flow
K Sum by GR= 0
Std Step Tol= 0.01
Critical Tol= 0.01
Num of Std Step Trials= 20
Max Error Tol= 0.3
Flow Tol Ratio= 0.001
Split Flow NTrial= 30
Split Flow Tol= 0.02
Split Flow Ratio= 0.02
Log Output Level= 0
Friction Slope Method= 1
Unsteady Friction Slope Method= 2
Unsteady Bridges Friction Slope Method= 1
Parabolic Critical Depth
Global Vel Dist=  1 , 1 , 1
Global Log Level= 0
CheckData=True
Encroach Param= -1, 0, 0, 0
BEGIN DESCRIPTION:
Multiple Run
END DESCRIPTION:

--- Stream0186_DS.f01 (steady flow) ---

Flow Title=Multiple
Number of Profiles=7
Profile Names=10-year,25-year,50-year,1pct_min,100-year,1pct_plu,500-year
River Rch & RM= Stream0186_DS,Reach-1,6686
     430     680     903     582    1162    2318    1898
River Rch & RM= Stream0186_DS,Reach-1,6388
    1096    1845    2553    1712    3415    6815    6044
River Rch & RM= Stream0186_DS,Reach-1,1408
    1171    1979    2744    1843    3678    7338    6534
Boundary for River Rch & Prof#=Stream0186_DS,Reach-1,1
Up Type=0
Dn Type=3
Dn Slope=0.005
Boundary for River Rch & Prof#=Stream0186_DS,Reach-1,2
Up Type=0
Dn Type=3
Dn Slope=0.005
Boundary for River Rch & Prof#=Stream0186_DS,Reach-1,3
Up Type=0
Dn Type=3
Dn Slope=0.005
Boundary for River Rch & Prof#=Stream0186_DS,Reach-1,4
Up Type=0
Dn Type=3
Dn Slope=0.005
Boundary for River Rch & Prof#=Stream0186_DS,Reach-1,5
Up Type=0
Dn Type=3
Dn Slope=0.005
Boundary for River Rch & Prof#=Stream0186_DS,Reach-1,6
Up Type=0
Dn Type=3
Dn Slope=0.005
Boundary for River Rch & Prof#=Stream0186_DS,Reach-1,7
Up Type=0
Dn Type=3
Dn Slope=0.005

--- Stream0186_DS.g01 (geometry) ---

Geom Title=Existing Conditions

River Reach=Stream0186_DS,Reach-1
Reach XY= 30
      2118675.00     13899275.00      2118678.54     13899026.46
      2118817.14     13898881.17      2118830.52     13898772.57
      2118966.86     13898631.06      2119025.29     13898495.18
      2118977.41     13898419.48      2118967.26     13898268.54
      2118782.73     13898128.66      2118828.76     13897926.56
      2118917.47     13897775.01      2118871.24     13897576.56
      2118726.05     13897364.56      2118721.46     13896576.46
      2118377.17     13896219.56      2118421.46     13895726.46
      2118231.33     13895483.00      2118124.92     13895432.76
      2118071.78     13895466.72      2117822.71     13895369.16
      2117565.32     13895214.24      2117377.43     13895030.52
      2117224.90     13894982.33      2117127.29     13895069.91
      2117065.30     13895064.84      2116888.33     13894838.39
      2116751.10     13894802.28      2116682.75     13894678.02
      2116734.24     13894626.20      2116975.00     13894625.00

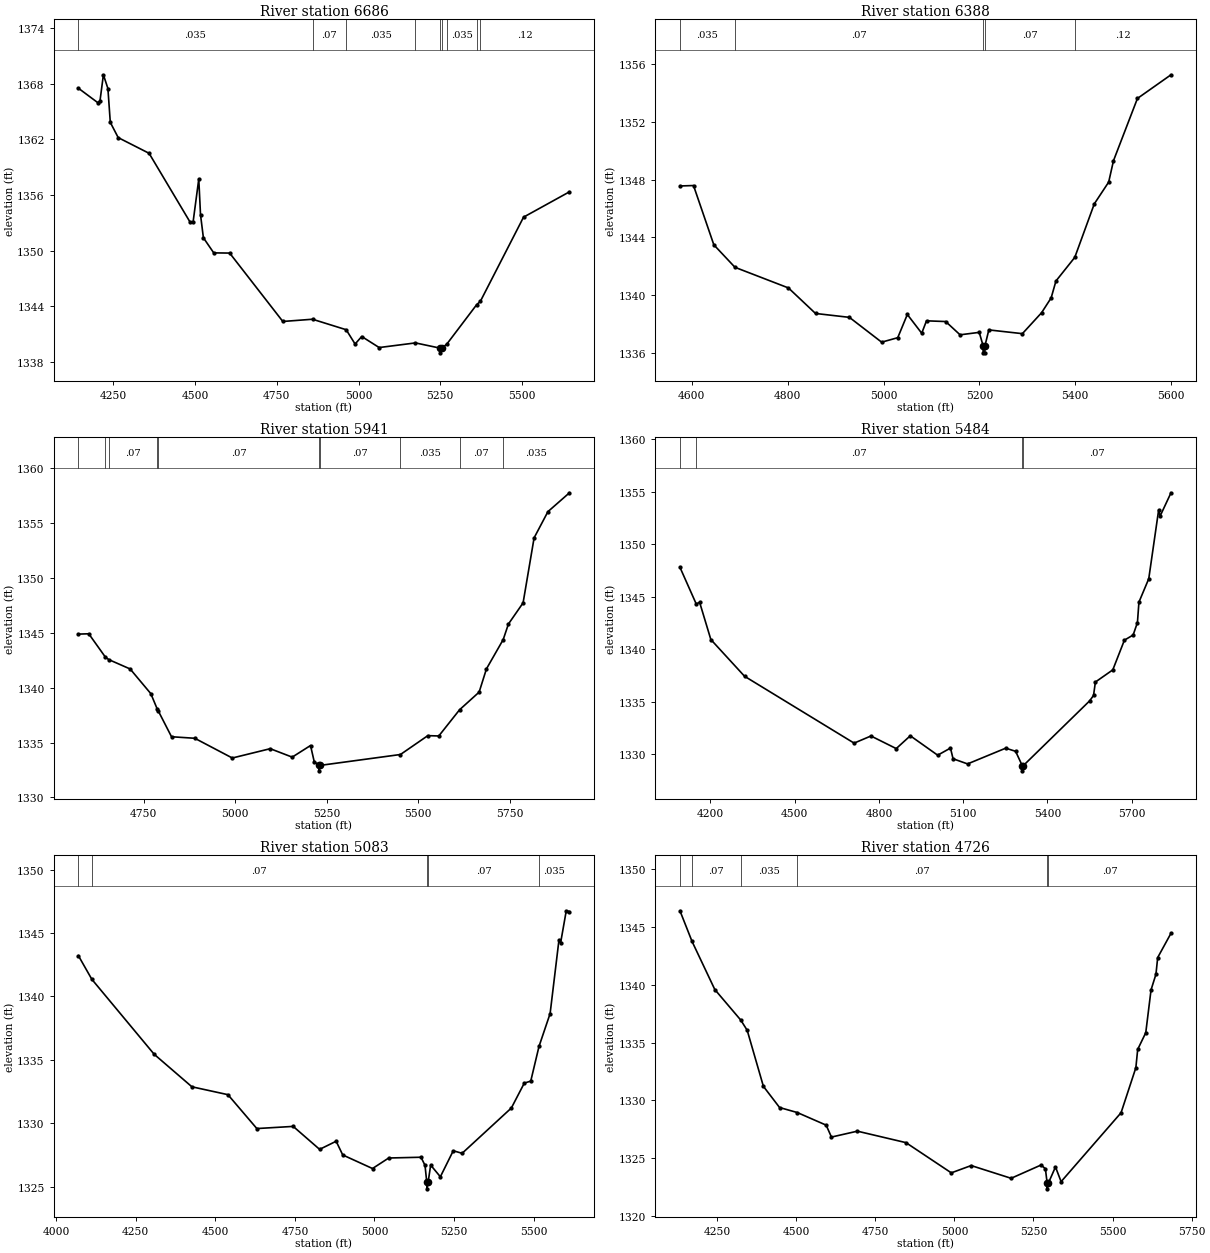
Type RM Length L Ch R = 1,6686,298,298,298
BEGIN DESCRIPTION:
Stream0186_DS 14.0
END DESCRIPTION:
XS GIS Cut Line= 3
      2119487.51     13899528.19      2118674.99     13899254.40
      2118061.40     13899053.96
#Sta/Elev= 30
  4142.6 1367.50  4201.4 1365.96  4208.6 1366.12  4219.1 1368.95  4232.9 1367.47
  4240.2 1363.82  4264.4 1362.18  4358.9 1360.49  4484.8 1353.05  4493.5 1353.06
  4511.0 1357.72  4516.3 1353.88  4525.1 1351.39  4556.8 1349.76  4605.5 1349.74
  4768.2 1342.37  4859.1 1342.61  4962.1 1341.48  4989.4 1339.94  5009.7 1340.75
  5063.1 1339.56  5174.2 1340.06  5250.5 1339.49  5250.7 1338.99  5254.5 1339.49
  5270.1 1339.93  5361.3 1344.17  5372.8 1344.54  5505.0 1353.61  5645.5 1356.34
#Mann=9,-1,0
  4142.6   0.035       0  4859.1    0.07       0  4962.1   0.035       0
  5174.2    0.07       0  5250.5   0.035       0  5254.5    0.07       0
  5270.1   0.035       0  5361.3    0.07       0  5372.8    0.12       0
Bank Sta=5250.5,5254.5
Exp/Cntr=0.3,0.1

Type RM Length L Ch R = 1,6388,447,447,447
BEGIN DESCRIPTION:
Stream0186_DS 13.0
END DESCRIPTION:
XS GIS Cut Line= 3
      2119025.00     13899275.00      2118725.00     13898975.00
      2118124.96     13898975.00
#Sta/Elev= 30
  4575.4 1347.56  4603.7 1347.59  4646.1 1343.48  4690.2 1341.92  4801.7 1340.49
  4858.2 1338.72  4928.9 1338.45  4996.1 1336.73  5029.7 1337.04  5049.7 1338.65
  5079.7 1337.35  5089.7 1338.21  5129.7 1338.16  5159.7 1337.24  5199.7 1337.41
  5207.7 1336.49  5207.9 1335.99  5211.4 1335.99  5211.7 1336.49  5219.7 1337.58
  5289.7 1337.32  5329.7 1338.77  5349.7 1339.80  5359.7 1340.97  5399.0 1342.61
  5439.7 1346.32  5469.7 1347.83  5479.7 1349.31  5529.7 1353.63  5599.7 1355.27
#Mann=5,-1,0
  4575.4   0.035       0  4690.2    0.07       0  5207.7    0.05       0
  5211.7    0.07       0  5399.0    0.12       0
Bank Sta=5207.7,5211.7
Exp/Cntr=0.3,0.1

Type RM Length L Ch R = 1,5941,457,457,457
BEGIN DESCRIPTION:
Stream0186_DS 12.0
END DESCRIPTION:
XS GIS Cut Line= 3
      2119275.03     13898925.03      2118975.00     13898625.00
      2118058.48     13898566.41
#Sta/Elev= 30
  4571.1 1344.89  4599.4 1344.92  4644.9 1342.79  4654.5 1342.56  4712.6 1341.71
  4769.1 1339.46  4786.2 1338.09  4789.1 1337.91  4825.7 1335.53  4889.3 1335.39
  4991.9 1333.59  5095.6 1334.44  5155.7 1333.67  5205.8 1334.73  5215.9 1333.25
  5228.7 1332.92  5229.0 1332.42  5232.7 1332.92  5451.7 1333.91  5526.5 1335.63
  5556.5 1335.60  5613.3 1337.99  5666.8 1339.60  5686.8 1341.72  5732.6 1344.39
  5746.9 1345.81  5787.0 1347.74  5817.1 1353.67  5854.9 1356.06  5913.8 1357.78
#Mann=10,-1,0
  4571.1    0.07       0  4644.9   0.035       0  4654.5    0.07       0
  4786.2   0.035       0  4789.1    0.07       0  5228.7    0.05       0
  5232.7    0.07       0  5451.7   0.035       0  5613.3    0.07       0
  5732.6   0.035       0
Bank Sta=5228.7,5232.7
Exp/Cntr=0.3,0.1

Type RM Length L Ch R = 1,5484,401,401,401
BEGIN DESCRIPTION:
Stream0186_DS 11.0
END DESCRIPTION:
XS GIS Cut Line= 3
      2119824.97     13898225.00      2118925.00     13898225.00
      2118104.58     13898440.41
#Sta/Elev= 30
  4091.7 1347.80  4149.8 1344.30  4161.7 1344.47  4201.7 1340.92  4321.7 1337.42
  4711.7 1331.05  4771.7 1331.73  4861.7 1330.53  4911.7 1331.75  5009.3 1329.90
  5054.8 1330.58  5064.0 1329.56  5115.7 1329.07  5251.5 1330.57  5286.7 1330.27
  5310.2 1328.91  5310.4 1328.41  5314.2 1328.91  5550.0 1335.07  5564.1 1335.59
  5570.7 1336.87  5632.7 1338.03  5674.0 1340.86  5705.1 1341.35  5720.4 1342.54
  5725.7 1344.48  5760.7 1346.71  5795.9 1353.26  5801.1 1352.68  5839.9 1354.90
#Mann=4,-1,0
  4091.7    0.12       0  4149.8    0.07       0  5310.2    0.05       0
  5314.2    0.07       0
Bank Sta=5310.2,5314.2
Exp/Cntr=0.3,0.1

Type RM Length L Ch R = 1,5083,357,357,357
BEGIN DESCRIPTION:
Stream0186_DS 10.0
END DESCRIPTION:
XS GIS Cut Line= 3
      2119724.96     13898174.99      2118825.00     13897925.00
      2118225.01     13898025.00
#Sta/Elev= 30
  4070.1 1343.21  4112.3 1341.35  4308.2 1335.44  4426.6 1332.88  4539.7 1332.26
  4630.5 1329.59  4744.7 1329.76  4827.7 1327.95  4879.6 1328.59  4900.3 1327.51
  4993.8 1326.44  5044.7 1327.27  5146.1 1327.33  5158.7 1326.69  5164.3 1325.34
  5164.6 1324.84  5168.3 1325.34  5176.5 1326.71  5206.9 1325.79  5247.4 1327.84
  5275.3 1327.64  5429.9 1331.21  5470.5 1333.17  5490.8 1333.33  5516.7 1336.06
  5551.6 1338.65  5579.5 1344.47  5584.5 1344.21  5602.3 1346.75  5612.4 1346.69
#Mann=5,-1,0
  4070.1    0.12       0  4112.3    0.07       0  5164.3    0.05       0
  5168.3    0.07       0  5516.7   0.035       0
Bank Sta=5164.3,5168.3
Exp/Cntr=0.3,0.1

Type RM Length L Ch R = 1,4726,203,203,203
BEGIN DESCRIPTION:
Stream0186_DS 9.0
END DESCRIPTION:
XS GIS Cut Line= 3
      2119722.67     13897799.21      2118871.94     13897611.70
      2118225.04     13897824.99
#Sta/Elev= 30
  4132.4 1346.38  4170.7 1343.73  4242.6 1339.58  4324.7 1336.94  4345.0 1336.06
  4396.2 1331.22  4447.4 1329.39  4503.2 1328.96  4594.6 1327.87  4611.3 1326.84
  4693.2 1327.35  4846.8 1326.36  4990.2 1323.75  5053.0 1324.38  5179.3 1323.28
  5274.1 1324.43  5287.7 1324.10  5293.1 1322.87  5293.4 1322.37  5297.1 1322.87
  5319.5 1324.26  5337.3 1322.99  5526.8 1328.94  5573.6 1332.83  5579.4 1334.41
  5604.9 1335.85  5621.6 1339.55  5637.1 1340.90  5642.6 1342.34  5684.7 1344.44
#Mann=6,-1,0
  4132.4    0.12       0  4170.7    0.07       0  4324.7   0.035       0
  4503.2    0.07       0  5293.1    0.05       0  5297.1    0.07       0
Bank Sta=5293.1,5297.1
Exp/Cntr=0.3,0.1

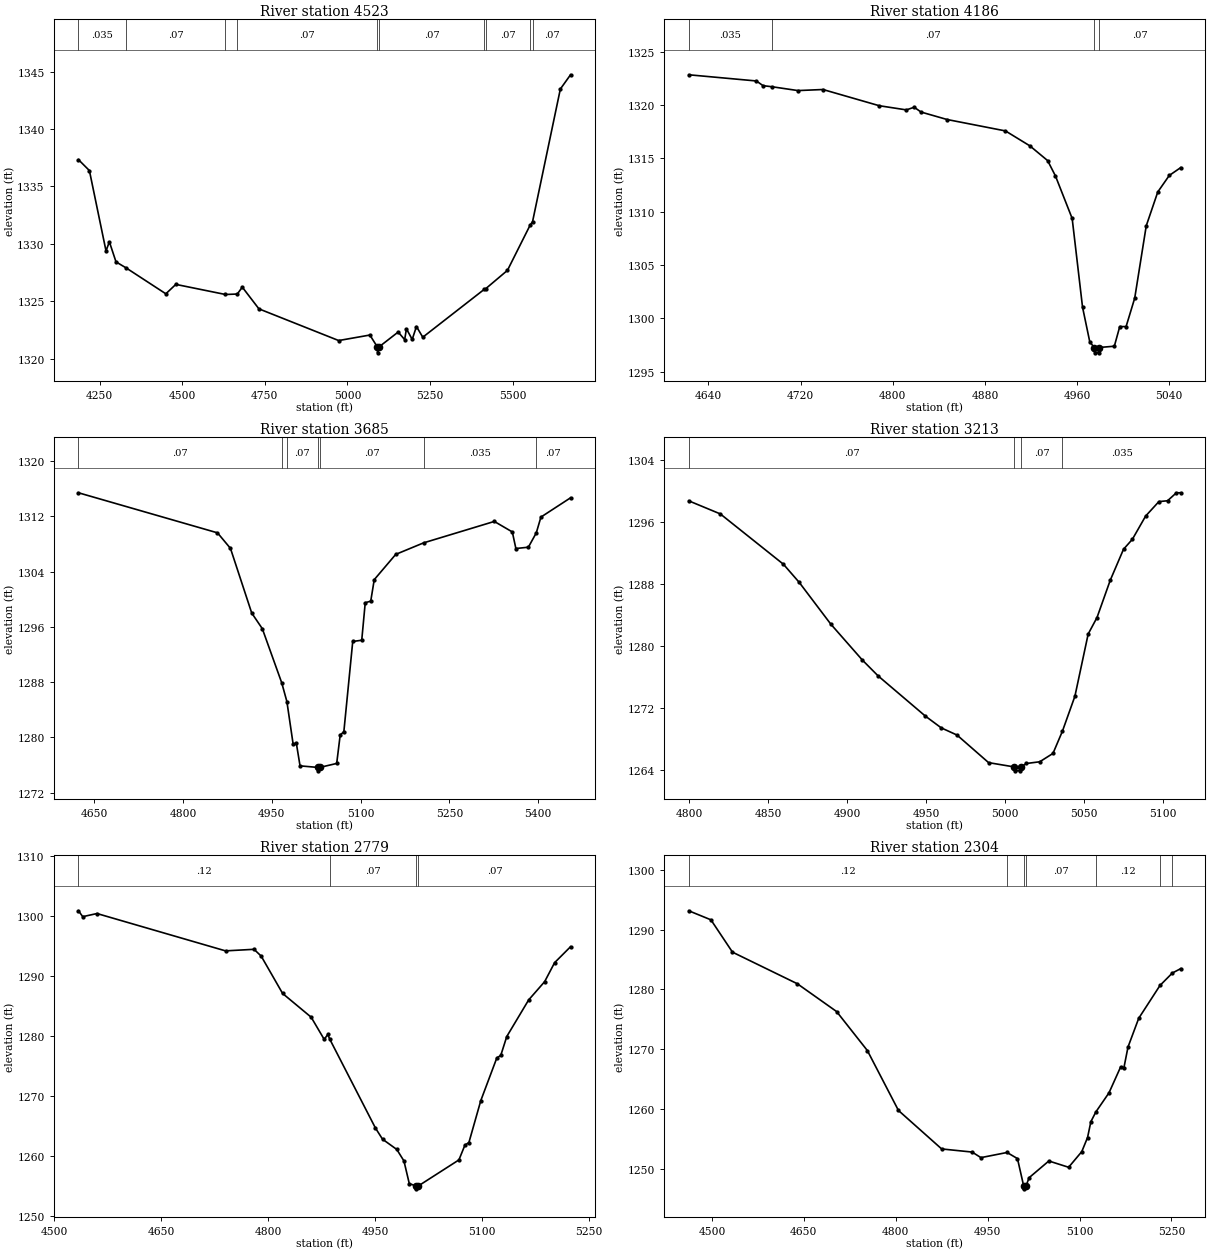
Type RM Length L Ch R = 1,4523,337,337,337
BEGIN DESCRIPTION:
Stream0186_DS 9.5
END DESCRIPTION:
XS GIS Cut Line= 3
      2119597.93     13897524.03      2118788.57     13897438.24
      2118156.14     13897673.88
#Sta/Elev= 30
  4186.1 1337.33  4219.2 1336.38  4269.5 1329.38  4279.6 1330.18  4299.7 1328.43
  4330.0 1327.91  4450.5 1325.65  4480.7 1326.47  4630.9 1325.59  4666.7 1325.63
  4681.8 1326.23  4732.1 1324.34  4973.4 1321.58  5067.8 1322.06  5090.7 1321.01
  5091.0 1320.51  5094.7 1321.01  5153.4 1322.32  5173.1 1321.66  5178.4 1322.60
  5195.9 1321.68  5208.7 1322.80  5227.9 1321.87  5414.4 1326.05  5417.7 1326.08
  5484.0 1327.69  5552.5 1331.62  5560.0 1331.93  5644.1 1343.48  5674.9 1344.72
#Mann=10,-1,0
  4186.1   0.035       0  4330.0    0.07       0  4630.9   0.035       0
  4666.7    0.07       0  5090.7    0.05       0  5094.7    0.07       0
  5414.4   0.035       0  5417.7    0.07       0  5552.5   0.035       0
  5560.0    0.07       0
Bank Sta=5090.7,5094.7
Exp/Cntr=0.3,0.1

Type RM Length L Ch R = 1,4186,501,501,501
BEGIN DESCRIPTION:
Stream0186_DS 8.0
END DESCRIPTION:
XS GIS Cut Line= 3
      2119045.59     13897323.53      2118725.00     13897125.00
      2118674.98     13897125.00
#Sta/Elev= 30
  4622.9 1322.83  4681.6 1322.25  4687.4 1321.81  4695.1 1321.71  4717.7 1321.35
  4739.4 1321.45  4788.3 1319.93  4811.8 1319.54  4818.6 1319.79  4824.5 1319.34
  4847.1 1318.64  4897.8 1317.57  4919.0 1316.17  4934.4 1314.79  4941.2 1313.35
  4955.7 1309.37  4964.7 1301.06  4971.0 1297.80  4974.9 1297.28  4975.2 1296.78
  4978.7 1296.78  4978.9 1297.28  4992.3 1297.40  4997.0 1299.24  5002.5 1299.24
  5010.0 1301.91  5020.0 1308.68  5030.0 1311.85  5040.0 1313.40  5050.0 1314.14
#Mann=4,-1,0
  4622.9   0.035       0  4695.1    0.07       0  4974.9    0.05       0
  4978.9    0.07       0
Bank Sta=4974.9,4978.9
Exp/Cntr=0.3,0.1

Type RM Length L Ch R = 1,3685,472,472,472
BEGIN DESCRIPTION:
Stream0186_DS 7.0
END DESCRIPTION:
XS GIS Cut Line= 3
      2119069.85     13896472.81      2118725.00     13896625.00
      2118479.81     13897007.17
#Sta/Elev= 30
  4623.5 1315.41  4858.3 1309.61  4880.2 1307.36  4916.1 1298.00  4934.0 1295.73
  4966.8 1287.89  4975.5 1285.18  4986.0 1279.04  4991.5 1279.13  4997.7 1275.87
  5027.2 1275.65  5027.4 1275.15  5031.2 1275.65  5059.6 1276.22  5065.5 1280.33
  5071.7 1280.82  5086.7 1293.88  5101.9 1294.06  5107.8 1299.49  5117.1 1299.72
  5123.0 1302.83  5159.3 1306.49  5206.4 1308.16  5325.8 1311.26  5356.2 1309.74
  5362.2 1307.34  5383.3 1307.53  5396.7 1309.61  5404.5 1311.89  5454.5 1314.68
#Mann=7,-1,0
  4623.5    0.07       0  4966.8    0.12       0  4975.5    0.07       0
  5027.2    0.05       0  5031.2    0.07       0  5206.4   0.035       0
  5396.7    0.07       0
Bank Sta=5027.2,5031.2
Exp/Cntr=0.3,0.1

Type RM Length L Ch R = 1,3213,434,434,434
BEGIN DESCRIPTION:
Stream0186_DS 6.0
END DESCRIPTION:
XS GIS Cut Line= 3
      2118625.02     13896275.00      2118425.00     13896275.00
      2118325.02     13896324.99
#Sta/Elev= 30
  4799.7 1298.76  4819.7 1297.07  4859.7 1290.57  4869.7 1288.23  4889.7 1282.84
  4909.7 1278.20  4919.7 1276.15  4949.7 1270.95  4959.7 1269.44  4969.7 1268.51
  4989.7 1264.95  5006.1 1264.39  5006.4 1263.89  5009.9 1263.89  5010.1 1264.39
  5013.7 1264.84  5022.1 1265.06  5030.5 1266.14  5036.5 1269.02  5044.4 1273.53
  5052.8 1281.56  5058.4 1283.69  5066.8 1288.51  5075.2 1292.51  5080.8 1293.79
  5089.2 1296.79  5097.6 1298.66  5103.1 1298.77  5108.7 1299.80  5111.5 1299.80
#Mann=4,-1,0
  4799.7    0.07       0  5006.1    0.05       0  5010.1    0.07       0
  5036.5   0.035       0
Bank Sta=5006.1,5010.1
Exp/Cntr=0.3,0.1

Type RM Length L Ch R = 1,2779,475,475,475
BEGIN DESCRIPTION:
Stream0186_DS 5.0
END DESCRIPTION:
XS GIS Cut Line= 3
      2118891.00     13895894.68      2118425.00     13895875.00
      2118225.02     13895974.99
#Sta/Elev= 30
  4534.0 1300.91  4540.0 1299.93  4560.0 1300.45  4740.2 1294.23  4780.2 1294.49
  4790.2 1293.36  4820.3 1287.13  4860.3 1283.18  4878.6 1279.48  4883.6 1280.30
  4886.5 1279.49  4950.4 1264.72  4960.4 1262.85  4980.4 1261.14  4990.4 1259.23
  4997.9 1255.45  5006.8 1255.08  5007.0 1254.58  5010.8 1255.08  5067.5 1259.40
  5075.9 1261.86  5081.5 1262.30  5098.2 1269.29  5120.6 1276.38  5126.2 1276.82
  5134.6 1279.96  5165.3 1286.06  5187.7 1289.10  5201.7 1292.27  5224.0 1294.92
#Mann=4,-1,0
  4534.0    0.12       0  4886.5    0.07       0  5006.8    0.05       0
  5010.8    0.07       0
Bank Sta=5006.8,5010.8
Exp/Cntr=0.3,0.1

Type RM Length L Ch R = 1,2304,451,451,451
BEGIN DESCRIPTION:
Stream0186_DS 4.0
END DESCRIPTION:
XS GIS Cut Line= 3
      2118643.65     13895143.81      2118225.00     13895475.00
      2118124.99     13895725.03
#Sta/Elev= 30
  4462.1 1293.14  4498.3 1291.63  4533.5 1286.23  4639.3 1280.96  4703.4 1276.32
  4753.6 1269.81  4804.4 1259.80  4874.9 1253.38  4924.6 1252.86  4939.0 1251.93
  4981.6 1252.79  4998.6 1251.77  5008.7 1247.22  5009.0 1246.72  5012.7 1247.22
  5017.5 1248.57  5049.8 1251.37  5082.1 1250.32  5103.6 1252.94  5113.0 1255.29
  5118.4 1257.93  5126.5 1259.55  5148.0 1262.75  5166.9 1267.05  5172.3 1266.91
  5179.0 1270.39  5196.5 1275.19  5231.2 1280.67  5251.4 1282.75  5265.2 1283.49
#Mann=7,-1,0
  4462.1    0.12       0  4981.6    0.07       0  5008.7    0.05       0
  5012.7    0.07       0  5126.5    0.12       0  5231.2    0.07       0
  5251.4   0.035       0
Bank Sta=5008.7,5012.7
Exp/Cntr=0.3,0.1

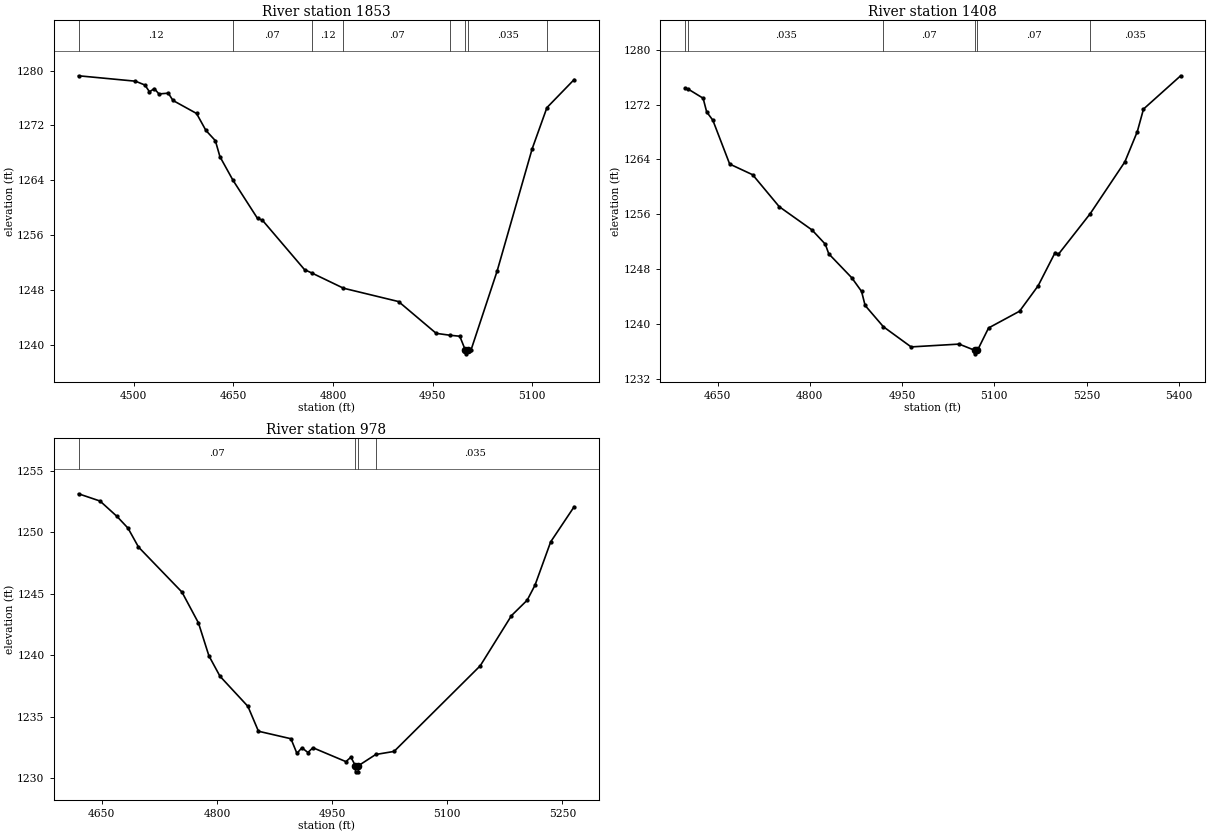
Type RM Length L Ch R = 1,1853,445,445,445
BEGIN DESCRIPTION:
Stream0186_DS 3.0
END DESCRIPTION:
XS GIS Cut Line= 3
      2118246.93     13894965.87      2117825.00     13895375.00
      2117775.01     13895524.97
#Sta/Elev= 30
  4417.1 1279.23  4502.8 1278.44  4517.0 1277.88  4523.9 1276.89  4531.1 1277.36
  4538.1 1276.58  4552.2 1276.69  4559.2 1275.63  4594.7 1273.73  4608.8 1271.25
  4623.0 1269.76  4629.9 1267.42  4649.4 1264.00  4686.5 1258.40  4693.7 1258.16
  4757.2 1250.93  4768.2 1250.44  4815.8 1248.22  4898.7 1246.27  4955.3 1241.63
  4976.4 1241.35  4990.8 1241.21  4999.3 1239.14  4999.6 1238.64  5003.3 1239.14
  5007.5 1239.14  5047.0 1250.73  5099.7 1268.57  5121.9 1274.58  5162.9 1278.68
#Mann=8,-1,0
  4417.1    0.12       0  4649.4    0.07       0  4768.2    0.12       0
  4815.8    0.07       0  4976.4   0.035       0  4999.3   0.035       0
  5003.3   0.035       0  5121.9    0.07       0
Bank Sta=4999.3,5003.3
Exp/Cntr=0.3,0.1

Type RM Length L Ch R = 1,1408,430,430,430
BEGIN DESCRIPTION:
Stream0186_DS 2.0
END DESCRIPTION:
XS GIS Cut Line= 3
      2117825.00     13894925.00      2117475.00     13895125.00
      2117525.00     13895524.98
#Sta/Elev= 30
  4596.9 1274.39  4601.9 1274.26  4626.4 1272.92  4632.2 1270.92  4642.2 1269.72
  4669.6 1263.33  4707.0 1261.77  4750.2 1257.12  4803.5 1253.73  4825.1 1251.66
  4830.8 1250.25  4868.3 1246.75  4884.1 1244.78  4889.9 1242.73  4919.6 1239.63
  4964.7 1236.69  5042.8 1237.10  5068.6 1236.18  5068.8 1235.68  5072.6 1236.18
  5090.7 1239.45  5141.1 1241.89  5171.3 1245.59  5199.0 1250.44  5204.1 1250.16
  5256.1 1256.11  5312.4 1263.65  5332.6 1268.05  5342.7 1271.34  5403.1 1276.19
#Mann=6,-1,0
  4596.9    0.12       0  4601.9   0.035       0  4919.6    0.07       0
  5068.6    0.05       0  5072.6    0.07       0  5256.1   0.035       0
Bank Sta=5068.6,5072.6
Exp/Cntr=0.3,0.1

Type RM Length L Ch R = 1,978,0,0,0
BEGIN DESCRIPTION:
Stream0186_DS 1.0
END DESCRIPTION:
XS GIS Cut Line= 3
      2117374.98     13894775.02      2117125.00     13895075.00
      2117174.99     13895324.97
#Sta/Elev= 30
  4619.8 1253.12  4647.8 1252.53  4669.9 1251.28  4684.2 1250.33  4697.9 1248.79
  4754.5 1245.13  4776.0 1242.62  4789.6 1239.95  4804.0 1238.29  4840.4 1235.84
  4854.1 1233.82  4896.4 1233.21  4904.2 1232.02  4910.7 1232.48  4918.5 1232.09
  4925.0 1232.48  4968.0 1231.35  4974.5 1231.71  4980.3 1231.02  4980.5 1230.52
  4984.0 1230.52  4984.3 1231.02  5006.8 1231.93  5030.7 1232.18  5142.9 1239.14
  5183.6 1243.22  5204.0 1244.47  5214.2 1245.69  5234.6 1249.21  5265.2 1252.07
#Mann=4,-1,0
  4619.8    0.07       0  4980.3    0.05       0  4984.3    0.07       0
  5006.8   0.035       0
Bank Sta=4980.3,4984.3
Exp/Cntr=0.3,0.1

Chan Stop Cuts=-1