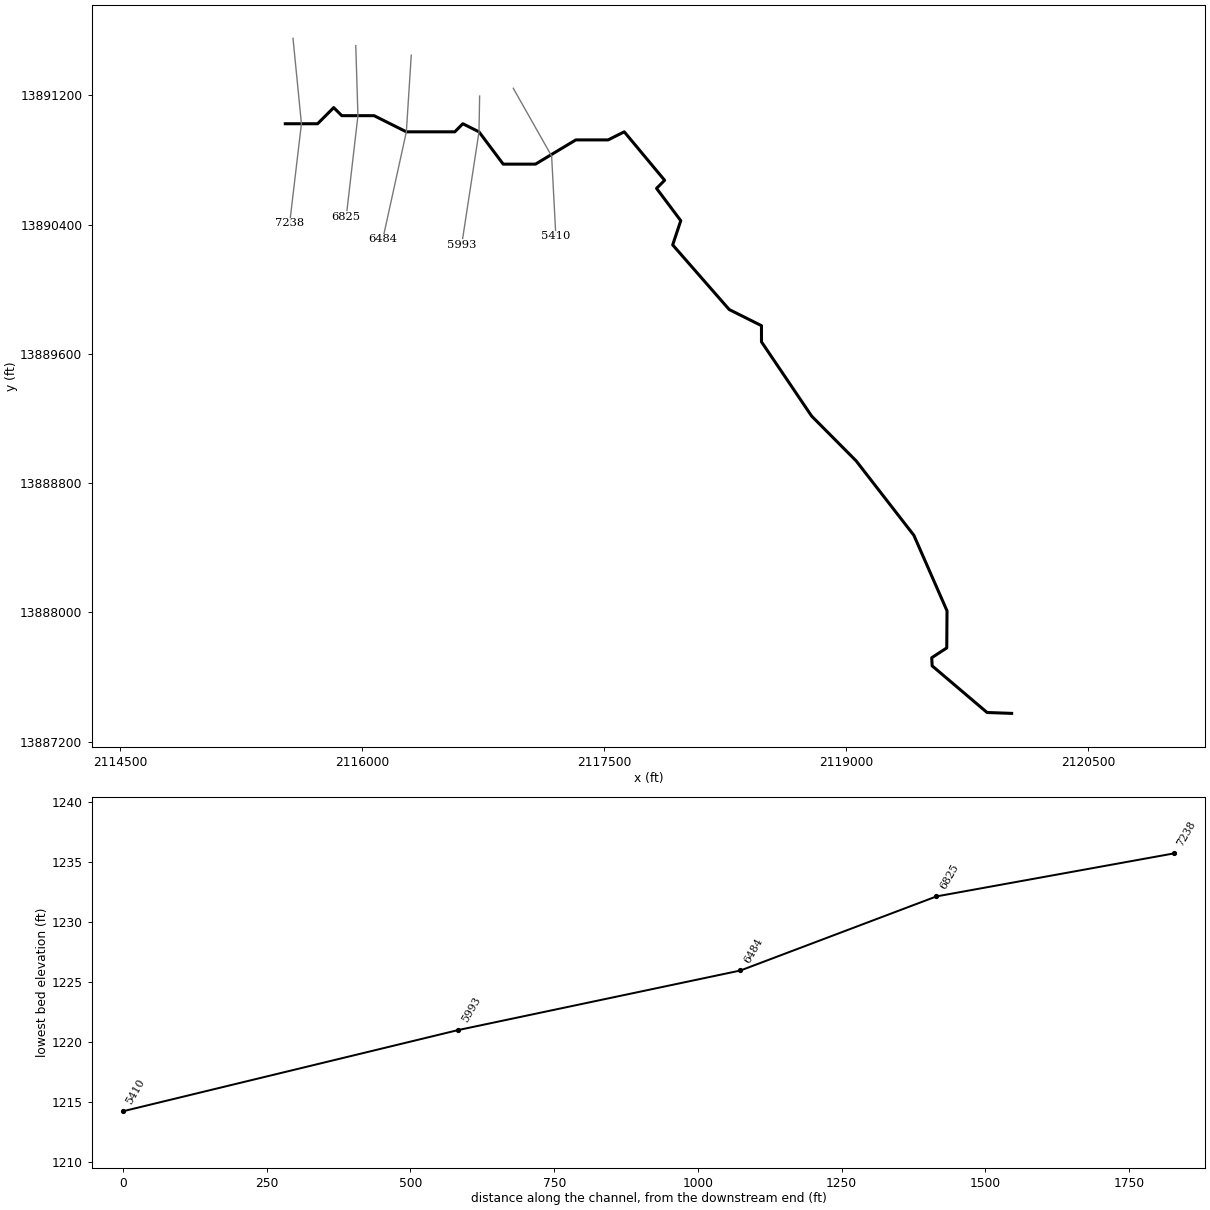
--- Stream0187_DS.prj (project) ---

Proj Title=Stream0187_DS Base Level Engineering
Current Plan=p01
Default Exp/Contr=0.3,0.1
English Units
Geom File=g01
Flow File=f01
Plan File=p01
BEGIN DESCRIPTION:
Stream0187_DS
END DESCRIPTION:

--- Stream0187_DS.p01 (plan) ---

Plan Title=Multiple Run
Short Identifier=Multiple
Geom File=g01
Flow File=f01
Subcritical Flow
K Sum by GR= 0
Std Step Tol= 0.01
Critical Tol= 0.01
Num of Std Step Trials= 20
Max Error Tol= 0.3
Flow Tol Ratio= 0.001
Split Flow NTrial= 30
Split Flow Tol= 0.02
Split Flow Ratio= 0.02
Log Output Level= 0
Friction Slope Method= 1
Unsteady Friction Slope Method= 2
Unsteady Bridges Friction Slope Method= 1
Parabolic Critical Depth
Global Vel Dist=  1 , 1 , 1
Global Log Level= 0
CheckData=True
Encroach Param= -1, 0, 0, 0
BEGIN DESCRIPTION:
Multiple Run
END DESCRIPTION:

--- Stream0187_DS.f01 (steady flow) ---

Flow Title=Multiple
Number of Profiles=7
Profile Names=10-year,25-year,50-year,1pct_min,100-year,1pct_plu,500-year
River Rch & RM= Stream0187_DS,Reach-1,7238
     340     530     697     446     890    1775    1429
River Rch & RM= Stream0187_DS,Reach-1,6825
    1228    2077    2881    1935    3861    7703    6860
Boundary for River Rch & Prof#=Stream0187_DS,Reach-1,1
Up Type=0
Dn Type=3
Dn Slope=0.005
Boundary for River Rch & Prof#=Stream0187_DS,Reach-1,2
Up Type=0
Dn Type=3
Dn Slope=0.005
Boundary for River Rch & Prof#=Stream0187_DS,Reach-1,3
Up Type=0
Dn Type=3
Dn Slope=0.005
Boundary for River Rch & Prof#=Stream0187_DS,Reach-1,4
Up Type=0
Dn Type=3
Dn Slope=0.005
Boundary for River Rch & Prof#=Stream0187_DS,Reach-1,5
Up Type=0
Dn Type=3
Dn Slope=0.005
Boundary for River Rch & Prof#=Stream0187_DS,Reach-1,6
Up Type=0
Dn Type=3
Dn Slope=0.005
Boundary for River Rch & Prof#=Stream0187_DS,Reach-1,7
Up Type=0
Dn Type=3
Dn Slope=0.005

--- Stream0187_DS.g01 (geometry) ---

Geom Title=Existing Conditions

River Reach=Stream0187_DS,Reach-1
Reach XY= 30
      2115525.00     13891025.00      2115725.00     13891025.00
      2115825.00     13891125.00      2115875.00     13891075.00
      2116075.00     13891075.00      2116275.00     13890975.00
      2116575.00     13890975.00      2116625.00     13891025.00
      2116725.00     13890975.00      2116875.00     13890775.00
      2117075.00     13890775.00      2117325.00     13890925.00
      2117525.00     13890925.00      2117625.00     13890975.00
      2117875.00     13890675.00      2117825.00     13890625.00
      2117975.00     13890425.00      2117925.00     13890275.00
      2118275.00     13889875.00      2118475.00     13889775.00
      2118475.00     13889675.00      2118785.78     13889215.32
      2119061.37     13888938.21      2119419.15     13888477.29
      2119624.48     13888009.78      2119622.88     13887780.27
      2119529.77     13887719.36      2119532.34     13887669.25
      2119872.54     13887380.44      2120025.00     13887375.00

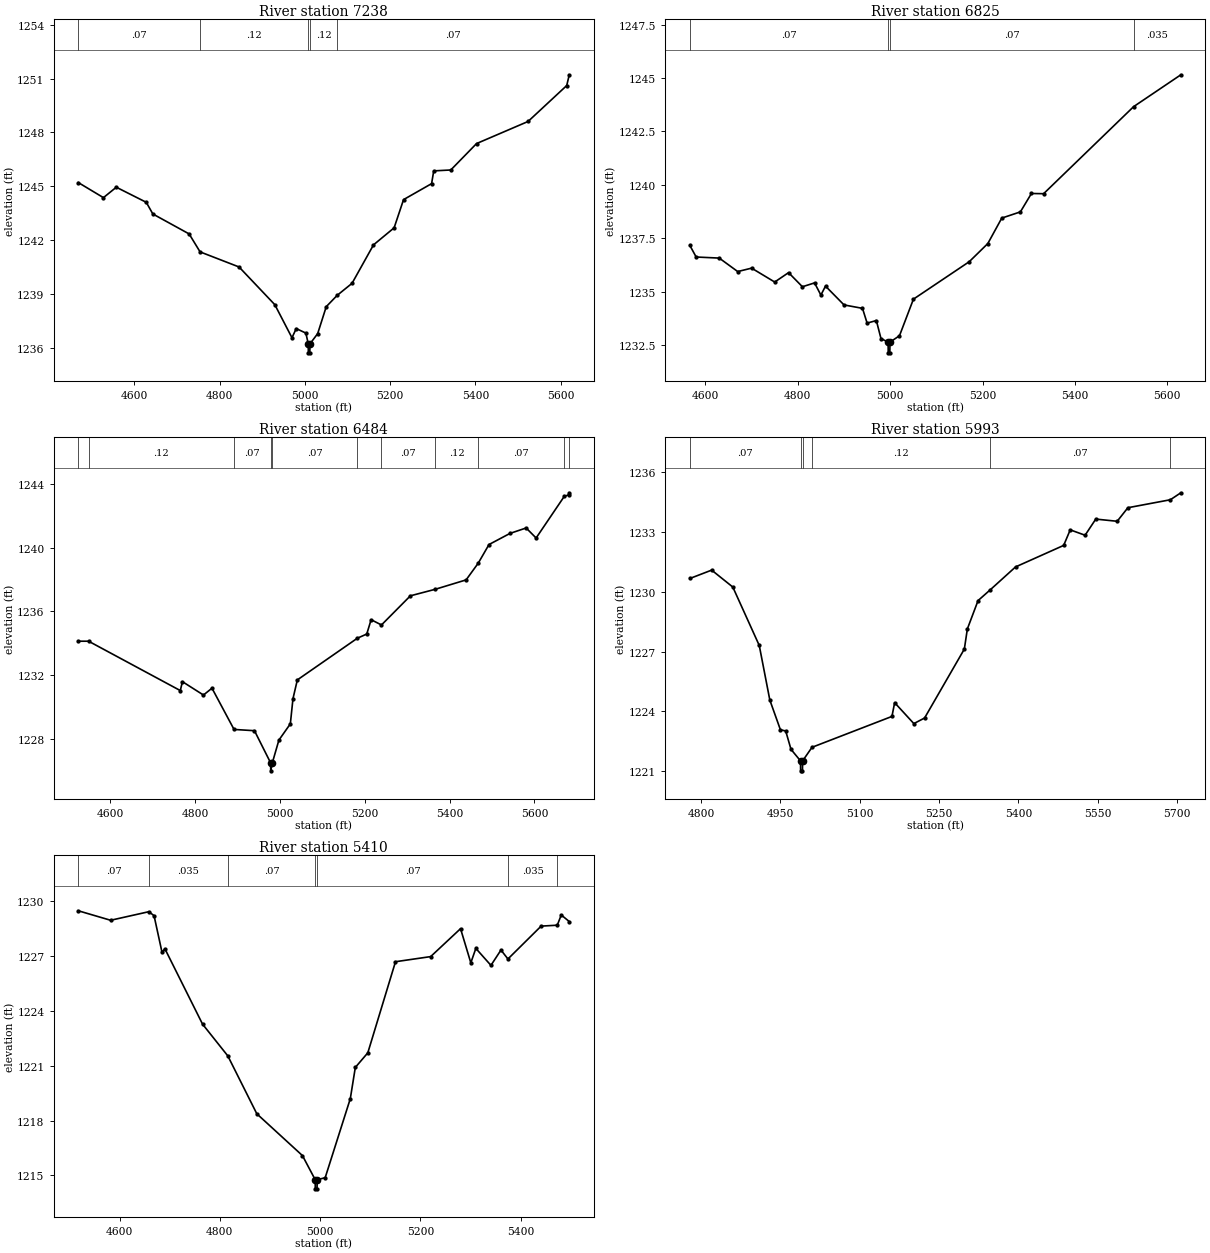
Type RM Length L Ch R = 1,7238,413,413,413
BEGIN DESCRIPTION:
Stream0187_DS 5.0
END DESCRIPTION:
XS GIS Cut Line= 3
      2115572.77     13891553.73      2115625.00     13891025.00
      2115552.06     13890409.00
#Sta/Elev= 30
  4468.7 1245.21  4527.7 1244.37  4557.9 1244.95  4628.2 1244.11  4643.6 1243.46
  4728.7 1242.35  4754.4 1241.35  4845.8 1240.51  4929.7 1238.41  4969.9 1236.57
  4979.9 1237.08  5002.5 1236.83  5008.1 1236.23  5008.3 1235.73  5011.8 1235.73
  5012.1 1236.23  5030.2 1236.80  5050.3 1238.30  5075.9 1238.93  5110.8 1239.60
  5161.1 1241.74  5209.5 1242.69  5231.6 1244.26  5297.4 1245.15  5302.4 1245.86
  5342.4 1245.91  5402.8 1247.38  5523.6 1248.61  5614.3 1250.61  5620.3 1251.21
#Mann=5,-1,0
  4468.7    0.07       0  4754.4    0.12       0  5008.1    0.05       0
  5012.1    0.12       0  5075.9    0.07       0
Bank Sta=5008.1,5012.1
Exp/Cntr=0.3,0.1

Type RM Length L Ch R = 1,6825,341,341,341
BEGIN DESCRIPTION:
Stream0187_DS 4.0
END DESCRIPTION:
XS GIS Cut Line= 3
      2115961.66     13891508.59      2115975.00     13891075.00
      2115902.65     13890449.77
#Sta/Elev= 30
  4566.2 1237.17  4579.8 1236.63  4629.8 1236.58  4669.8 1235.95  4699.9 1236.11
  4749.9 1235.46  4779.9 1235.90  4809.9 1235.24  4836.2 1235.42  4849.9 1234.85
  4859.9 1235.27  4900.0 1234.39  4940.0 1234.23  4950.0 1233.54  4970.0 1233.66
  4980.0 1232.82  4995.5 1232.65  4995.7 1232.15  4999.2 1232.15  4999.5 1232.65
  5020.1 1232.95  5050.3 1234.66  5171.1 1236.41  5211.4 1237.26  5241.6 1238.45
  5281.9 1238.74  5305.8 1239.60  5332.2 1239.59  5527.1 1243.66  5629.4 1245.15
#Mann=4,-1,0
  4566.2    0.07       0  4995.5    0.05       0  4999.5    0.07       0
  5527.1   0.035       0
Bank Sta=4995.5,4999.5
Exp/Cntr=0.3,0.1

Type RM Length L Ch R = 1,6484,491,491,491
BEGIN DESCRIPTION:
Stream0187_DS 3.0
END DESCRIPTION:
XS GIS Cut Line= 3
      2116305.41     13891449.63      2116275.00     13890975.00
      2116128.62     13890308.59
#Sta/Elev= 30
  4524.4 1234.12  4548.7 1234.12  4765.0 1231.02  4770.0 1231.58  4819.6 1230.74
  4839.7 1231.17  4891.7 1228.58  4939.9 1228.50  4978.0 1226.48  4978.2 1225.98
  4982.0 1226.48  4997.5 1227.91  5024.5 1228.93  5030.7 1230.51  5041.0 1231.69
  5182.7 1234.31  5204.7 1234.57  5215.0 1235.47  5239.4 1235.14  5307.6 1236.97
  5366.2 1237.38  5439.0 1237.97  5467.6 1239.02  5493.0 1240.19  5542.6 1240.89
  5580.6 1241.23  5604.1 1240.60  5670.4 1243.21  5680.7 1243.31  5682.3 1243.44
#Mann=11,-1,0
  4524.4    0.07       0  4548.7    0.12       0  4891.7    0.07       0
  4978.0    0.05       0  4982.0    0.07       0  5182.7    0.12       0
  5239.4    0.07       0  5366.2    0.12       0  5467.6    0.07       0
  5670.4   0.035       0  5680.7    0.07       0
Bank Sta=4978,4982
Exp/Cntr=0.3,0.1

Type RM Length L Ch R = 1,5993,583,583,583
BEGIN DESCRIPTION:
Stream0187_DS 2.0
END DESCRIPTION:
XS GIS Cut Line= 3
      2116729.02     13891196.16      2116725.00     13890975.00
      2116617.91     13890275.96
#Sta/Elev= 30
  4778.8 1230.67  4820.0 1231.09  4860.0 1230.24  4910.0 1227.31  4930.0 1224.57
  4950.0 1223.08  4960.0 1223.02  4970.0 1222.10  4988.0 1221.52  4988.2 1221.02
  4991.7 1221.02  4992.0 1221.52  5009.7 1222.20  5160.9 1223.75  5166.0 1224.44
  5202.3 1223.39  5222.6 1223.67  5297.8 1227.13  5303.5 1228.14  5323.7 1229.56
  5347.1 1230.11  5394.6 1231.25  5485.6 1232.33  5498.0 1233.11  5526.1 1232.84
  5546.3 1233.65  5586.8 1233.54  5607.0 1234.22  5687.3 1234.62  5707.2 1234.97
#Mann=6,-1,0
  4778.8    0.07       0  4988.0    0.05       0  4992.0    0.07       0
  5009.7    0.12       0  5347.1    0.07       0  5687.3   0.035       0
Bank Sta=4988,4992
Exp/Cntr=0.3,0.1

Type RM Length L Ch R = 1,5410,0,0,0
BEGIN DESCRIPTION:
Stream0187_DS 1.0
END DESCRIPTION:
XS GIS Cut Line= 3
      2116937.37     13891244.70      2117175.00     13890825.00
      2117201.19     13890328.99
#Sta/Elev= 30
  4517.7 1229.49  4582.2 1228.97  4658.5 1229.44  4668.8 1229.22  4684.7 1227.21
  4690.4 1227.41  4765.5 1223.28  4815.9 1221.54  4873.7 1218.37  4964.7 1216.08
  4990.1 1214.76  4990.3 1214.26  4993.8 1214.26  4994.1 1214.76  5010.0 1214.87
  5060.1 1219.20  5070.1 1220.91  5095.0 1221.71  5150.2 1226.70  5220.3 1226.98
  5279.9 1228.51  5300.4 1226.64  5310.4 1227.43  5340.5 1226.50  5360.5 1227.34
  5374.4 1226.85  5440.6 1228.65  5472.8 1228.70  5480.7 1229.26  5496.7 1228.90
#Mann=7,-1,0
  4517.7    0.07       0  4658.5   0.035       0  4815.9    0.07       0
  4990.1    0.05       0  4994.1    0.07       0  5374.4   0.035       0
  5472.8    0.12       0
Bank Sta=4990.1,4994.1
Exp/Cntr=0.3,0.1

Chan Stop Cuts=-1