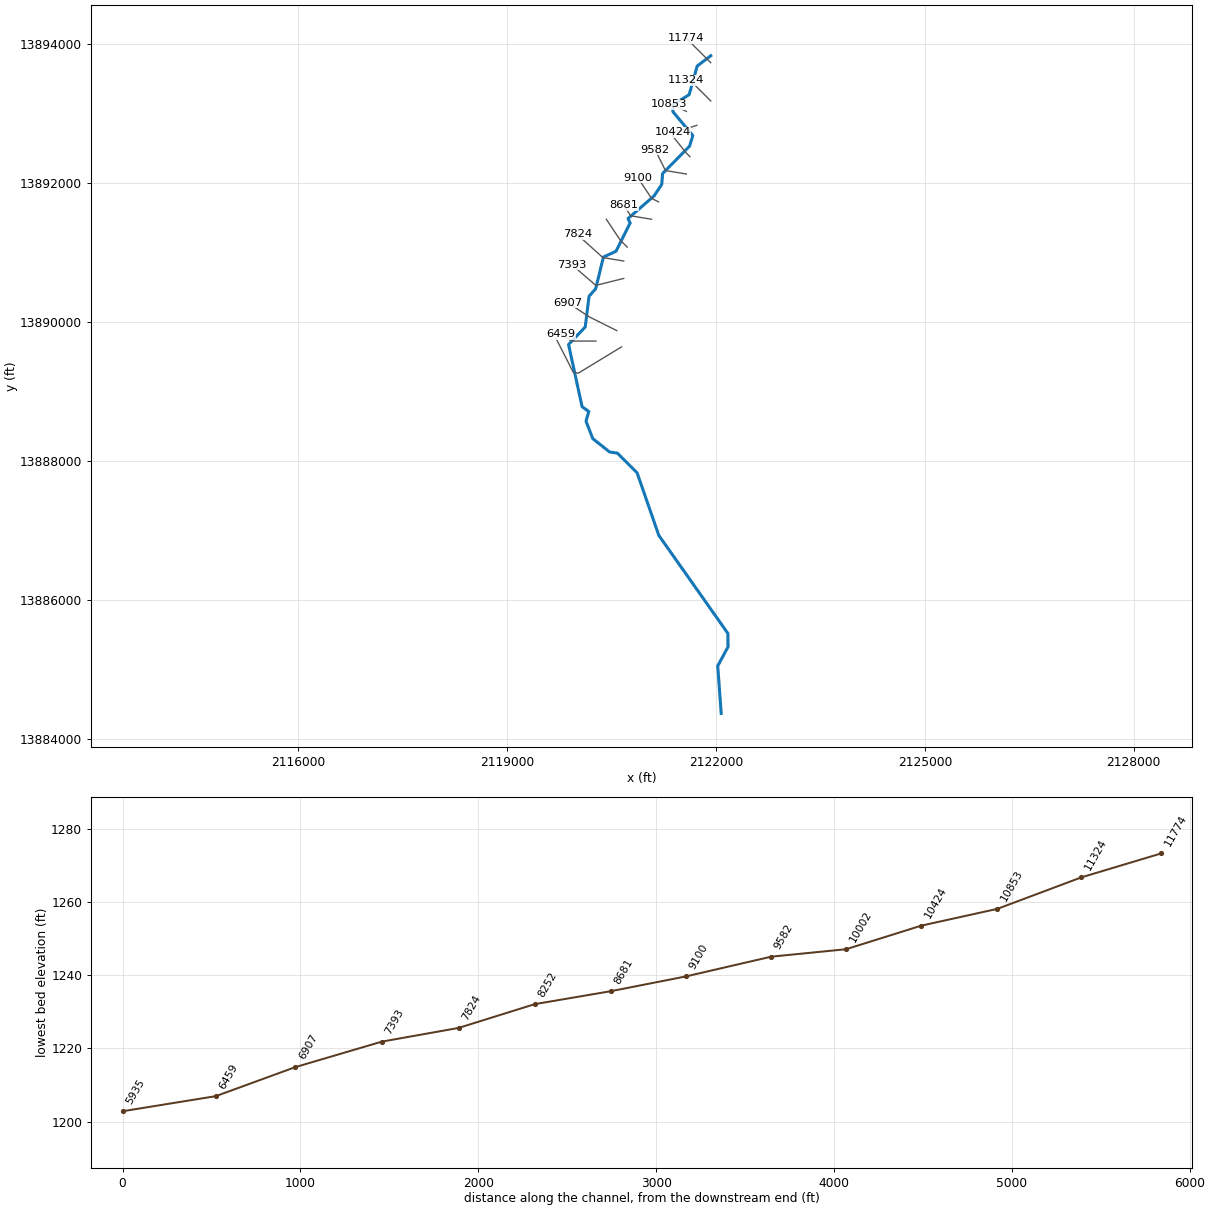
--- Stream0188_DS.prj (project) ---

Proj Title=Stream0188_DS Base Level Engineering
Current Plan=p01
Default Exp/Contr=0.3,0.1
English Units
Geom File=g01
Flow File=f01
Plan File=p01
BEGIN DESCRIPTION:
Stream0188_DS
END DESCRIPTION:

--- Stream0188_DS.p01 (plan) ---

Plan Title=Multiple Run
Short Identifier=Multiple
Geom File=g01
Flow File=f01
Subcritical Flow
K Sum by GR= 0
Std Step Tol= 0.01
Critical Tol= 0.01
Num of Std Step Trials= 20
Max Error Tol= 0.3
Flow Tol Ratio= 0.001
Split Flow NTrial= 30
Split Flow Tol= 0.02
Split Flow Ratio= 0.02
Log Output Level= 0
Friction Slope Method= 1
Unsteady Friction Slope Method= 2
Unsteady Bridges Friction Slope Method= 1
Parabolic Critical Depth
Global Vel Dist=  1 , 1 , 1
Global Log Level= 0
CheckData=True
Encroach Param= -1, 0, 0, 0
BEGIN DESCRIPTION:
Multiple Run
END DESCRIPTION:

--- Stream0188_DS.f01 (steady flow) ---

Flow Title=Multiple
Number of Profiles=7
Profile Names=10-year,25-year,50-year,1pct_min,100-year,1pct_plu,500-year
River Rch & RM= Stream0188_DS,Reach-1,11774
    1060    1778    2454    1640    3273    6530    5758
River Rch & RM= Stream0188_DS,Reach-1,7393
    1335    2257    3129    2099    4188    8357    7424
Boundary for River Rch & Prof#=Stream0188_DS,Reach-1,1
Up Type=0
Dn Type=3
Dn Slope=0.005
Boundary for River Rch & Prof#=Stream0188_DS,Reach-1,2
Up Type=0
Dn Type=3
Dn Slope=0.005
Boundary for River Rch & Prof#=Stream0188_DS,Reach-1,3
Up Type=0
Dn Type=3
Dn Slope=0.005
Boundary for River Rch & Prof#=Stream0188_DS,Reach-1,4
Up Type=0
Dn Type=3
Dn Slope=0.005
Boundary for River Rch & Prof#=Stream0188_DS,Reach-1,5
Up Type=0
Dn Type=3
Dn Slope=0.005
Boundary for River Rch & Prof#=Stream0188_DS,Reach-1,6
Up Type=0
Dn Type=3
Dn Slope=0.005
Boundary for River Rch & Prof#=Stream0188_DS,Reach-1,7
Up Type=0
Dn Type=3
Dn Slope=0.005

--- Stream0188_DS.g01 (geometry) ---

Geom Title=Existing Conditions

River Reach=Stream0188_DS,Reach-1
Reach XY= 30
      2121925.00     13893825.00      2121730.82     13893677.31
      2121614.39     13893264.94      2121376.96     13893119.12
      2121382.78     13893018.84      2121666.98     13892678.35
      2121621.19     13892526.56      2121232.74     13892131.46
      2121221.45     13891976.47      2121111.51     13891811.44
      2120736.23     13891485.02      2120766.98     13891421.67
      2120564.24     13891015.27      2120383.14     13890931.68
      2120271.38     13890476.50      2120177.18     13890369.55
      2120121.39     13889926.50      2119882.31     13889675.10
      2120077.02     13888780.69      2120173.47     13888713.12
      2120132.56     13888575.00      2120230.73     13888322.45
      2120472.57     13888130.52      2120584.79     13888114.48
      2120867.18     13887831.19      2121178.57     13886933.15
      2122171.45     13885523.53      2122172.94     13885330.86
      2122025.05     13885056.67      2122075.00     13884375.00

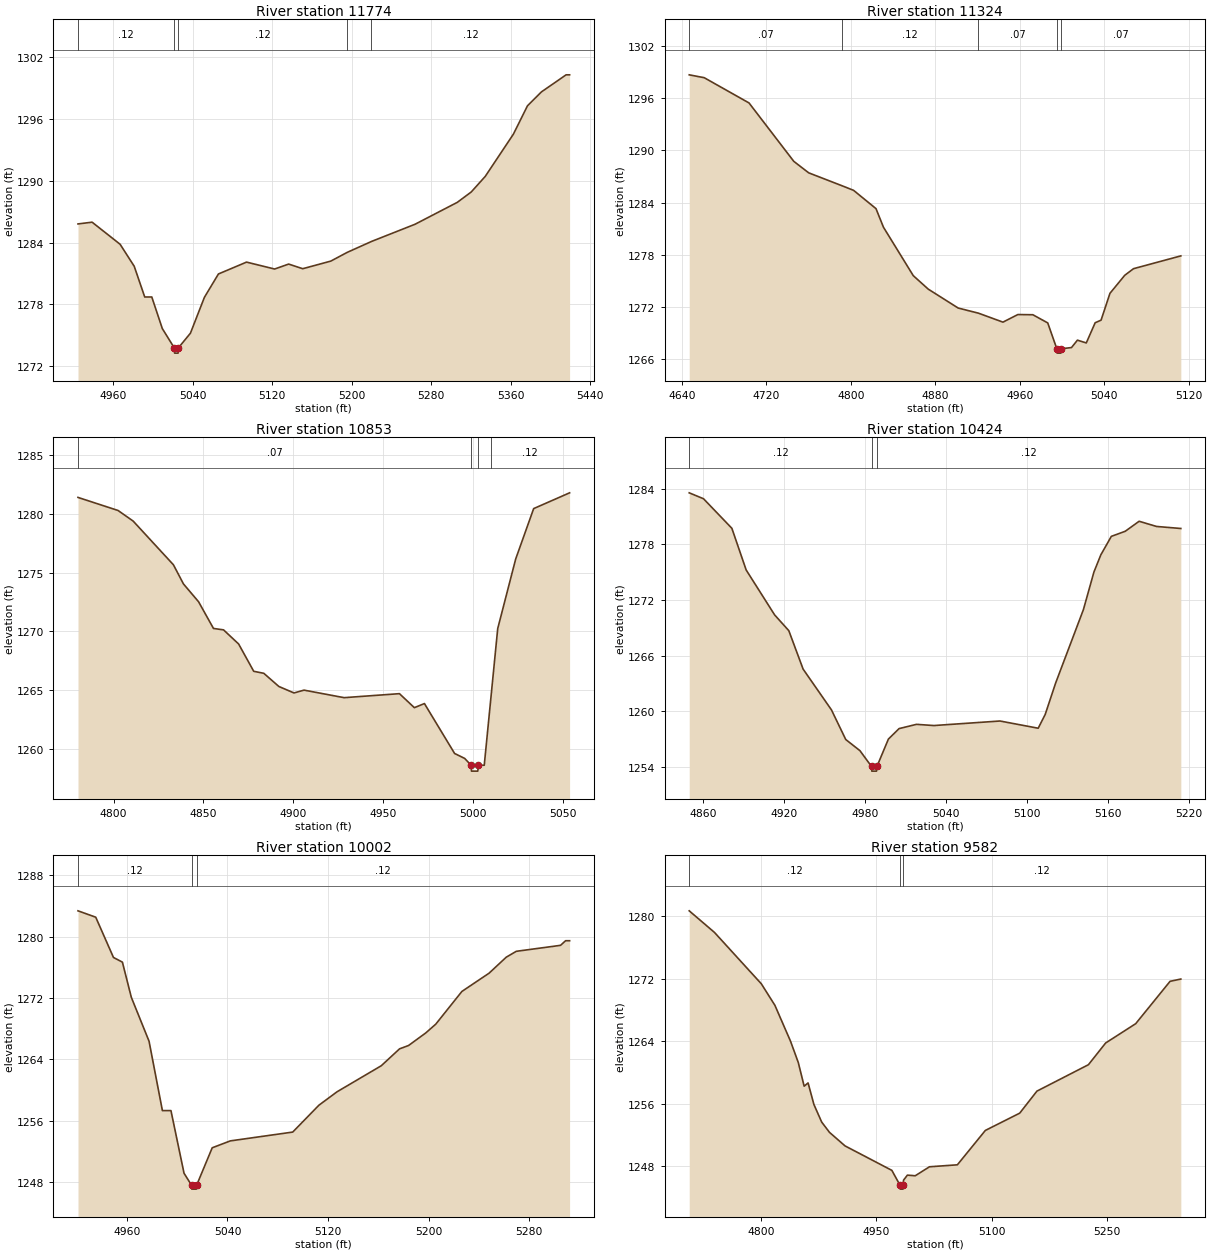
Type RM Length L Ch R = 1,11774,450,450,450
BEGIN DESCRIPTION:
Stream0188_DS 14.0
END DESCRIPTION:
XS GIS Cut Line= 3
      2121925.01     13893724.99      2121875.00     13893775.00
      2121574.99     13894075.01
#Sta/Elev= 30
  4924.5 1285.80  4938.7 1285.97  4966.9 1283.83  4981.1 1281.70  4991.7 1278.72
  4998.8 1278.72  5009.4 1275.66  5021.5 1273.78  5021.8 1273.28  5025.3 1273.28
  5025.5 1273.78  5037.7 1275.21  5051.8 1278.69  5065.9 1280.95  5094.2 1282.10
  5122.5 1281.43  5136.6 1281.91  5150.8 1281.46  5179.1 1282.20  5195.5 1283.04
  5220.0 1284.10  5263.9 1285.77  5306.4 1287.89  5320.5 1288.90  5334.6 1290.41
  5362.9 1294.50  5377.1 1297.25  5391.2 1298.60  5416.0 1300.25  5419.5 1300.25
#Mann=5,-1,0
  4924.5    0.12       0  5021.5    0.05       0  5025.5    0.12       0
  5195.5   0.035       0  5220.0    0.12       0
Bank Sta=5021.5,5025.5
Exp/Cntr=0.3,0.1

Type RM Length L Ch R = 1,11324,471,471,471
BEGIN DESCRIPTION:
Stream0188_DS 13.0
END DESCRIPTION:
XS GIS Cut Line= 3
      2121925.01     13893174.99      2121675.00     13893425.00
      2121574.97     13893475.01
#Sta/Elev= 30
  4647.0 1298.69  4661.2 1298.36  4703.6 1295.46  4746.0 1288.75  4760.1 1287.43
  4791.6 1285.95  4802.6 1285.42  4823.8 1283.32  4830.9 1281.18  4859.1 1275.62
  4873.3 1274.07  4901.6 1271.90  4920.8 1271.31  4944.0 1270.28  4958.1 1271.15
  4972.3 1271.13  4986.4 1270.19  4995.0 1267.22  4995.3 1266.72  4998.8 1266.72
  4999.0 1267.22  5008.9 1267.36  5014.5 1268.21  5022.9 1267.89  5031.3 1270.21
  5036.9 1270.51  5045.3 1273.59  5059.3 1275.66  5067.6 1276.42  5112.4 1277.89
#Mann=5,-1,0
  4647.0    0.07       0  4791.6    0.12       0  4920.8    0.07       0
  4995.0    0.05       0  4999.0    0.07       0
Bank Sta=4995,4999
Exp/Cntr=0.3,0.1

Type RM Length L Ch R = 1,10853,429,429,429
BEGIN DESCRIPTION:
Stream0188_DS 12.0
END DESCRIPTION:
XS GIS Cut Line= 3
      2121574.98     13893025.01      2121375.00     13893125.00
      2121324.98     13893125.00
#Sta/Elev= 30
  4780.2 1281.38  4802.5 1280.27  4810.9 1279.37  4833.3 1275.66  4838.9 1274.03
  4847.3 1272.52  4855.6 1270.25  4861.2 1270.13  4869.6 1268.93  4878.0 1266.61
  4883.6 1266.44  4892.0 1265.32  4900.4 1264.77  4906.0 1265.01  4928.3 1264.37
  4959.1 1264.71  4967.4 1263.52  4973.0 1263.87  4989.8 1259.63  4995.4 1259.21
  4999.0 1258.63  4999.2 1258.13  5002.7 1258.13  5003.0 1258.63  5006.3 1258.63
  5009.9 1264.20  5013.8 1270.24  5023.8 1276.15  5033.8 1280.43  5053.8 1281.77
#Mann=4,-1,0
  4780.2    0.07       0  4999.0    0.05       0  5003.0    0.07       0
  5009.9    0.12       0
Bank Sta=4999,5003
Exp/Cntr=0.3,0.1

Type RM Length L Ch R = 1,10424,422,422,422
BEGIN DESCRIPTION:
Stream0188_DS 11.0
END DESCRIPTION:
XS GIS Cut Line= 3
      2121725.02     13892825.01      2121575.00     13892775.00
      2121374.99     13892725.00
#Sta/Elev= 30
  4849.7 1283.56  4860.3 1282.92  4881.3 1279.73  4891.9 1275.23  4913.0 1270.38
  4923.5 1268.68  4934.1 1264.53  4955.1 1260.13  4965.7 1256.93  4976.2 1255.73
  4984.8 1254.02  4985.0 1253.52  4988.5 1253.52  4988.8 1254.02  4997.3 1256.98
  5005.2 1258.11  5018.1 1258.57  5031.0 1258.44  5080.0 1258.93  5108.3 1258.15
  5113.5 1259.64  5121.2 1263.02  5141.8 1270.95  5149.6 1275.01  5154.7 1276.86
  5162.5 1278.86  5172.8 1279.41  5183.1 1280.49  5196.0 1279.93  5214.0 1279.71
#Mann=3,-1,0
  4849.7    0.12       0  4984.8    0.05       0  4988.8    0.12       0
Bank Sta=4984.8,4988.8
Exp/Cntr=0.3,0.1

Type RM Length L Ch R = 1,10002,420,420,420
BEGIN DESCRIPTION:
Stream0188_DS 10.0
END DESCRIPTION:
XS GIS Cut Line= 3
      2121624.97     13892375.03      2121575.00     13892425.00
      2121375.01     13892674.99
#Sta/Elev= 30
  4921.2 1283.38  4935.3 1282.55  4949.4 1277.30  4956.5 1276.69  4963.6 1272.10
  4977.7 1266.37  4988.3 1257.33  4995.1 1257.33  5005.5 1249.16  5011.5 1247.59
  5011.7 1247.09  5015.2 1247.09  5015.5 1247.59  5027.9 1252.48  5042.3 1253.38
  5091.9 1254.53  5112.7 1258.03  5127.1 1259.78  5162.3 1263.18  5176.8 1265.38
  5184.0 1265.82  5197.6 1267.45  5205.6 1268.60  5226.4 1272.87  5248.0 1275.25
  5261.6 1277.33  5269.6 1278.10  5304.8 1278.88  5308.8 1279.48  5312.0 1279.48
#Mann=3,-1,0
  4921.2    0.12       0  5011.5    0.05       0  5015.5    0.12       0
Bank Sta=5011.5,5015.5
Exp/Cntr=0.3,0.1

Type RM Length L Ch R = 1,9582,482,482,482
BEGIN DESCRIPTION:
Stream0188_DS 9.0
END DESCRIPTION:
XS GIS Cut Line= 3
      2121574.98     13892125.00      2121275.00     13892175.00
      2121125.01     13892474.98
#Sta/Elev= 30
  4706.4 1280.67  4739.3 1277.90  4800.2 1271.33  4817.9 1268.57  4838.2 1263.98
  4848.3 1261.25  4855.9 1258.23  4861.0 1258.65  4868.6 1255.89  4878.7 1253.64
  4888.9 1252.32  4909.1 1250.59  4970.0 1247.46  4980.6 1245.56  4980.9 1245.06
  4984.4 1245.06  4984.6 1245.56  4985.2 1246.21  4990.2 1246.85  5000.4 1246.77
  5018.9 1247.92  5055.2 1248.17  5091.6 1252.57  5136.3 1254.78  5158.7 1257.60
  5225.7 1260.98  5248.1 1263.76  5287.2 1266.23  5331.9 1271.65  5345.9 1271.94
#Mann=3,-1,0
  4706.4    0.12       0  4980.6    0.05       0  4984.6    0.12       0
Bank Sta=4980.6,4984.6
Exp/Cntr=0.3,0.1

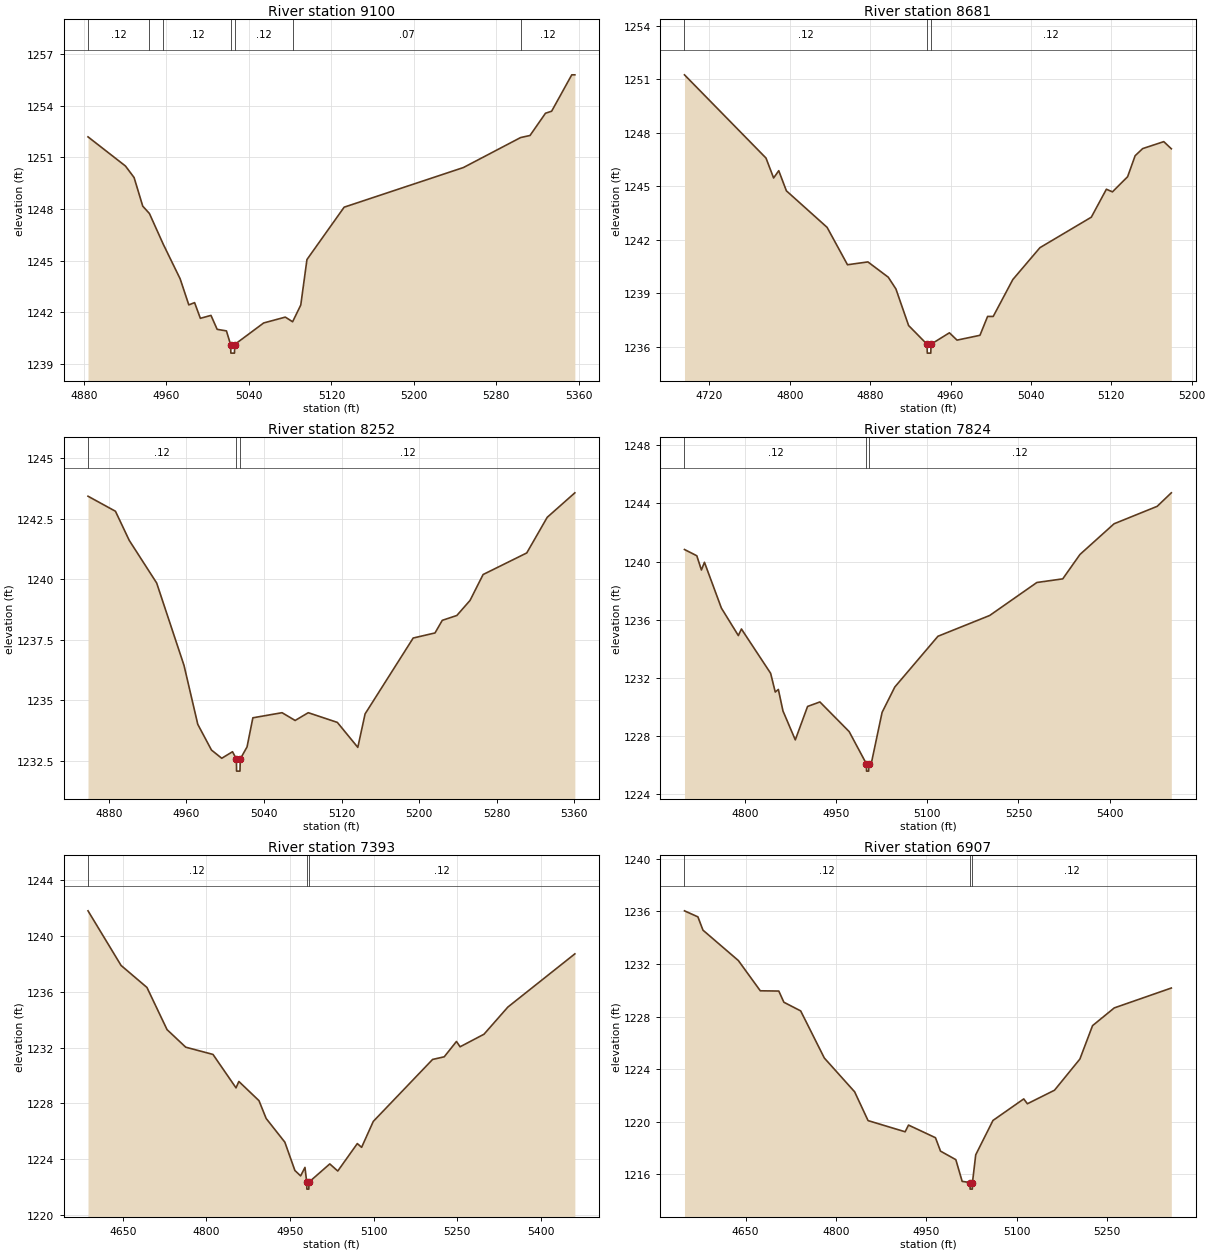
Type RM Length L Ch R = 1,9100,419,419,419
BEGIN DESCRIPTION:
Stream0188_DS 8.0
END DESCRIPTION:
XS GIS Cut Line= 3
      2121174.97     13891725.01      2121075.00     13891775.00
      2120875.02     13892074.98
#Sta/Elev= 30
  4883.9 1252.19  4920.2 1250.50  4928.6 1249.83  4937.0 1248.17  4943.5 1247.74
  4956.9 1245.96  4973.3 1243.95  4981.7 1242.44  4987.3 1242.57  4992.9 1241.66
  5003.2 1241.83  5009.2 1241.02  5018.2 1240.93  5022.2 1240.14  5022.5 1239.64
  5026.0 1239.64  5026.2 1240.14  5054.3 1241.39  5075.3 1241.73  5082.4 1241.46
  5090.3 1242.43  5096.3 1245.07  5132.4 1248.11  5248.1 1250.41  5303.6 1252.15
  5312.7 1252.27  5327.7 1253.56  5333.7 1253.68  5353.2 1255.79  5356.2 1255.79
#Mann=7,-1,0
  4883.9    0.12       0  4943.5    0.07       0  4956.9    0.12       0
  5022.2    0.05       0  5026.2    0.12       0  5082.4    0.07       0
  5303.6    0.12       0
Bank Sta=5022.2,5026.2
Exp/Cntr=0.3,0.1

Type RM Length L Ch R = 1,8681,429,429,429
BEGIN DESCRIPTION:
Stream0188_DS 7.0
END DESCRIPTION:
XS GIS Cut Line= 3
      2121075.01     13891475.00      2120775.00     13891525.00
      2120675.01     13891674.98
#Sta/Elev= 30
  4695.3 1251.25  4776.4 1246.58  4784.0 1245.46  4789.1 1245.87  4796.7 1244.74
  4837.2 1242.69  4857.5 1240.59  4877.8 1240.75  4898.1 1239.89  4905.7 1239.23
  4918.3 1237.18  4936.6 1236.13  4936.9 1235.63  4940.4 1235.63  4940.6 1236.13
  4958.9 1236.77  4966.5 1236.36  4989.3 1236.63  4996.9 1237.69  5002.5 1237.69
  5022.0 1239.76  5049.0 1241.55  5100.1 1243.26  5115.1 1244.83  5121.1 1244.68
  5136.2 1245.53  5143.7 1246.71  5151.2 1247.11  5172.2 1247.50  5179.7 1247.10
#Mann=3,-1,0
  4695.3    0.12       0  4936.6    0.05       0  4940.6    0.12       0
Bank Sta=4936.6,4940.6
Exp/Cntr=0.3,0.1

Type RM Length L Ch R = 1,8252,428,428,428
BEGIN DESCRIPTION:
Stream0188_DS 6.0
END DESCRIPTION:
XS GIS Cut Line= 3
      2120725.03     13891074.97      2120625.00     13891175.00
      2120425.01     13891474.98
#Sta/Elev= 30
  4858.5 1243.42  4886.8 1242.80  4901.0 1241.60  4929.3 1239.84  4957.5 1236.44
  4971.7 1234.01  4985.8 1232.95  4996.4 1232.61  5007.5 1232.88  5011.5 1232.58
  5011.7 1232.08  5015.2 1232.08  5015.5 1232.58  5022.5 1233.08  5028.5 1234.28
  5058.6 1234.49  5072.1 1234.17  5085.6 1234.49  5115.6 1234.09  5136.7 1233.06
  5144.2 1234.44  5193.8 1237.57  5216.3 1237.78  5223.8 1238.30  5238.8 1238.50
  5252.4 1239.12  5265.9 1240.19  5310.9 1241.08  5332.0 1242.55  5360.5 1243.56
#Mann=3,-1,0
  4858.5    0.12       0  5011.5    0.05       0  5015.5    0.12       0
Bank Sta=5011.5,5015.5
Exp/Cntr=0.3,0.1

Type RM Length L Ch R = 1,7824,431,431,431
BEGIN DESCRIPTION:
Stream0188_DS 5.0
END DESCRIPTION:
XS GIS Cut Line= 3
      2120674.99     13890875.00      2120375.00     13890925.00
      2120004.87     13891257.54
#Sta/Elev= 30
  4700.1 1240.83  4720.4 1240.40  4728.0 1239.42  4733.0 1239.95  4760.9 1236.80
  4788.8 1234.91  4793.9 1235.36  4842.0 1232.31  4849.6 1231.02  4854.7 1231.20
  4862.3 1229.72  4882.6 1227.73  4902.8 1230.03  4923.1 1230.34  4971.3 1228.30
  4999.7 1226.08  4999.9 1225.58  5003.4 1225.58  5003.7 1226.08  5007.6 1226.08
  5025.5 1229.62  5046.5 1231.37  5117.5 1234.86  5202.7 1236.29  5280.4 1238.56
  5323.0 1238.81  5351.4 1240.49  5407.5 1242.60  5478.5 1243.80  5501.8 1244.73
#Mann=3,-1,0
  4700.1    0.12       0  4999.7    0.05       0  5003.7    0.12       0
Bank Sta=4999.7,5003.7
Exp/Cntr=0.3,0.1

Type RM Length L Ch R = 1,7393,486,486,486
BEGIN DESCRIPTION:
Stream0188_DS 4.0
END DESCRIPTION:
XS GIS Cut Line= 3
      2120675.04     13890625.01      2120275.00     13890525.00
      2119925.02     13890824.98
#Sta/Elev= 30
  4587.7 1241.82  4647.0 1237.90  4693.4 1236.32  4729.5 1233.29  4763.0 1232.03
  4811.9 1231.51  4853.2 1229.11  4858.3 1229.57  4894.4 1228.19  4907.3 1226.91
  4940.8 1225.21  4958.8 1223.18  4969.1 1222.79  4976.9 1223.40  4980.0 1222.34
  4980.3 1221.84  4983.8 1221.84  4984.0 1222.34  5021.4 1223.65  5035.7 1223.14
  5070.8 1225.11  5078.5 1224.84  5099.4 1226.70  5205.8 1231.15  5226.7 1231.34
  5248.6 1232.44  5255.2 1232.06  5298.0 1232.96  5340.8 1234.91  5461.0 1238.73
#Mann=3,-1,0
  4587.7    0.12       0  4980.0    0.05       0  4984.0    0.12       0
Bank Sta=4980,4984
Exp/Cntr=0.3,0.1

Type RM Length L Ch R = 1,6907,448,448,448
BEGIN DESCRIPTION:
Stream0188_DS 3.0
END DESCRIPTION:
XS GIS Cut Line= 3
      2120574.98     13889875.01      2120175.00     13890075.00
      2119875.04     13890274.98
#Sta/Elev= 30
  4548.6 1236.04  4570.9 1235.58  4579.3 1234.57  4638.0 1232.26  4674.4 1229.96
  4705.1 1229.94  4713.5 1229.09  4741.4 1228.43  4780.6 1224.85  4830.9 1222.28
  4853.2 1220.09  4914.7 1219.24  4920.3 1219.75  4965.0 1218.79  4973.4 1217.77
  4998.8 1217.12  5009.3 1215.47  5022.3 1215.38  5022.5 1214.88  5026.1 1214.88
  5026.4 1215.38  5031.8 1217.49  5060.4 1220.10  5111.5 1221.74  5117.5 1221.37
  5162.5 1222.40  5204.6 1224.77  5225.6 1227.31  5261.7 1228.66  5356.3 1230.17
#Mann=3,-1,0
  4548.6    0.12       0  5022.3    0.05       0  5026.4    0.12       0
Bank Sta=5022.3,5026.4
Exp/Cntr=0.3,0.1

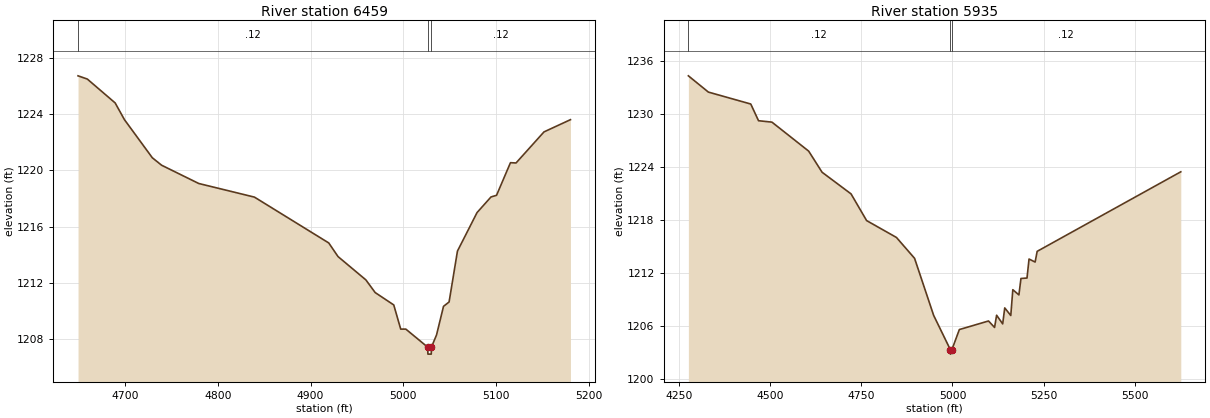
Type RM Length L Ch R = 1,6459,524,524,524
BEGIN DESCRIPTION:
Stream0188_DS 2.0
END DESCRIPTION:
XS GIS Cut Line= 3
      2120275.04     13889725.00      2119925.00     13889725.00
      2119775.02     13889824.99
#Sta/Elev= 30
  4649.6 1226.73  4659.6 1226.50  4689.6 1224.80  4699.6 1223.61  4729.6 1220.90
  4739.6 1220.37  4779.6 1219.07  4839.6 1218.10  4919.6 1214.84  4929.6 1213.87
  4959.6 1212.21  4969.6 1211.31  4989.6 1210.43  4997.1 1208.71  5002.6 1208.71
  5026.1 1207.43  5026.4 1206.93  5030.0 1206.93  5030.2 1207.43  5035.7 1208.30
  5043.2 1210.33  5049.2 1210.64  5058.2 1214.26  5079.3 1217.00  5094.3 1218.11
  5100.3 1218.23  5115.3 1220.55  5121.3 1220.53  5151.4 1222.74  5179.9 1223.61
#Mann=3,-1,0
  4649.6    0.12       0  5026.1    0.05       0  5030.2    0.12       0
Bank Sta=5026.1,5030.2
Exp/Cntr=0.3,0.1

Type RM Length L Ch R = 1,5935,0,0,0
BEGIN DESCRIPTION:
Stream0188_DS 1.0
END DESCRIPTION:
XS GIS Cut Line= 4
      2120642.88     13889641.01      2120023.78     13889264.50
      2119949.75     13889276.33      2119699.59     13889767.97
#Sta/Elev= 30
  4275.4 1234.30  4330.3 1232.46  4446.6 1231.11  4467.9 1229.22  4504.7 1229.06
  4605.5 1225.78  4642.3 1223.39  4721.8 1220.94  4764.5 1217.92  4846.4 1216.01
  4896.1 1213.65  4948.4 1207.20  4994.3 1203.31  4994.6 1202.81  4998.5 1203.31
  5019.0 1205.59  5099.0 1206.56  5115.6 1205.83  5121.2 1207.21  5137.9 1206.23
  5143.5 1208.04  5160.1 1207.18  5165.7 1210.10  5182.4 1209.51  5188.0 1211.37
  5204.6 1211.42  5210.2 1213.57  5226.9 1213.23  5232.5 1214.44  5626.6 1223.44
#Mann=3,-1,0
  4275.4    0.12       0  4994.3    0.05       0  4998.5    0.12       0
Bank Sta=4994.3,4998.5
Exp/Cntr=0.3,0.1

Chan Stop Cuts=-1