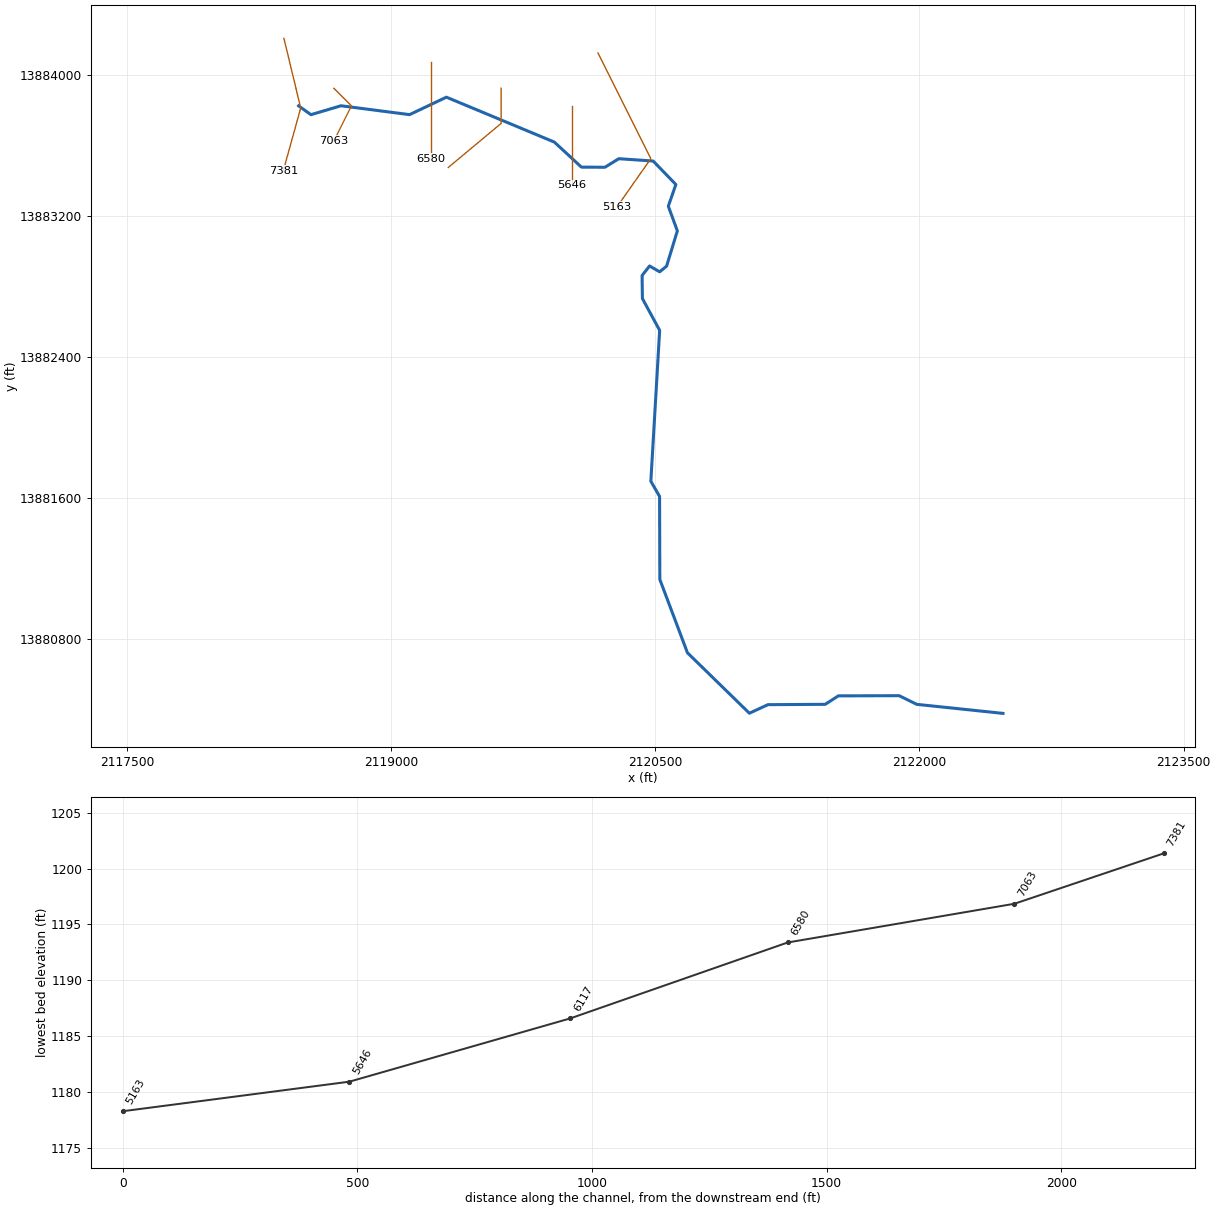
--- Stream0189_DS.prj (project) ---

Proj Title=Stream0189_DS Base Level Engineering
Current Plan=p01
Default Exp/Contr=0.3,0.1
English Units
Geom File=g01
Flow File=f01
Plan File=p01
BEGIN DESCRIPTION:
Stream0189_DS
END DESCRIPTION:

--- Stream0189_DS.p01 (plan) ---

Plan Title=Multiple Run
Short Identifier=Multiple
Geom File=g01
Flow File=f01
Subcritical Flow
K Sum by GR= 0
Std Step Tol= 0.01
Critical Tol= 0.01
Num of Std Step Trials= 20
Max Error Tol= 0.3
Flow Tol Ratio= 0.001
Split Flow NTrial= 30
Split Flow Tol= 0.02
Split Flow Ratio= 0.02
Log Output Level= 0
Friction Slope Method= 1
Unsteady Friction Slope Method= 2
Unsteady Bridges Friction Slope Method= 1
Parabolic Critical Depth
Global Vel Dist=  1 , 1 , 1
Global Log Level= 0
CheckData=True
Encroach Param= -1, 0, 0, 0
BEGIN DESCRIPTION:
Multiple Run
END DESCRIPTION:

--- Stream0189_DS.f01 (steady flow) ---

Flow Title=Multiple
Number of Profiles=7
Profile Names=10-year,25-year,50-year,1pct_min,100-year,1pct_plu,500-year
River Rch & RM= Stream0189_DS,Reach-1,7381
     639    1047    1423     940    1876    3743    3219
River Rch & RM= Stream0189_DS,Reach-1,7063
     888    1484    2043    1363    2720    5427    4770
Boundary for River Rch & Prof#=Stream0189_DS,Reach-1,1
Up Type=0
Dn Type=3
Dn Slope=0.005
Boundary for River Rch & Prof#=Stream0189_DS,Reach-1,2
Up Type=0
Dn Type=3
Dn Slope=0.005
Boundary for River Rch & Prof#=Stream0189_DS,Reach-1,3
Up Type=0
Dn Type=3
Dn Slope=0.005
Boundary for River Rch & Prof#=Stream0189_DS,Reach-1,4
Up Type=0
Dn Type=3
Dn Slope=0.005
Boundary for River Rch & Prof#=Stream0189_DS,Reach-1,5
Up Type=0
Dn Type=3
Dn Slope=0.005
Boundary for River Rch & Prof#=Stream0189_DS,Reach-1,6
Up Type=0
Dn Type=3
Dn Slope=0.005
Boundary for River Rch & Prof#=Stream0189_DS,Reach-1,7
Up Type=0
Dn Type=3
Dn Slope=0.005

--- Stream0189_DS.g01 (geometry) ---

Geom Title=Existing Conditions

River Reach=Stream0189_DS,Reach-1
Reach XY= 30
      2118475.00     13883825.00      2118545.08     13883774.78
      2118715.72     13883825.45      2119104.97     13883775.04
      2119314.31     13883874.24      2119927.30     13883619.17
      2120080.86     13883477.05      2120214.49     13883476.21
      2120293.27     13883524.79      2120488.32     13883511.63
      2120617.20     13883378.42      2120574.42     13883254.96
      2120625.77     13883114.95      2120564.48     13882914.51
      2120525.23     13882882.47      2120468.01     13882915.83
      2120425.52     13882861.42      2120427.34     13882730.52
      2120525.21     13882550.09      2120475.21     13881693.27
      2120524.79     13881606.73      2120526.22     13881135.50
      2120683.14     13880718.94      2121034.78     13880375.75
      2121140.21     13880424.46      2121465.34     13880426.38
      2121540.22     13880474.48      2121885.19     13880475.45
      2121985.50     13880426.22      2122475.00     13880375.00

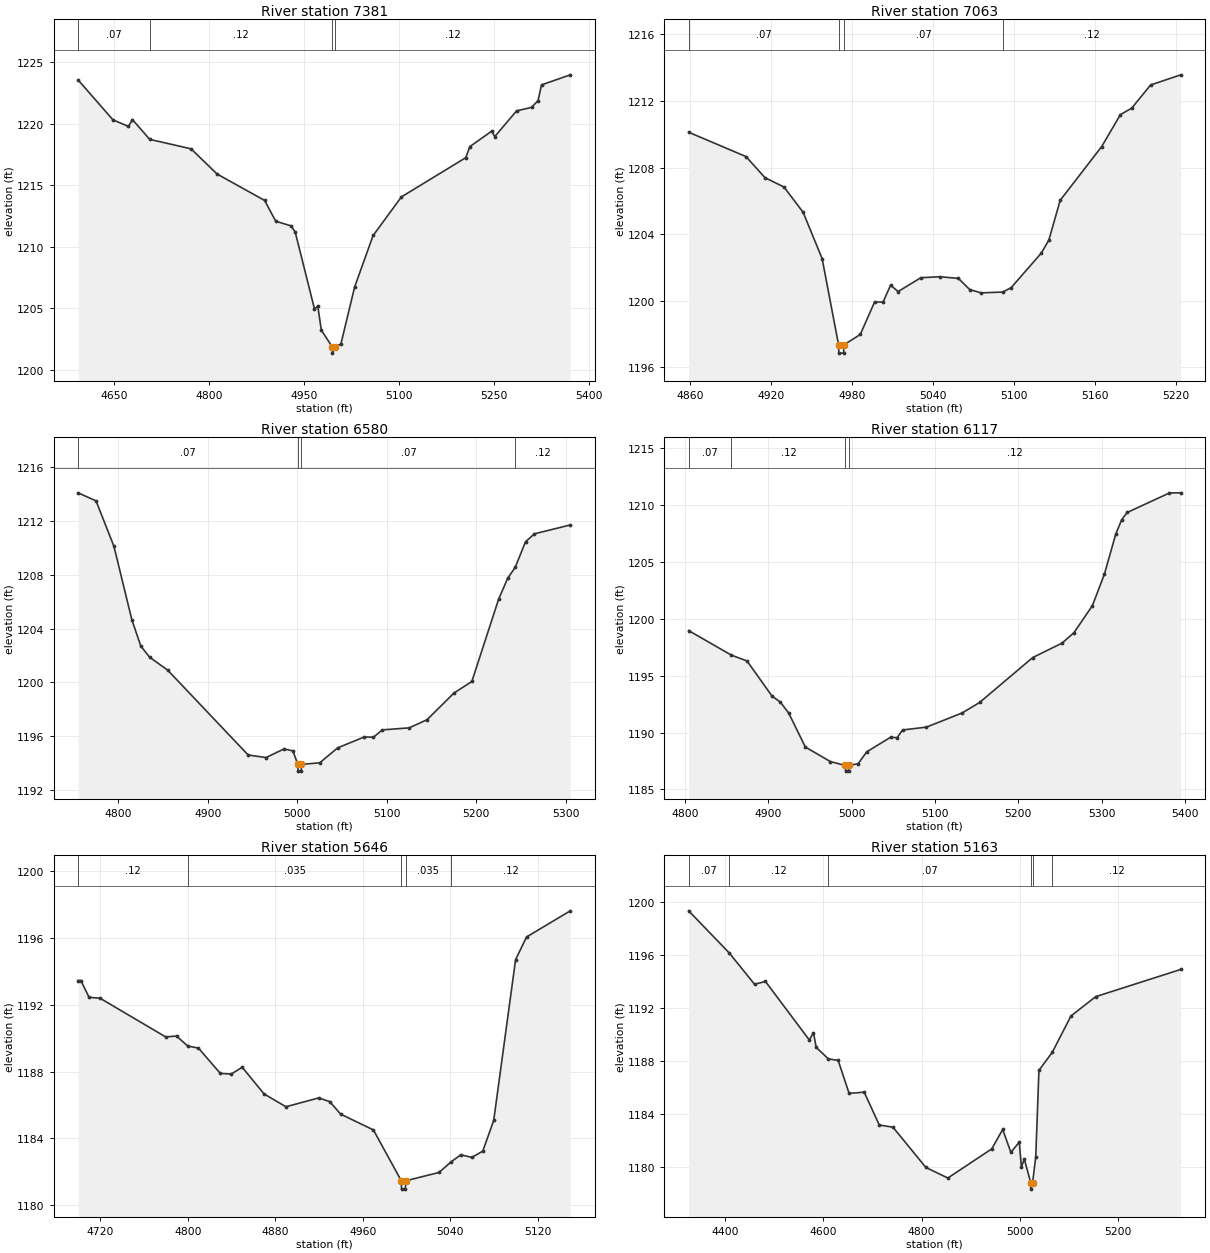
Type RM Length L Ch R = 1,7381,318,318,318
BEGIN DESCRIPTION:
Stream0189_DS 10.0
END DESCRIPTION:
XS GIS Cut Line= 3
      2118391.66     13884208.35      2118486.82     13883812.53
      2118387.95     13883455.98
#Sta/Elev= 30
  4592.9 1223.57  4647.8 1220.33  4672.4 1219.79  4678.6 1220.35  4705.9 1218.74
  4771.2 1217.97  4812.3 1215.92  4887.4 1213.77  4904.9 1212.08  4929.3 1211.70
  4935.7 1211.19  4966.1 1204.94  4971.3 1205.18  4976.9 1203.22  4994.2 1201.85
  4994.4 1201.35  4998.2 1201.85  5007.8 1202.09  5029.6 1206.75  5058.7 1210.92
  5103.4 1214.06  5205.0 1217.25  5211.4 1218.15  5245.7 1219.40  5250.9 1218.97
  5285.2 1221.06  5308.8 1221.34  5319.1 1221.89  5324.6 1223.17  5370.0 1223.99
#Mann=4,-1,0
  4592.9    0.07       0  4705.9    0.12       0  4994.2    0.05       0
  4998.2    0.12       0
Bank Sta=4994.2,4998.2
Exp/Cntr=0.3,0.1

Type RM Length L Ch R = 1,7063,483,483,483
BEGIN DESCRIPTION:
Stream0189_DS 9.0
END DESCRIPTION:
XS GIS Cut Line= 3
      2118674.98     13883925.02      2118775.00     13883825.00
      2118674.98     13883624.96
#Sta/Elev= 30
  4858.7 1210.12  4901.2 1208.66  4915.3 1207.39  4929.4 1206.83  4943.6 1205.31
  4957.7 1202.53  4969.9 1197.35  4970.1 1196.85  4973.6 1196.85  4973.9 1197.35
  4986.0 1197.97  4996.6 1199.92  5002.9 1199.92  5008.5 1200.93  5014.1 1200.55
  5030.9 1201.38  5044.9 1201.44  5058.8 1201.34  5067.2 1200.67  5075.6 1200.47
  5091.8 1200.52  5098.0 1200.79  5120.3 1202.86  5125.9 1203.64  5134.3 1206.03
  5165.1 1209.26  5179.0 1211.18  5187.4 1211.57  5201.4 1212.96  5223.8 1213.57
#Mann=4,-1,0
  4858.7    0.07       0  4969.9    0.05       0  4973.9    0.07       0
  5091.8    0.12       0
Bank Sta=4969.9,4973.9
Exp/Cntr=0.3,0.1

Type RM Length L Ch R = 1,6580,463,463,463
BEGIN DESCRIPTION:
Stream0189_DS 8.0
END DESCRIPTION:
XS GIS Cut Line= 3
      2119225.00     13884074.97      2119225.00     13883825.00
      2119225.00     13883524.97
#Sta/Elev= 30
  4755.1 1214.10  4775.1 1213.50  4795.1 1210.12  4815.1 1204.66  4825.1 1202.70
  4835.1 1201.86  4855.1 1200.91  4945.1 1194.59  4965.1 1194.40  4985.1 1195.04
  4995.1 1194.90  5000.6 1193.89  5000.8 1193.39  5004.3 1193.39  5004.6 1193.89
  5025.1 1194.01  5045.1 1195.12  5075.1 1195.94  5085.1 1195.91  5095.1 1196.46
  5125.1 1196.61  5145.1 1197.22  5175.1 1199.20  5195.1 1200.06  5225.1 1206.20
  5235.1 1207.73  5243.6 1208.56  5255.1 1210.46  5265.1 1211.05  5305.1 1211.71
#Mann=4,-1,0
  4755.1    0.07       0  5000.6    0.05       0  5004.6    0.07       0
  5243.6    0.12       0
Bank Sta=5000.6,5004.6
Exp/Cntr=0.3,0.1

Type RM Length L Ch R = 1,6117,471,471,471
BEGIN DESCRIPTION:
Stream0189_DS 7.0
END DESCRIPTION:
XS GIS Cut Line= 3
      2119625.00     13883925.01      2119625.00     13883725.00
      2119325.02     13883475.02
#Sta/Elev= 30
  4804.6 1198.97  4855.9 1196.81  4874.6 1196.30  4904.6 1193.21  4914.6 1192.68
  4924.6 1191.72  4944.6 1188.73  4974.6 1187.45  4992.6 1187.11  4992.9 1186.61
  4996.4 1186.61  4996.6 1187.11  5007.9 1187.26  5018.3 1188.31  5046.9 1189.59
  5054.7 1189.55  5061.2 1190.23  5089.9 1190.48  5132.8 1191.73  5153.7 1192.65
  5217.4 1196.60  5252.6 1197.87  5266.9 1198.79  5289.0 1201.16  5303.4 1203.93
  5317.0 1207.45  5324.2 1208.73  5330.7 1209.36  5381.5 1211.08  5395.1 1211.09
#Mann=4,-1,0
  4804.6    0.07       0  4855.9    0.12       0  4992.6    0.05       0
  4996.6    0.12       0
Bank Sta=4992.6,4996.6
Exp/Cntr=0.3,0.1

Type RM Length L Ch R = 1,5646,483,483,483
BEGIN DESCRIPTION:
Stream0189_DS 6.0
END DESCRIPTION:
XS GIS Cut Line= 3
      2120025.00     13883824.96      2120025.00     13883525.00
      2120025.00     13883374.96
#Sta/Elev= 30
  4699.7 1193.46  4702.2 1193.46  4709.7 1192.45  4719.7 1192.40  4779.7 1190.08
  4789.7 1190.13  4799.9 1189.53  4809.7 1189.41  4829.7 1187.89  4839.7 1187.85
  4849.7 1188.26  4869.7 1186.66  4889.7 1185.89  4919.7 1186.42  4929.7 1186.20
  4939.7 1185.45  4969.7 1184.50  4995.2 1181.45  4995.4 1180.95  4998.9 1180.95
  4999.2 1181.45  5029.7 1181.95  5040.8 1182.59  5049.7 1183.01  5059.7 1182.85
  5069.7 1183.23  5079.7 1185.07  5099.7 1194.71  5109.7 1196.07  5149.7 1197.64
#Mann=5,-1,0
  4699.7    0.12       0  4799.9   0.035       0  4995.2   0.035       0
  4999.2   0.035       0  5040.8    0.12       0
Bank Sta=4995.2,4999.2
Exp/Cntr=0.3,0.1

Type RM Length L Ch R = 1,5163,0,0,0
BEGIN DESCRIPTION:
Stream0189_DS 5.0
END DESCRIPTION:
XS GIS Cut Line= 3
      2120175.00     13884125.00      2120475.00     13883525.00
      2120284.10     13883252.91
#Sta/Elev= 30
  4325.2 1199.35  4408.0 1196.16  4459.4 1193.80  4481.7 1194.01  4571.2 1189.58
  4579.6 1190.14  4585.1 1189.03  4609.8 1188.16  4629.9 1188.04  4652.2 1185.55
  4683.0 1185.64  4713.7 1183.16  4741.7 1182.99  4808.7 1179.95  4853.5 1179.15
  4942.9 1181.35  4965.3 1182.82  4982.0 1181.09  4999.1 1181.87  5003.4 1180.00
  5009.5 1180.58  5022.3 1178.81  5022.6 1178.31  5026.3 1178.81  5032.7 1180.75
  5039.2 1187.29  5066.3 1188.65  5104.5 1191.40  5154.8 1192.86  5328.4 1194.92
#Mann=6,-1,0
  4325.2    0.07       0  4408.0    0.12       0  4609.8    0.07       0
  5022.3    0.05       0  5026.3    0.07       0  5066.3    0.12       0
Bank Sta=5022.3,5026.3
Exp/Cntr=0.3,0.1

Chan Stop Cuts=-1