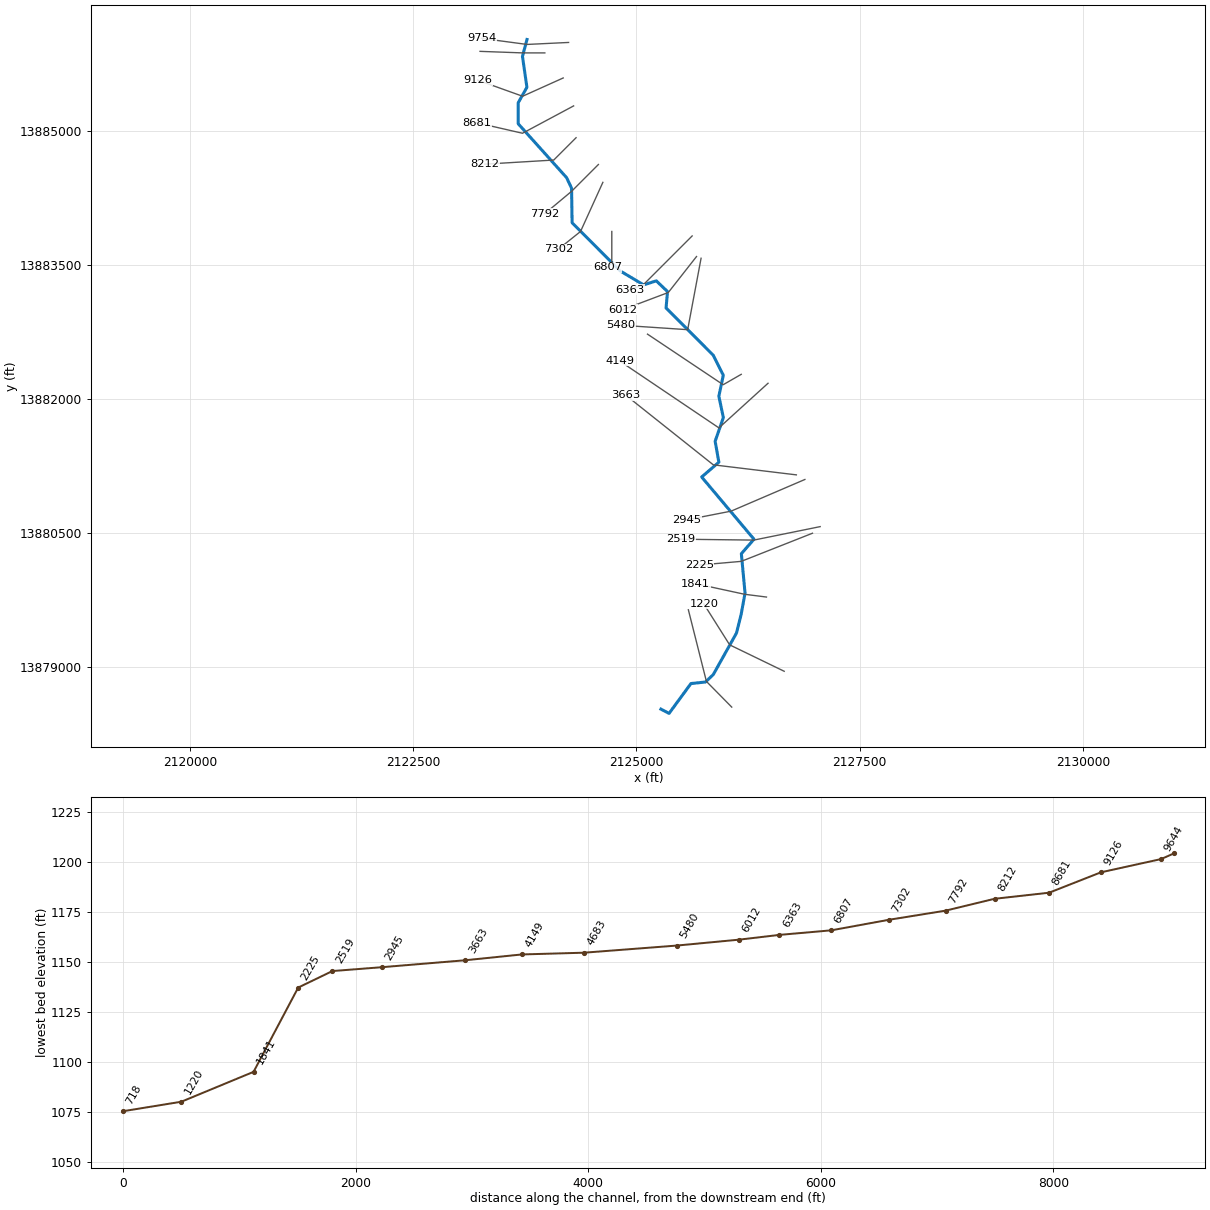
--- Stream0190_DS.prj (project) ---

Proj Title=Stream0190_DS Base Level Engineering
Current Plan=p01
Default Exp/Contr=0.3,0.1
English Units
Geom File=g01
Flow File=f01
Plan File=p01
BEGIN DESCRIPTION:
Stream0190_DS
END DESCRIPTION:

--- Stream0190_DS.p01 (plan) ---

Plan Title=Multiple Run
Short Identifier=Multiple
Geom File=g01
Flow File=f01
Subcritical Flow
K Sum by GR= 0
Std Step Tol= 0.01
Critical Tol= 0.01
Num of Std Step Trials= 20
Max Error Tol= 0.3
Flow Tol Ratio= 0.001
Split Flow NTrial= 30
Split Flow Tol= 0.02
Split Flow Ratio= 0.02
Log Output Level= 0
Friction Slope Method= 1
Unsteady Friction Slope Method= 2
Unsteady Bridges Friction Slope Method= 1
Parabolic Critical Depth
Global Vel Dist=  1 , 1 , 1
Global Log Level= 0
CheckData=True
Encroach Param= -1, 0, 0, 0
BEGIN DESCRIPTION:
Multiple Run
END DESCRIPTION:

--- Stream0190_DS.f01 (steady flow) ---

Flow Title=Multiple
Number of Profiles=7
Profile Names=10-year,25-year,50-year,1pct_min,100-year,1pct_plu,500-year
River Rch & RM= Stream0190_DS,Reach-1,9754
    1170    1976    2739    1839    3670    7322    6515
River Rch & RM= Stream0190_DS,Reach-1,6012
    1291    2195    3057    2060    4110    8200    7353
River Rch & RM= Stream0190_DS,Reach-1,2945
    1678    2901    4085    2781    5549   11072   10142
Boundary for River Rch & Prof#=Stream0190_DS,Reach-1,1
Up Type=0
Dn Type=3
Dn Slope=0.005
Boundary for River Rch & Prof#=Stream0190_DS,Reach-1,2
Up Type=0
Dn Type=3
Dn Slope=0.005
Boundary for River Rch & Prof#=Stream0190_DS,Reach-1,3
Up Type=0
Dn Type=3
Dn Slope=0.005
Boundary for River Rch & Prof#=Stream0190_DS,Reach-1,4
Up Type=0
Dn Type=3
Dn Slope=0.005
Boundary for River Rch & Prof#=Stream0190_DS,Reach-1,5
Up Type=0
Dn Type=3
Dn Slope=0.005
Boundary for River Rch & Prof#=Stream0190_DS,Reach-1,6
Up Type=0
Dn Type=3
Dn Slope=0.005
Boundary for River Rch & Prof#=Stream0190_DS,Reach-1,7
Up Type=0
Dn Type=3
Dn Slope=0.005

--- Stream0190_DS.g01 (geometry) ---

Geom Title=Existing Conditions

River Reach=Stream0190_DS,Reach-1
Reach XY= 30
      2123775.00     13886025.00      2123724.50     13885835.17
      2123774.49     13885490.21      2123676.36     13885315.35
      2123677.24     13885080.93      2124219.16     13884477.29
      2124274.49     13884359.79      2124280.46     13883972.55
      2124818.94     13883433.14      2125081.04     13883276.63
      2125223.37     13883321.87      2125349.28     13883201.69
      2125332.76     13883018.83      2125861.61     13882488.33
      2125973.96     13882264.56      2125924.19     13882029.57
      2125974.49     13881790.22      2125882.56     13881525.00
      2125924.34     13881290.84      2125731.57     13881125.00
      2126317.40     13880428.33      2126176.20     13880265.41
      2126217.44     13879825.00      2126173.62     13879584.66
      2126121.24     13879376.56      2125861.39     13878911.76
      2125773.54     13878828.54      2125611.68     13878811.63
      2125366.66     13878477.52      2125275.00     13878525.00

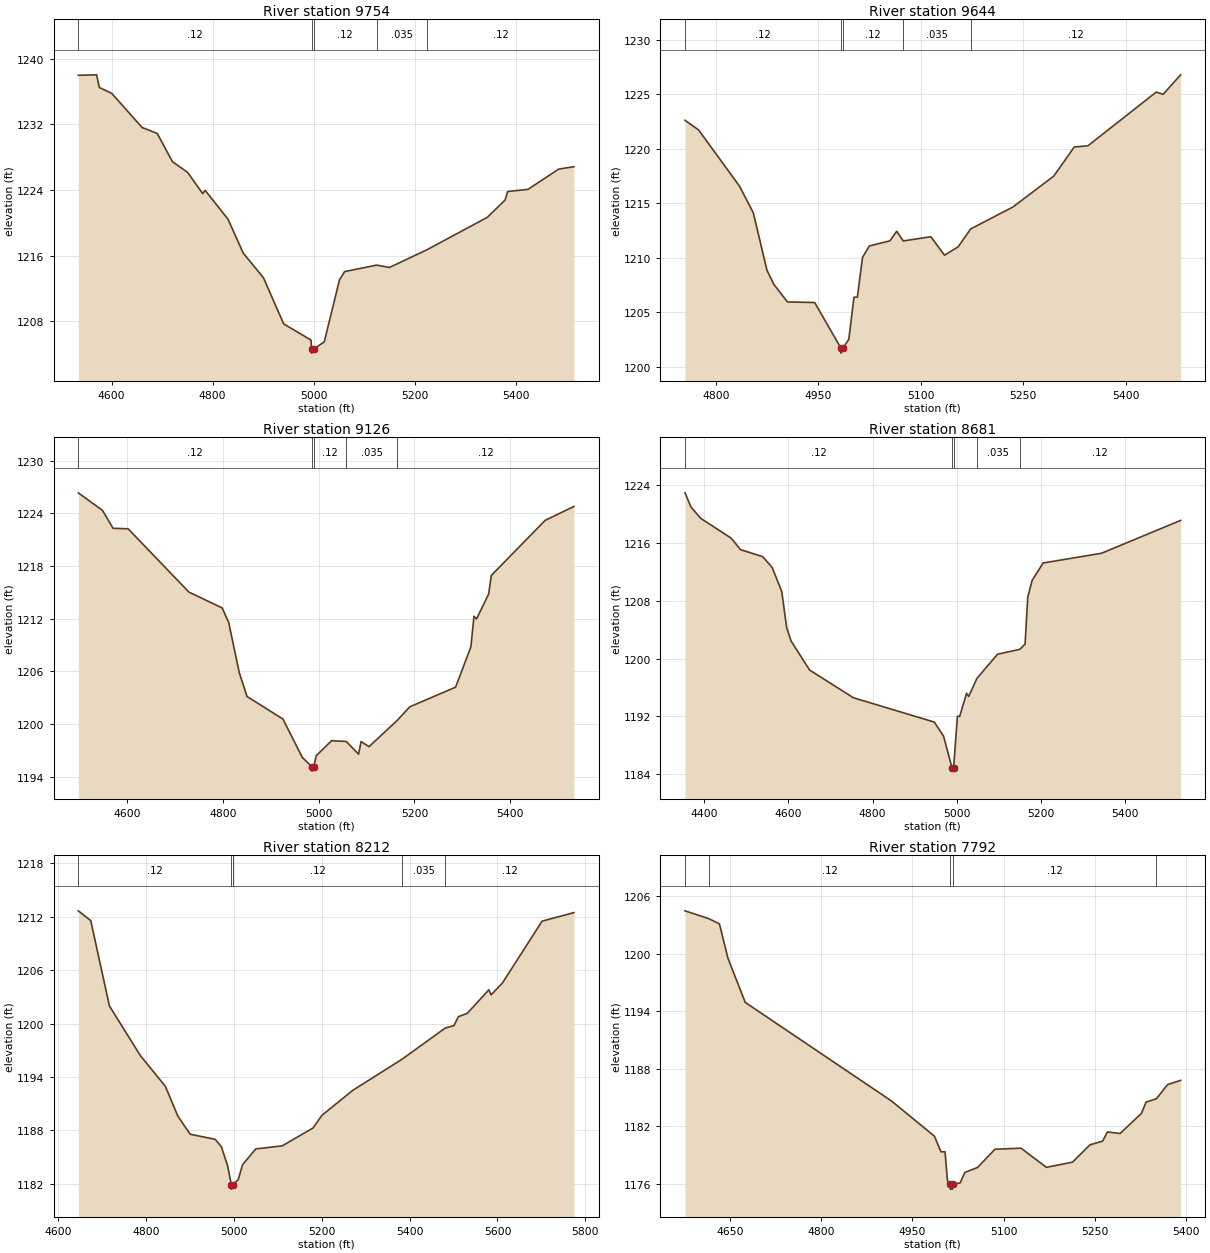
Type RM Length L Ch R = 1,9754,110,110,110
BEGIN DESCRIPTION:
Stream0190_DS 18.0
END DESCRIPTION:
XS GIS Cut Line= 3
      2124241.17     13885992.01      2123775.70     13885969.71
      2123264.86     13886038.11
#Sta/Elev= 30
  4534.0 1237.98  4570.2 1238.03  4575.6 1236.49  4600.2 1235.77  4660.3 1231.61
  4690.3 1230.88  4720.4 1227.44  4750.4 1226.14  4780.2 1223.55  4785.2 1223.94
  4830.5 1220.42  4860.5 1216.30  4900.6 1213.29  4940.6 1207.67  4994.8 1205.69
  4995.8 1204.60  4996.1 1204.10  4999.8 1204.60  5020.9 1205.46  5051.2 1213.04
  5061.2 1214.04  5124.8 1214.83  5149.9 1214.54  5224.6 1216.71  5343.7 1220.65
  5379.0 1222.76  5384.1 1223.80  5424.5 1224.07  5485.0 1226.53  5515.4 1226.83
#Mann=5,-1,0
  4534.0    0.12       0  4995.8    0.05       0  4999.8    0.12       0
  5124.8   0.035       0  5224.6    0.12       0
Bank Sta=4995.8,4999.8
Exp/Cntr=0.3,0.1

Type RM Length L Ch R = 1,9644,518,518,518
BEGIN DESCRIPTION:
Stream0190_DS 17.0
END DESCRIPTION:
XS GIS Cut Line= 3
      2123975.02     13885875.00      2123725.00     13885875.00
      2123249.34     13885892.25
#Sta/Elev= 30
  4754.5 1222.63  4774.5 1221.74  4834.5 1216.57  4854.5 1214.15  4874.5 1208.89
  4884.5 1207.59  4904.5 1205.97  4944.5 1205.91  4982.5 1201.77  4982.8 1201.27
  4986.5 1201.77  4994.5 1202.55  5002.0 1206.40  5007.0 1206.40  5014.5 1210.05
  5024.5 1211.10  5054.6 1211.57  5064.6 1212.45  5074.2 1211.56  5114.6 1211.95
  5134.6 1210.25  5154.6 1211.02  5172.9 1212.66  5234.7 1214.67  5294.7 1217.51
  5324.7 1220.18  5344.7 1220.29  5444.8 1225.22  5454.8 1225.01  5480.5 1226.80
#Mann=5,-1,0
  4754.5    0.12       0  4982.5    0.05       0  4986.5    0.12       0
  5074.2   0.035       0  5172.9    0.12       0
Bank Sta=4982.5,4986.5
Exp/Cntr=0.3,0.1

Type RM Length L Ch R = 1,9126,445,445,445
BEGIN DESCRIPTION:
Stream0190_DS 16.0
END DESCRIPTION:
XS GIS Cut Line= 3
      2124180.99     13885594.35      2123726.11     13885389.48
      2123222.69     13885570.01
#Sta/Elev= 30
  4498.9 1226.35  4549.3 1224.35  4571.3 1222.31  4602.8 1222.25  4729.5 1215.04
  4798.9 1213.23  4812.6 1211.57  4834.5 1205.87  4850.7 1203.14  4925.6 1200.57
  4966.1 1196.19  4986.0 1195.13  4986.3 1194.63  4990.0 1195.13  4995.0 1196.38
  5027.2 1198.10  5057.7 1198.01  5083.4 1196.56  5088.7 1198.00  5105.2 1197.42
  5163.6 1200.39  5190.2 1201.96  5285.8 1204.20  5317.7 1208.80  5324.1 1212.28
  5329.4 1211.97  5354.8 1214.83  5360.2 1216.93  5472.5 1223.21  5532.6 1224.80
#Mann=5,-1,0
  4498.9    0.12       0  4986.0    0.05       0  4990.0    0.12       0
  5057.7   0.035       0  5163.6    0.12       0
Bank Sta=4986,4990
Exp/Cntr=0.3,0.1

Type RM Length L Ch R = 1,8681,469,469,469
BEGIN DESCRIPTION:
Stream0190_DS 15.0
END DESCRIPTION:
XS GIS Cut Line= 3
      2124297.53     13885281.31      2123725.00     13884975.00
      2123211.37     13885092.88
#Sta/Elev= 30
  4355.0 1222.91  4369.2 1220.96  4391.9 1219.40  4464.7 1216.64  4486.6 1215.06
  4539.3 1214.09  4562.0 1212.58  4584.7 1209.25  4596.3 1204.27  4606.9 1202.42
  4650.8 1198.41  4754.8 1194.58  4946.6 1191.22  4968.6 1189.29  4988.5 1184.94
  4988.8 1184.44  4992.5 1184.94  5001.5 1192.01  5006.9 1192.01  5023.2 1195.19
  5028.3 1194.77  5047.7 1197.25  5096.7 1200.60  5149.5 1201.27  5162.1 1202.00
  5168.5 1208.50  5178.7 1210.78  5204.9 1213.21  5343.8 1214.56  5531.3 1219.10
#Mann=5,-1,0
  4355.0    0.12       0  4988.5    0.05       0  4992.5    0.12       0
  5047.7   0.035       0  5149.5    0.12       0
Bank Sta=4988.5,4992.5
Exp/Cntr=0.3,0.1

Type RM Length L Ch R = 1,8212,420,420,420
BEGIN DESCRIPTION:
Stream0190_DS 14.0
END DESCRIPTION:
XS GIS Cut Line= 3
      2124324.99     13884924.99      2124075.00     13884675.00
      2123302.62     13884628.66
#Sta/Elev= 30
  4646.7 1212.66  4675.0 1211.56  4717.4 1201.98  4788.1 1196.38  4844.7 1192.95
  4873.0 1189.61  4901.2 1187.56  4957.8 1187.00  4971.9 1186.18  4986.1 1184.06
  4994.7 1181.90  4994.9 1181.40  4998.7 1181.90  5010.3 1182.46  5020.3 1184.15
  5050.3 1185.92  5110.4 1186.26  5180.6 1188.27  5200.6 1189.68  5270.7 1192.49
  5383.0 1195.99  5481.5 1199.50  5501.1 1199.76  5511.1 1200.77  5531.2 1201.14
  5580.5 1203.79  5585.5 1203.22  5611.3 1204.55  5701.5 1211.50  5774.0 1212.46
#Mann=5,-1,0
  4646.7    0.12       0  4994.7    0.05       0  4998.7    0.12       0
  5383.0   0.035       0  5481.5    0.12       0
Bank Sta=4994.7,4998.7
Exp/Cntr=0.3,0.1

Type RM Length L Ch R = 1,7792,490,490,490
BEGIN DESCRIPTION:
Stream0190_DS 13.0
END DESCRIPTION:
XS GIS Cut Line= 3
      2124575.00     13884625.00      2124275.00     13884325.00
      2123974.98     13884074.98
#Sta/Elev= 30
  4576.3 1204.45  4615.2 1203.64  4632.9 1203.09  4647.0 1199.50  4675.3 1194.92
  4915.7 1184.66  4986.4 1180.99  4997.0 1179.37  5003.8 1179.37  5007.7 1176.39
  5012.2 1175.98  5012.5 1175.48  5016.0 1175.48  5016.2 1175.98  5028.5 1176.12
  5036.4 1177.22  5057.2 1177.73  5085.8 1179.63  5128.8 1179.74  5170.4 1177.75
  5213.4 1178.29  5242.0 1180.09  5262.9 1180.48  5270.7 1181.43  5291.5 1181.27
  5326.6 1183.36  5334.4 1184.54  5351.3 1184.89  5369.6 1186.36  5391.1 1186.80
#Mann=5,-1,0
  4576.3    0.07       0  4615.2    0.12       0  5012.2    0.05       0
  5016.2    0.12       0  5351.3   0.035       0
Bank Sta=5012.2,5016.2
Exp/Cntr=0.3,0.1

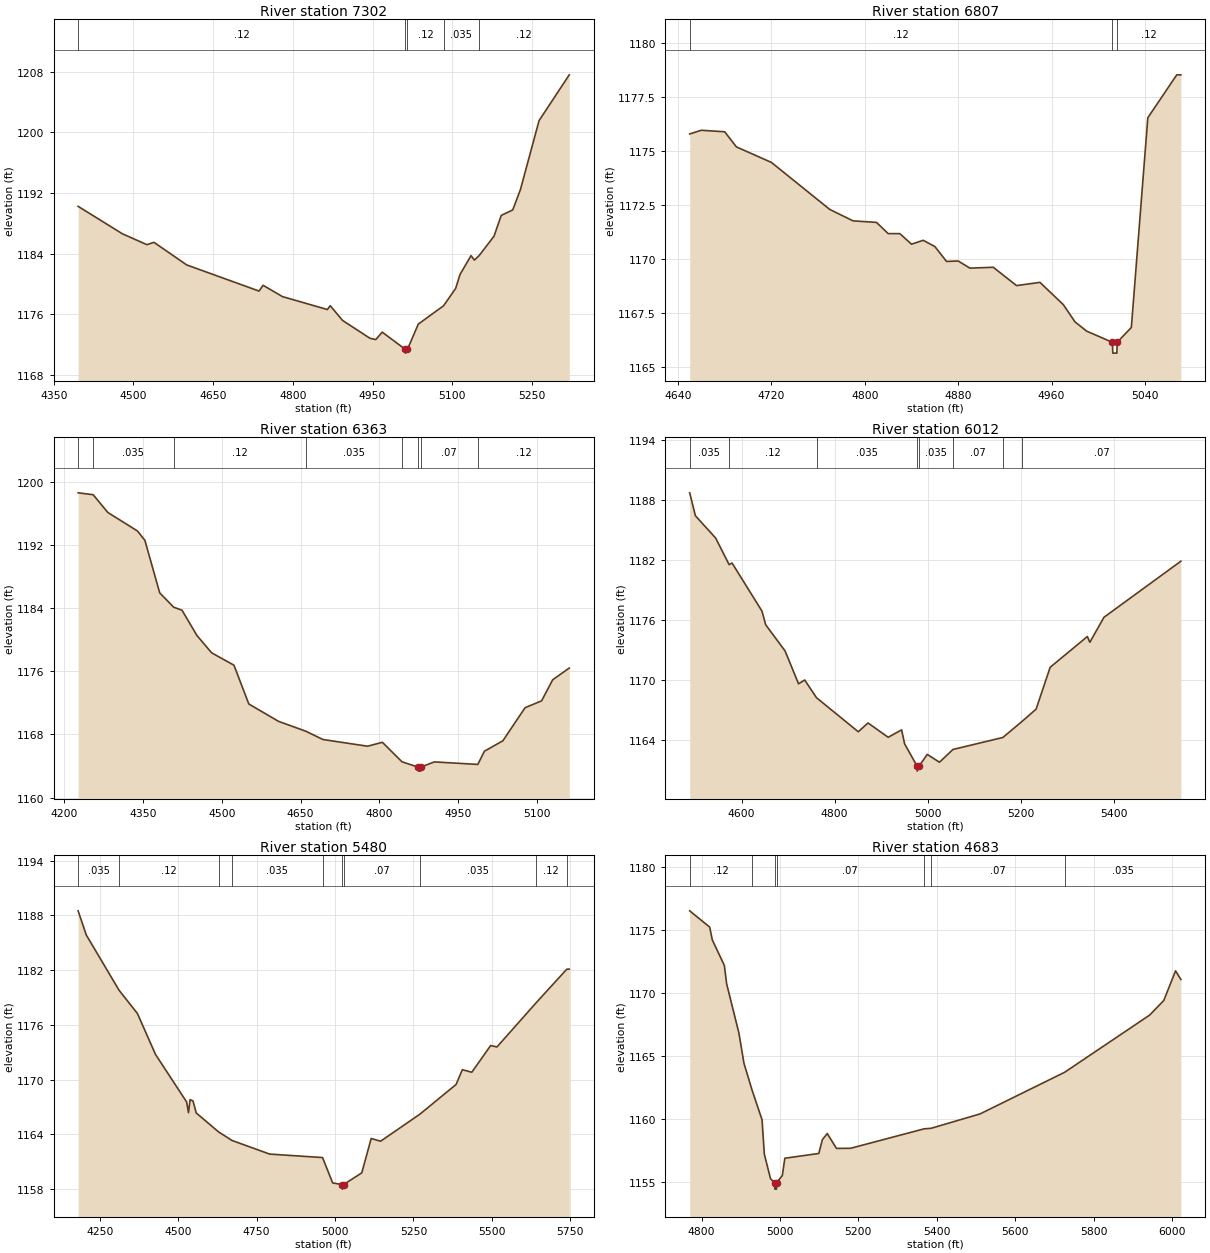
Type RM Length L Ch R = 1,7302,495,495,495
BEGIN DESCRIPTION:
Stream0190_DS 12.0
END DESCRIPTION:
XS GIS Cut Line= 3
      2124625.01     13884425.01      2124375.00     13883875.00
      2124125.02     13883675.01
#Sta/Elev= 30
  4395.8 1190.25  4479.3 1186.62  4525.4 1185.19  4538.6 1185.50  4600.1 1182.52
  4736.3 1179.07  4744.0 1179.83  4780.3 1178.34  4864.9 1176.63  4870.3 1177.14
  4893.4 1175.20  4945.0 1172.84  4956.0 1172.67  4968.1 1173.65  5011.6 1171.38
  5011.8 1170.88  5015.6 1171.38  5036.0 1174.71  5083.6 1177.13  5106.4 1179.43
  5114.4 1181.24  5135.2 1183.74  5141.6 1183.16  5150.3 1183.73  5178.5 1186.31
  5192.1 1189.05  5213.7 1189.77  5228.1 1192.44  5263.3 1201.56  5320.1 1207.60
#Mann=5,-1,0
  4395.8    0.12       0  5011.6    0.05       0  5015.6    0.12       0
  5083.6   0.035       0  5150.3    0.12       0
Bank Sta=5011.6,5015.6
Exp/Cntr=0.3,0.1

Type RM Length L Ch R = 1,6807,444,444,444
BEGIN DESCRIPTION:
Stream0190_DS 11.0
END DESCRIPTION:
XS GIS Cut Line= 3
      2124725.00     13883874.99      2124725.00     13883525.00
      2124675.00     13883475.00
#Sta/Elev= 30
  4650.0 1175.78  4660.0 1175.95  4680.0 1175.88  4690.0 1175.18  4720.0 1174.46
  4770.0 1172.28  4790.0 1171.75  4810.0 1171.68  4820.0 1171.16  4830.0 1171.16
  4840.0 1170.67  4850.0 1170.85  4860.0 1170.56  4870.0 1169.87  4880.0 1169.89
  4890.0 1169.56  4910.0 1169.60  4930.0 1168.75  4950.0 1168.90  4970.0 1167.87
  4980.0 1167.07  4990.0 1166.64  5012.1 1166.12  5012.4 1165.62  5015.9 1165.62
  5016.1 1166.12  5028.3 1166.81  5042.4 1176.53  5067.2 1178.52  5070.7 1178.52
#Mann=3,-1,0
  4650.0    0.12       0  5012.1    0.05       0  5016.1    0.12       0
Bank Sta=5012.1,5016.1
Exp/Cntr=0.3,0.1

Type RM Length L Ch R = 1,6363,351,351,351
BEGIN DESCRIPTION:
Stream0190_DS 10.0
END DESCRIPTION:
XS GIS Cut Line= 3
      2125624.99     13883824.99      2125075.00     13883275.00
      2124925.01     13883225.00
#Sta/Elev= 30
  4226.1 1198.66  4254.8 1198.42  4282.7 1196.17  4339.2 1193.82  4353.4 1192.63
  4381.6 1185.97  4408.2 1184.15  4424.1 1183.77  4452.4 1180.57  4480.6 1178.36
  4523.1 1176.79  4551.4 1171.87  4607.9 1169.67  4659.7 1168.42  4692.8 1167.36
  4777.6 1166.51  4805.9 1167.01  4843.3 1164.53  4874.6 1163.85  4874.9 1163.35
  4878.4 1163.35  4878.6 1163.85  4904.9 1164.52  4987.7 1164.20  5000.4 1165.88
  5035.5 1167.20  5077.7 1171.39  5109.3 1172.27  5130.4 1174.94  5162.0 1176.43
#Mann=8,-1,0
  4226.1    0.12       0  4254.8   0.035       0  4408.2    0.12       0
  4659.7   0.035       0  4843.3    0.07       0  4874.6    0.05       0
  4878.6    0.07       0  4987.7    0.12       0
Bank Sta=4874.6,4878.6
Exp/Cntr=0.3,0.1

Type RM Length L Ch R = 1,6012,532,532,532
BEGIN DESCRIPTION:
Stream0190_DS 9.0
END DESCRIPTION:
XS GIS Cut Line= 3
      2125674.01     13883594.31      2125358.05     13883191.56
      2124849.96     13882999.99
#Sta/Elev= 30
  4488.7 1188.73  4501.0 1186.44  4544.4 1184.22  4573.4 1181.56  4579.7 1181.72
  4643.9 1176.92  4652.0 1175.55  4693.6 1172.94  4722.5 1169.66  4735.7 1170.04
  4761.1 1168.27  4850.8 1164.87  4871.7 1165.75  4915.0 1164.32  4943.9 1165.06
  4950.3 1163.66  4977.1 1161.44  4977.3 1160.94  4981.3 1161.44  4999.0 1162.61
  5025.2 1161.83  5054.0 1163.10  5161.3 1164.30  5202.4 1165.90  5232.7 1167.13
  5262.9 1171.31  5342.8 1174.38  5348.2 1173.81  5378.4 1176.30  5543.6 1181.90
#Mann=8,-1,0
  4488.7   0.035       0  4573.4    0.12       0  4761.1   0.035       0
  4977.1   0.035       0  4981.3   0.035       0  5054.0    0.07       0
  5161.3    0.12       0  5202.4    0.07       0
Bank Sta=4977.1,4981.3
Exp/Cntr=0.3,0.1

Type RM Length L Ch R = 1,5480,797,797,797
BEGIN DESCRIPTION:
Stream0190_DS 8.0
END DESCRIPTION:
XS GIS Cut Line= 3
      2125725.01     13883575.03      2125575.00     13882775.00
      2124825.03     13882825.00
#Sta/Elev= 30
  4181.1 1188.51  4207.4 1185.85  4311.6 1179.81  4370.2 1177.26  4427.9 1172.77
  4527.1 1167.56  4533.0 1166.39  4538.1 1167.82  4547.4 1167.67  4557.6 1166.36
  4629.0 1164.28  4672.0 1163.34  4791.6 1161.85  4960.3 1161.47  4992.5 1158.69
  5023.0 1158.51  5023.3 1158.01  5027.3 1158.51  5085.3 1159.79  5115.3 1163.56
  5145.4 1163.26  5270.8 1166.23  5385.9 1169.48  5406.0 1171.10  5436.0 1170.82
  5496.2 1173.75  5516.2 1173.59  5639.7 1178.38  5738.7 1182.11  5746.7 1182.12
#Mann=10,-1,0
  4181.1   0.035       0  4311.6    0.12       0  4629.0    0.07       0
  4672.0   0.035       0  4960.3    0.07       0  5023.0    0.05       0
  5027.3    0.07       0  5270.8   0.035       0  5639.7    0.12       0
  5738.7    0.07       0
Bank Sta=5023,5027.3
Exp/Cntr=0.3,0.1

Type RM Length L Ch R = 1,4683,534,534,534
BEGIN DESCRIPTION:
Stream0190_DS 7.0
END DESCRIPTION:
XS GIS Cut Line= 3
      2126175.00     13882275.00      2125972.64     13882158.57
      2125125.03     13882724.98
#Sta/Elev= 30
  4769.8 1176.52  4820.8 1175.23  4827.5 1174.21  4858.2 1172.19  4864.0 1170.74
  4895.5 1166.80  4908.2 1164.43  4929.1 1162.28  4954.4 1159.94  4960.2 1157.21
  4976.0 1155.27  4986.7 1154.94  4987.0 1154.44  4991.1 1154.44  4991.4 1154.94
  5006.1 1155.52  5012.5 1156.89  5099.2 1157.27  5108.2 1158.36  5120.7 1158.85
  5144.3 1157.67  5180.3 1157.68  5367.4 1159.22  5386.1 1159.27  5510.7 1160.41
  5726.2 1163.71  5943.2 1168.25  5979.2 1169.41  6009.2 1171.76  6022.7 1171.08
#Mann=7,-1,0
  4769.8    0.12       0  4929.1    0.07       0  4986.7    0.05       0
  4991.4    0.07       0  5367.4   0.035       0  5386.1    0.07       0
  5726.2   0.035       0
Bank Sta=4986.7,4991.4
Exp/Cntr=0.3,0.1

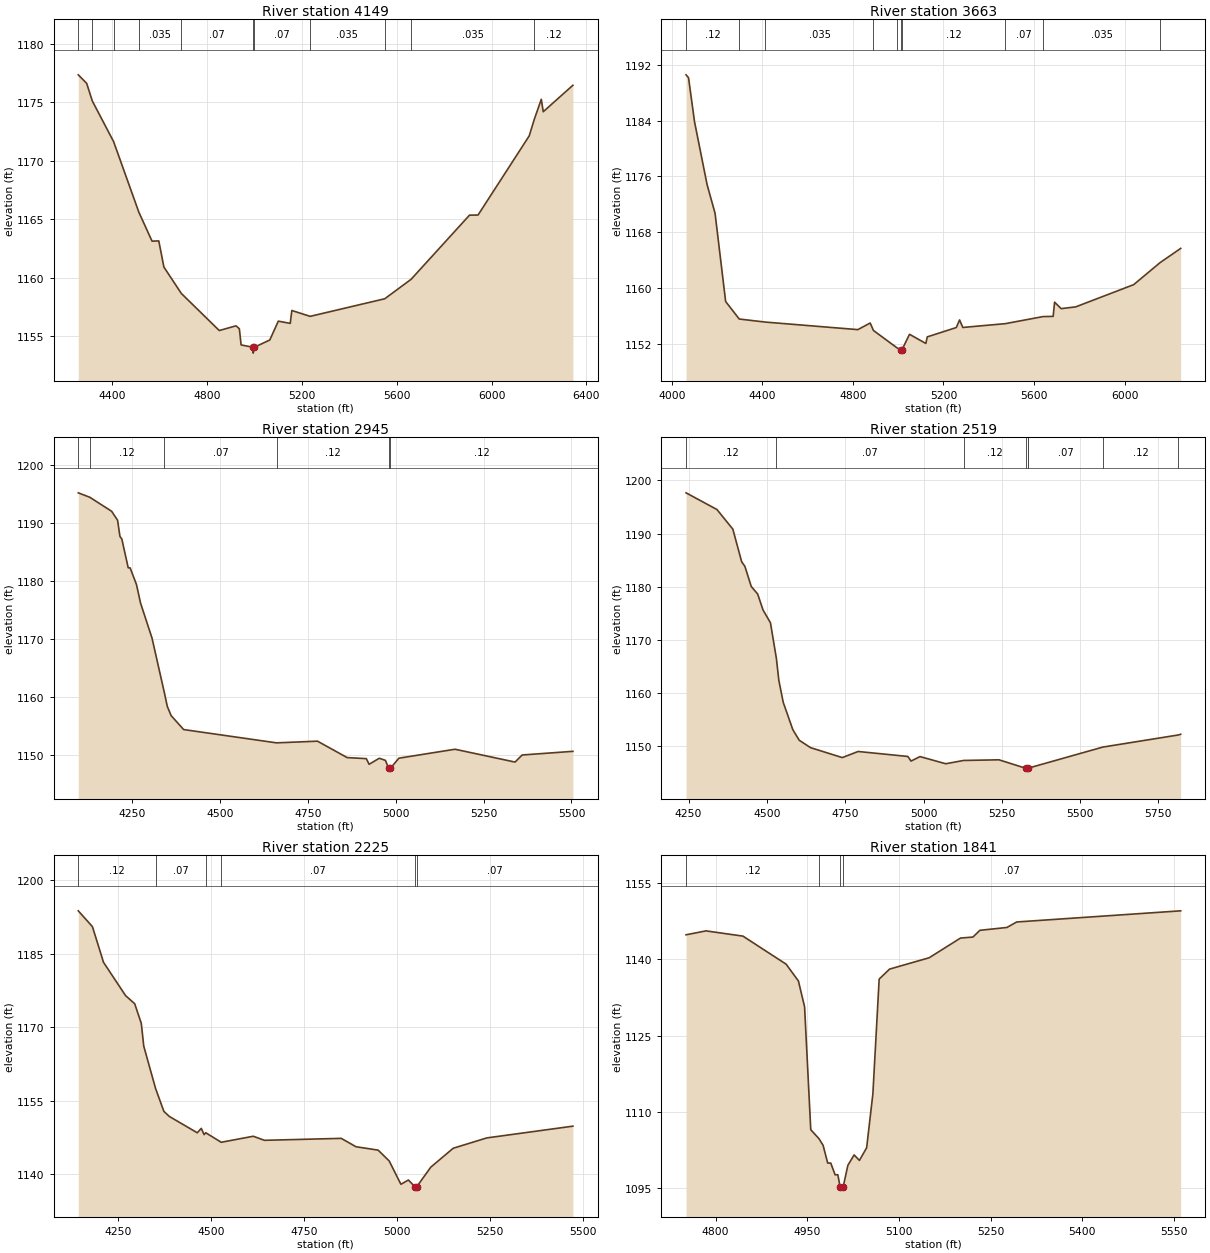
Type RM Length L Ch R = 1,4149,486,486,486
BEGIN DESCRIPTION:
Stream0190_DS 6.0
END DESCRIPTION:
XS GIS Cut Line= 3
      2126475.01     13882175.01      2125925.00     13881675.00
      2124811.29     13882425.68
#Sta/Elev= 30
  4256.3 1177.33  4291.8 1176.60  4315.7 1175.09  4405.3 1171.63  4511.9 1165.60
  4567.5 1163.13  4595.9 1163.15  4617.5 1160.92  4690.8 1158.67  4851.0 1155.50
  4921.6 1155.90  4935.8 1155.65  4943.2 1154.27  4993.8 1154.07  4994.2 1153.57
  4998.6 1154.07  5064.1 1154.69  5100.1 1156.30  5150.4 1156.11  5157.1 1157.21
  5234.3 1156.71  5549.0 1158.21  5660.1 1159.87  5906.6 1165.35  5942.6 1165.36
  6158.5 1172.12  6179.5 1173.51  6209.4 1175.24  6217.6 1174.18  6342.7 1176.44
#Mann=11,-1,0
  4256.3    0.07       0  4315.7    0.12       0  4405.3    0.07       0
  4511.9   0.035       0  4690.8    0.07       0  4993.8    0.05       0
  4998.6    0.07       0  5234.3   0.035       0  5549.0    0.07       0
  5660.1   0.035       0  6179.5    0.12       0
Bank Sta=4993.8,4998.6
Exp/Cntr=0.3,0.1

Type RM Length L Ch R = 1,3663,718,718,718
BEGIN DESCRIPTION:
Stream0190_DS 5.0
END DESCRIPTION:
XS GIS Cut Line= 3
      2126792.18     13881148.83      2125862.05     13881261.26
      2124885.72     13882037.81
#Sta/Elev= 30
  4063.1 1190.58  4074.1 1190.16  4100.5 1183.86  4155.9 1174.85  4191.2 1170.73
  4238.0 1158.07  4298.1 1155.56  4413.9 1155.12  4821.8 1154.04  4876.2 1154.99
  4890.7 1153.92  4995.5 1151.41  5012.3 1151.17  5012.7 1150.67  5017.1 1151.17
  5049.9 1153.37  5122.1 1152.06  5128.4 1153.00  5256.6 1154.34  5271.0 1155.43
  5285.4 1154.35  5473.8 1154.90  5639.5 1155.91  5684.3 1155.94  5690.7 1157.98
  5719.5 1157.05  5783.6 1157.30  6039.9 1160.49  6155.8 1163.63  6247.5 1165.69
#Mann=10,-1,0
  4063.1    0.12       0  4298.1    0.07       0  4413.9   0.035       0
  4890.7    0.07       0  4995.5    0.12       0  5012.3    0.05       0
  5017.1    0.12       0  5473.8    0.07       0  5639.5   0.035       0
  6155.8    0.07       0
Bank Sta=5012.3,5017.1
Exp/Cntr=0.3,0.1

Type RM Length L Ch R = 1,2945,426,426,426
BEGIN DESCRIPTION:
Stream0190_DS 4.0
END DESCRIPTION:
XS GIS Cut Line= 3
      2126887.70     13881097.21      2126061.45     13880742.63
      2125563.42     13880645.15
#Sta/Elev= 30
  4097.4 1195.13  4130.4 1194.36  4192.3 1191.95  4209.2 1190.41  4215.9 1187.63
  4221.3 1187.17  4239.4 1182.22  4244.9 1182.20  4263.0 1179.32  4274.5 1176.14
  4307.1 1170.11  4342.1 1160.74  4350.6 1158.33  4361.5 1156.75  4397.1 1154.35
  4661.2 1152.06  4777.7 1152.35  4862.1 1149.52  4916.5 1149.34  4924.5 1148.37
  4953.5 1149.41  4970.9 1149.04  4980.0 1147.69  4980.4 1147.19  4985.1 1147.69
  5009.2 1149.42  5168.8 1150.96  5339.4 1148.75  5359.7 1149.97  5504.0 1150.60
#Mann=6,-1,0
  4097.4    0.07       0  4130.4    0.12       0  4342.1    0.07       0
  4661.2    0.12       0  4980.0    0.05       0  4985.1    0.12       0
Bank Sta=4980,4985.1
Exp/Cntr=0.3,0.1

Type RM Length L Ch R = 1,2519,294,294,294
BEGIN DESCRIPTION:
Stream0190_DS 3.0
END DESCRIPTION:
XS GIS Cut Line= 3
      2127059.08     13880569.21      2126316.04     13880418.33
      2125495.00     13880428.15
#Sta/Elev= 30
  4241.8 1197.67  4340.6 1194.52  4391.2 1190.83  4419.4 1184.68  4429.6 1183.84
  4450.0 1180.03  4470.4 1178.62  4487.4 1175.64  4511.3 1173.19  4530.2 1166.50
  4538.1 1162.34  4552.1 1158.21  4582.7 1153.07  4603.1 1151.08  4639.3 1149.68
  4740.6 1147.81  4791.2 1148.96  4950.0 1148.02  4960.2 1147.15  4988.7 1148.00
  5071.0 1146.65  5128.1 1147.27  5241.1 1147.39  5328.5 1145.76  5328.9 1145.26
  5333.6 1145.76  5334.9 1145.83  5572.6 1149.79  5813.8 1152.07  5821.1 1152.20
#Mann=8,-1,0
  4241.8    0.12       0  4530.2    0.07       0  5128.1    0.12       0
  5328.5    0.05       0  5333.6    0.12       0  5334.9    0.07       0
  5572.6    0.12       0  5813.8   0.035       0
Bank Sta=5328.5,5333.6
Exp/Cntr=0.3,0.1

Type RM Length L Ch R = 1,2225,384,384,384
BEGIN DESCRIPTION:
Stream0190_DS 2.0
END DESCRIPTION:
XS GIS Cut Line= 3
      2126972.63     13880495.13      2126174.90     13880180.04
      2125704.32     13880138.66
#Sta/Elev= 30
  4142.3 1193.80  4180.4 1190.57  4210.2 1183.29  4269.7 1176.48  4294.0 1174.85
  4311.8 1170.83  4318.4 1166.19  4350.2 1157.54  4372.5 1152.88  4387.0 1151.85
  4462.3 1148.51  4473.1 1149.41  4480.7 1148.13  4485.2 1148.51  4526.7 1146.57
  4612.8 1147.80  4643.0 1146.97  4849.4 1147.37  4889.1 1145.66  4948.6 1144.97
  4978.4 1142.76  5009.9 1138.00  5030.0 1138.87  5047.5 1137.51  5047.9 1137.01
  5052.6 1137.51  5090.2 1141.49  5150.5 1145.35  5240.8 1147.46  5472.4 1149.86
#Mann=6,-1,0
  4142.3    0.12       0  4350.2    0.07       0  4485.2    0.12       0
  4526.7    0.07       0  5047.5    0.05       0  5052.6    0.07       0
Bank Sta=5047.5,5052.6
Exp/Cntr=0.3,0.1

Type RM Length L Ch R = 1,1841,621,621,621
BEGIN DESCRIPTION:
Stream0190_DS 1.0
END DESCRIPTION:
XS GIS Cut Line= 3
      2126457.36     13879780.42      2126211.05     13879811.79
      2125662.90     13879930.22
#Sta/Elev= 30
  4751.7 1144.81  4784.3 1145.58  4844.8 1144.55  4915.4 1139.04  4935.5 1135.74
  4945.6 1130.66  4955.7 1106.52  4969.0 1104.78  4975.9 1103.45  4983.4 1099.97
  4988.4 1099.97  4995.5 1097.67  5000.0 1097.67  5003.6 1095.35  5004.0 1094.85
  5008.8 1095.35  5016.4 1099.52  5026.6 1101.57  5035.3 1100.49  5047.1 1102.97
  5057.3 1113.56  5067.6 1136.11  5084.6 1138.07  5149.4 1140.30  5200.6 1144.17
  5221.0 1144.37  5232.3 1145.69  5276.5 1146.25  5292.6 1147.33  5560.8 1149.52
#Mann=4,-1,0
  4751.7    0.12       0  4969.0    0.07       0  5003.6    0.05       0
  5008.8    0.07       0
Bank Sta=5003.6,5008.8
Exp/Cntr=0.3,0.1

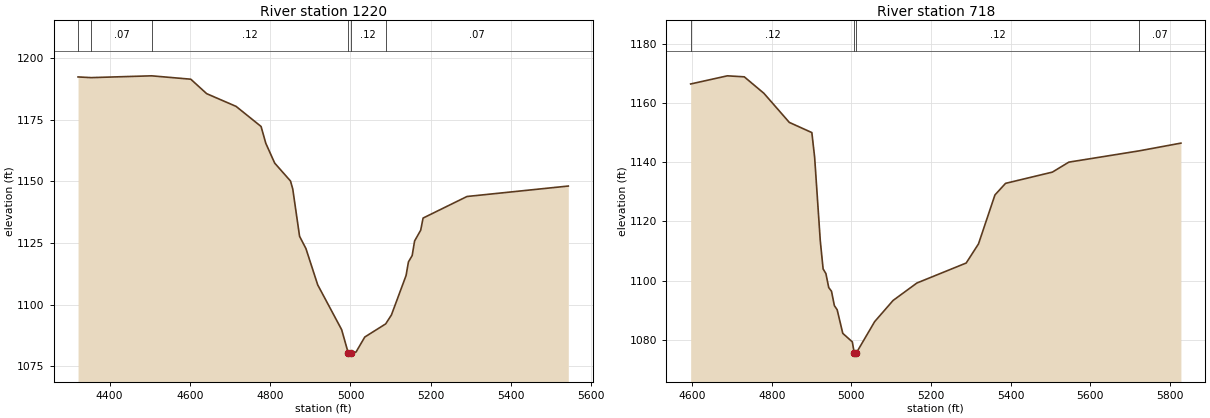
Type RM Length L Ch R = 1,1220,502,502,502
BEGIN DESCRIPTION:
Stream0190_DS 0.1
END DESCRIPTION:
XS GIS Cut Line= 3
      2126655.92     13878949.14      2126045.18     13879244.93
      2125755.56     13879703.76
#Sta/Elev= 30
  4321.4 1192.37  4353.8 1192.09  4504.6 1192.82  4602.2 1191.45  4641.8 1185.58
  4715.1 1180.42  4777.3 1172.27  4789.1 1165.44  4811.3 1157.39  4850.6 1150.14
  4856.2 1146.95  4873.2 1127.72  4889.1 1122.71  4918.4 1108.00  4978.0 1089.83
  4994.4 1080.40  4994.9 1079.90  5000.2 1080.40  5013.8 1080.74  5035.6 1086.83
  5087.7 1092.17  5102.0 1095.79  5138.5 1111.80  5144.4 1117.31  5153.7 1119.90
  5159.7 1125.80  5174.9 1130.17  5180.9 1135.11  5290.3 1143.86  5542.6 1148.10
#Mann=6,-1,0
  4321.4    0.12       0  4353.8    0.07       0  4504.6    0.12       0
  4994.4    0.05       0  5000.2    0.12       0  5087.7    0.07       0
Bank Sta=4994.4,5000.2
Exp/Cntr=0.3,0.1

Type RM Length L Ch R = 1,718,0,0,0
BEGIN DESCRIPTION:
Stream0190_DS 0.0
END DESCRIPTION:
XS GIS Cut Line= 3
      2126068.25     13878547.86      2125784.82     13878835.47
      2125582.50     13879637.96
#Sta/Elev= 30
  4596.2 1166.39  4688.4 1169.14  4730.9 1168.80  4780.3 1163.22  4844.0 1153.41
  4900.6 1149.97  4907.6 1141.66  4921.8 1113.43  4928.9 1103.93  4935.9 1102.35
  4943.0 1097.63  4950.0 1096.38  4957.2 1091.53  4964.2 1090.14  4978.3 1082.17
  5002.3 1079.28  5006.9 1075.65  5007.4 1075.15  5012.7 1075.65  5058.4 1086.13
  5104.7 1093.28  5164.5 1099.17  5288.3 1105.92  5319.2 1112.38  5360.5 1128.91
  5387.1 1132.82  5504.8 1136.62  5546.1 1139.99  5722.3 1143.79  5827.6 1146.41
#Mann=4,-1,0
  4596.2    0.12       0  5006.9    0.05       0  5012.7    0.12       0
  5722.3    0.07       0
Bank Sta=5006.9,5012.7
Exp/Cntr=0.3,0.1

Chan Stop Cuts=-1