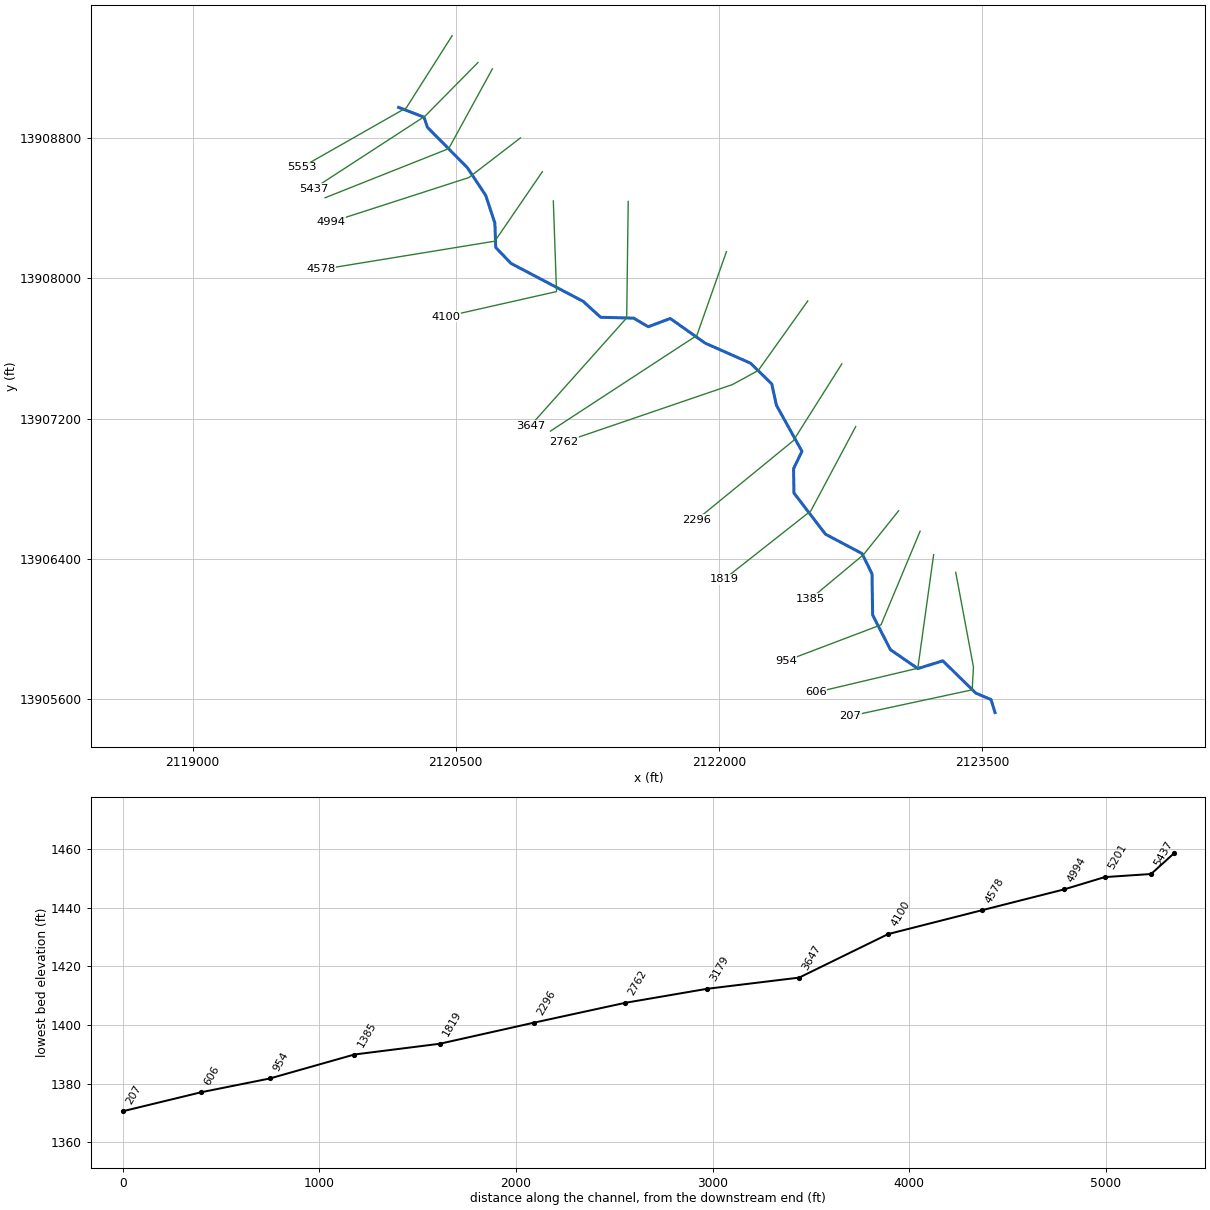
--- Stream0191_DS.prj (project) ---

Proj Title=Stream0191_DS Base Level Engineering
Current Plan=p01
Default Exp/Contr=0.3,0.1
English Units
Geom File=g01
Flow File=f01
Plan File=p01
Y Axis Title=Elevation
X Axis Title(PF)=Main Channel Distance
X Axis Title(XS)=Station
BEGIN DESCRIPTION:
Stream0191_DS
END DESCRIPTION:
DSS Export Rating Curves= 0
DSS Export Rating Curve Sorted= 0
DSS Export Volume Flow Curves= 0
DXF OffsetX= 0
DXF OffsetY= 0
DXF ScaleX= 1
DXF ScaleY= 10

--- Stream0191_DS.p01 (plan) ---

Plan Title=Multiple Run
Short Identifier=Multiple
Geom File=g01
Flow File=f01
Subcritical Flow
K Sum by GR= 0
Std Step Tol= 0.01
Critical Tol= 0.01
Num of Std Step Trials= 20
Max Error Tol= 0.3
Flow Tol Ratio= 0.001
Split Flow NTrial= 30
Split Flow Tol= 0.02
Split Flow Ratio= 0.02
Log Output Level= 0
Friction Slope Method= 1
Unsteady Friction Slope Method= 2
Unsteady Bridges Friction Slope Method= 1
Parabolic Critical Depth
Global Vel Dist=  1 , 1 , 1
Global Log Level= 0
CheckData=True
Encroach Param= -1, 0, 0, 0
BEGIN DESCRIPTION:
Multiple Run
END DESCRIPTION:

--- Stream0191_DS.f01 (steady flow) ---

Flow Title=Multiple
Number of Profiles=7
Profile Names=10-year,25-year,50-year,1pct_min,100-year,1pct_plu,500-year
River Rch & RM= Stream0191_DS,Reach-1,5553
     797    1340    1857    1251    2496    4981    4453
River Rch & RM= Stream0191_DS,Reach-1,5201
    1221    2099    2946    2007    4005    7991    7315
Boundary for River Rch & Prof#=Stream0191_DS,Reach-1,1
Up Type=0
Dn Type=3
Dn Slope=0.005
Boundary for River Rch & Prof#=Stream0191_DS,Reach-1,2
Up Type=0
Dn Type=3
Dn Slope=0.005
Boundary for River Rch & Prof#=Stream0191_DS,Reach-1,3
Up Type=0
Dn Type=3
Dn Slope=0.005
Boundary for River Rch & Prof#=Stream0191_DS,Reach-1,4
Up Type=0
Dn Type=3
Dn Slope=0.005
Boundary for River Rch & Prof#=Stream0191_DS,Reach-1,5
Up Type=0
Dn Type=3
Dn Slope=0.005
Boundary for River Rch & Prof#=Stream0191_DS,Reach-1,6
Up Type=0
Dn Type=3
Dn Slope=0.005
Boundary for River Rch & Prof#=Stream0191_DS,Reach-1,7
Up Type=0
Dn Type=3
Dn Slope=0.005

--- Stream0191_DS.g01 (geometry) ---

Geom Title=Existing Conditions
Program Version=4.10

River Reach=Stream0191_DS   ,Reach-1
Reach XY= 30
        2120175.       13908975.      2120319.41     13908919.43
      2120338.72     13908862.02      2120566.84     13908631.05
      2120671.38      13908473.5      2120723.61     13908315.33
      2120728.54     13908176.46      2120815.29     13908085.75
      2121227.29     13907869.15      2121326.47     13907778.55
       2121514.5     13907773.76      2121597.81     13907724.63
      2121723.28     13907771.66      2121922.71     13907630.85
      2122181.06     13907516.86      2122302.12     13907398.52
      2122328.83     13907276.59      2122474.25     13907014.32
      2122426.39     13906915.34      2122428.54     13906776.47
      2122608.48     13906541.69      2122816.99     13906431.38
      2122873.64     13906315.35      2122877.24     13906080.93
      2122978.51     13905883.48      2123134.78     13905775.76
       2123277.3     13905819.91      2123465.33     13905635.77
      2123552.18     13905598.98        2123575.       13905525.

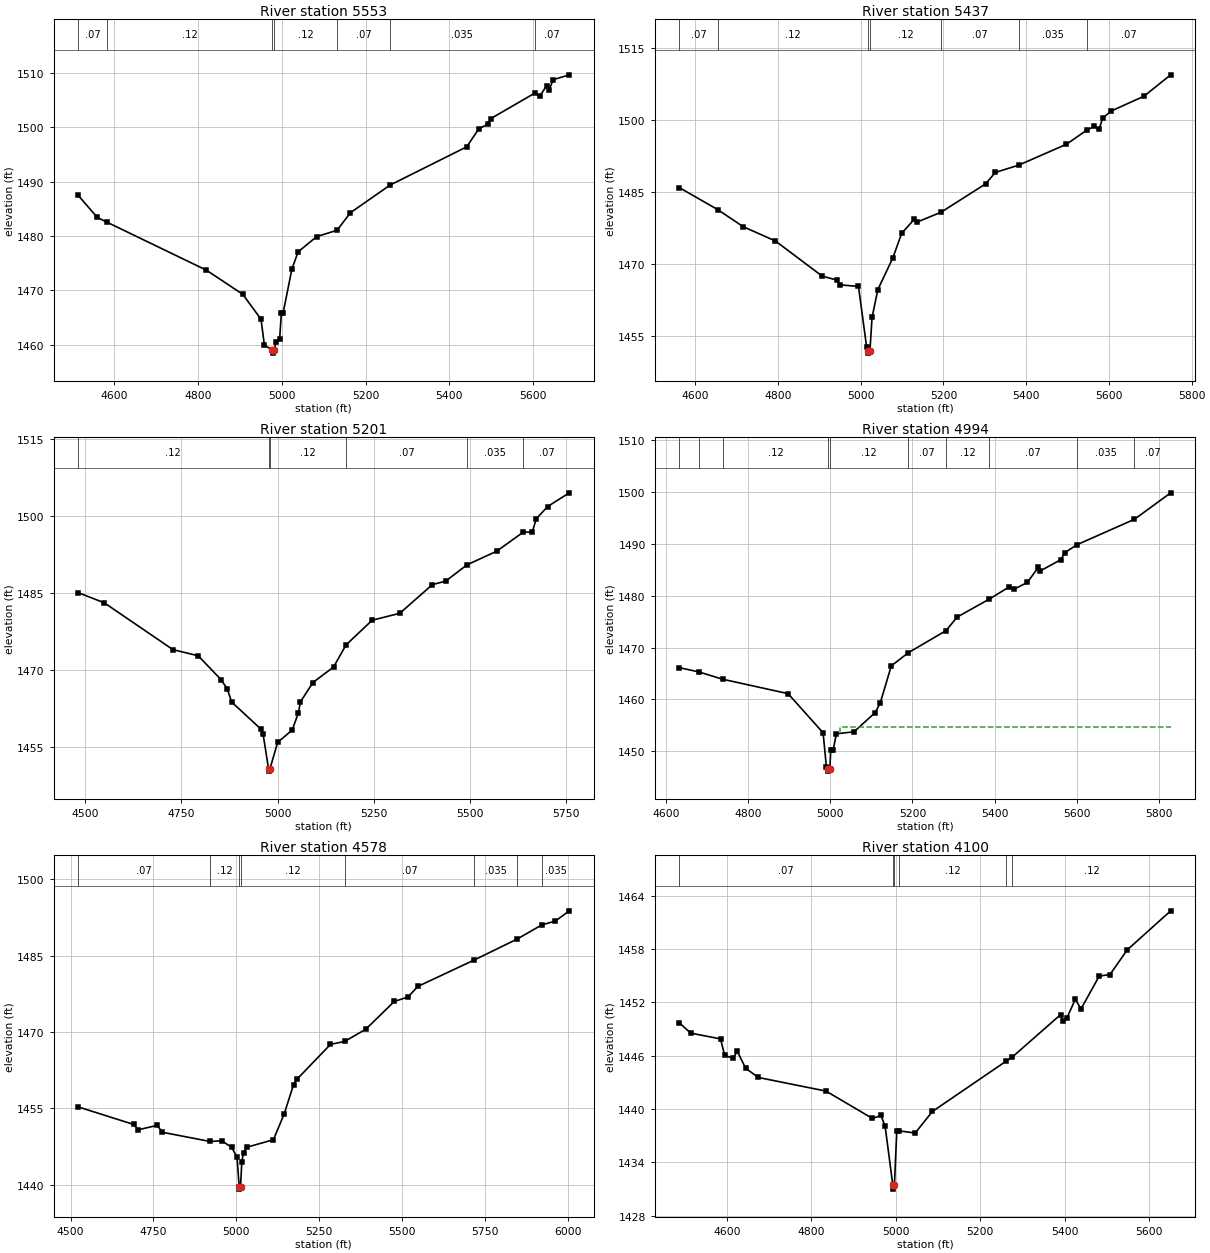
Type RM Length L Ch R = 1 ,5553    ,116,116,116
BEGIN DESCRIPTION:
Stream0191_DS 13.0
END DESCRIPTION:
XS GIS Cut Line= 3
      2120479.64     13909383.71      2120218.78     13908973.06
      2119622.05     13908633.65
#Sta/Elev= 30
  4513.5 1487.51  4559.4 1483.43  4581.9 1482.58    4820 1473.73  4906.7  1469.3
  4950.3 1464.71  4958.3    1460  4977.5 1458.98  4977.8 1458.48  4981.5 1458.98
  4985.9 1460.47  4994.8 1461.08  4998.9 1465.87  5003.1 1465.87    5024 1473.93
  5038.9  1477.1  5083.1  1479.9    5132 1481.08  5163.8  1484.3  5258.6 1489.39
  5441.5 1496.42  5470.8 1499.77  5492.5 1500.58    5499 1501.61  5603.5 1506.27
  5616.4 1505.79  5632.3 1507.65    5638 1506.88  5648.1 1508.77  5686.5 1509.66
#Mann= 7 ,-1 , 0
  4513.5     .07       0  4581.9     .12       0  4977.5     .05       0
  4981.5     .12       0    5132     .07       0  5258.6    .035       0
  5603.5     .07       0
Bank Sta=4977.5,4981.5
XS Rating Curve= 0 ,0
Exp/Cntr=0.3,0.1

Type RM Length L Ch R = 1 ,5437    ,236,236,236
BEGIN DESCRIPTION:
Stream0191_DS 12.0
END DESCRIPTION:
XS GIS Cut Line= 3
      2120627.02     13909230.73        2120325.       13908925.
      2119689.74     13908512.12
#Sta/Elev= 30
  4561.9 1485.89  4654.6 1481.32  4715.9 1477.78  4793.7 1474.81  4906.8 1467.49
  4942.2 1466.67  4949.3 1465.68  4994.6 1465.34  5014.4 1452.64  5018.3 1451.96
  5018.6 1451.46  5022.3 1451.96  5027.4 1458.89  5041.4 1464.68  5077.7 1471.29
    5099  1476.4    5129 1479.28    5135 1478.69  5194.4  1480.8  5301.7 1486.68
  5325.4 1489.07  5381.6 1490.58  5497.4 1494.94  5546.3 1497.87  5563.9 1498.65
  5576.1 1498.01    5585 1500.41  5606.1 1501.88  5684.6 1504.93  5749.3 1509.39
#Mann= 7 ,-1 , 0
  4561.9     .07       0  4654.6     .12       0  5018.3     .05       0
  5022.3     .12       0  5194.4     .07       0  5381.6    .035       0
  5546.3     .07       0
Bank Sta=5018.3,5022.3
XS Rating Curve= 0 ,0
Exp/Cntr=0.3,0.1

Type RM Length L Ch R = 1 ,5201    ,207,207,207
BEGIN DESCRIPTION:
Stream0191_DS 11.5
END DESCRIPTION:
XS GIS Cut Line= 3
       2120709.3     13909194.82      2120460.16     13908739.87
       2119755.5       13908460.
#Sta/Elev= 30
  4481.3 1485.14  4549.5 1483.15  4727.9 1474.04  4793.4 1472.85  4853.1 1468.19
  4868.7 1466.44  4880.6 1463.84  4956.5 1458.58  4962.2 1457.58  4976.3  1450.9
  4976.5  1450.4  4980.3  1450.9  4999.9 1455.99  5037.8 1458.39  5053.9 1461.72
  5059.3 1463.88  5091.6 1467.64  5145.4 1470.66  5177.8 1474.96  5245.6 1479.76
  5317.6 1481.12  5402.1 1486.69  5437.2 1487.39  5492.1 1490.54  5569.5  1493.2
  5638.8 1496.93  5661.9 1496.89  5672.1 1499.48  5701.8 1501.89  5758.2 1504.56
#Mann= 6 ,-1 , 0
  4481.3     .12       0  4976.3     .05       0  4980.3     .12       0
  5177.8     .07       0  5492.1    .035       0  5638.8     .07       0
Bank Sta=4976.3,4980.3
XS Rating Curve= 0 ,0
Exp/Cntr=0.3,0.1

Type RM Length L Ch R = 1 ,4994    ,416,416,416
BEGIN DESCRIPTION:
Stream0191_DS 11.0
END DESCRIPTION:
XS GIS Cut Line= 3
      2120869.24     13908801.07        2120575.       13908575.
      2119791.11     13908321.89
#Sta/Elev= 30
  4633.5 1466.12  4681.9 1465.27  4738.6 1463.89  4897.6 1461.12  4982.8 1453.58
    4991  1446.9  4995.3  1446.7  4995.5  1446.2  4999.3  1446.7  5001.4 1450.22
  5007.2 1450.22  5015.1 1453.39  5057.9 1453.77  5109.6 1457.48  5121.9 1459.34
  5148.7 1466.47  5190.2    1469  5281.7 1473.24  5308.9 1475.86  5387.3 1479.33
  5435.4 1481.67  5447.5 1481.23  5479.6 1482.52  5506.3 1485.43  5511.6 1484.77
  5561.5 1486.93  5570.4 1488.25  5600.5 1489.79  5740.2 1494.69  5828.3 1499.78
#Mann= 10 ,-1 , 0
  4633.5     .12       0  4681.9     .07       0  4738.6     .12       0
  4995.3     .05       0  4999.3     .12       0  5190.2     .07       0
  5281.7     .12       0  5387.3     .07       0  5600.5    .035       0
  5740.2     .07       0
#XS Ineff= 2 , 0
       0                 5024.62       0 1454.63
Permanent Ineff=
       F       F
Bank Sta=4995.3,4999.3
XS Rating Curve= 0 ,0
Exp/Cntr=0.3,0.1

Type RM Length L Ch R = 1 ,4578    ,478,478,478
BEGIN DESCRIPTION:
Stream0191_DS 10.0
END DESCRIPTION:
XS GIS Cut Line= 3
      2120994.19     13908608.31      2120723.37      13908212.5
      2119733.75     13908051.04
#Sta/Elev= 30
  4522.5 1455.28  4689.7 1451.84  4704.6 1450.79  4761.5 1451.66  4776.4  1450.3
  4920.7 1448.49  4955.8 1448.62  4985.6 1447.36  5002.1 1445.41  5008.6 1439.63
  5008.8 1439.13  5012.6 1439.63  5016.6 1444.52  5021.7 1446.32  5030.8 1447.34
  5111.9 1448.83  5144.6 1453.93  5172.7 1459.65  5182.8  1460.7  5284.1 1467.55
  5326.8 1468.13  5390.4 1470.52  5476.7 1475.98  5518.3 1476.87  5547.6 1478.93
  5717.8 1484.12  5846.6 1488.21  5921.7 1491.01    5963 1491.78  6004.8 1493.78
#Mann= 8 ,-1 , 0
  4522.5     .07       0  4920.7     .12       0  5008.6     .05       0
  5012.6     .12       0  5326.8     .07       0  5717.8    .035       0
  5846.6     .07       0  5921.7    .035       0
Bank Sta=5008.6,5012.6
XS Rating Curve= 0 ,0
Exp/Cntr=0.3,0.1

Type RM Length L Ch R = 1 ,4100    ,453,453,453
BEGIN DESCRIPTION:
Stream0191_DS 9.0
END DESCRIPTION:
XS GIS Cut Line= 3
      2121056.71     13908441.71        2121075.       13907925.
      2120444.77     13907782.82
#Sta/Elev= 30
  4487.8 1449.68  4514.5 1448.54  4585.2 1447.89  4594.6 1446.04  4614.6 1445.71
  4624.6  1446.5  4644.6 1444.58  4674.6 1443.55  4834.7 1442.02  4944.8 1438.94
  4964.8 1439.28  4974.8 1438.04  4992.8 1431.49  4993.1 1430.99  4996.8 1431.49
  5002.3 1437.55  5007.4 1437.55  5045.8  1437.3  5086.8 1439.73  5261.7  1445.4
  5276.1 1445.86  5390.2 1450.62  5395.3 1449.86  5404.6 1450.19  5425.1 1452.35
  5438.5 1451.26  5481.7 1454.96  5507.1 1455.13  5548.1 1457.91  5650.9  1462.3
#Mann= 6 ,-1 , 0
  4487.8     .07       0  4992.8     .05       0  4996.8     .07       0
  5007.4     .12       0  5261.7     .07       0  5276.1     .12       0
Bank Sta=4992.8,4996.8
XS Rating Curve= 0 ,0
Exp/Cntr=0.3,0.1

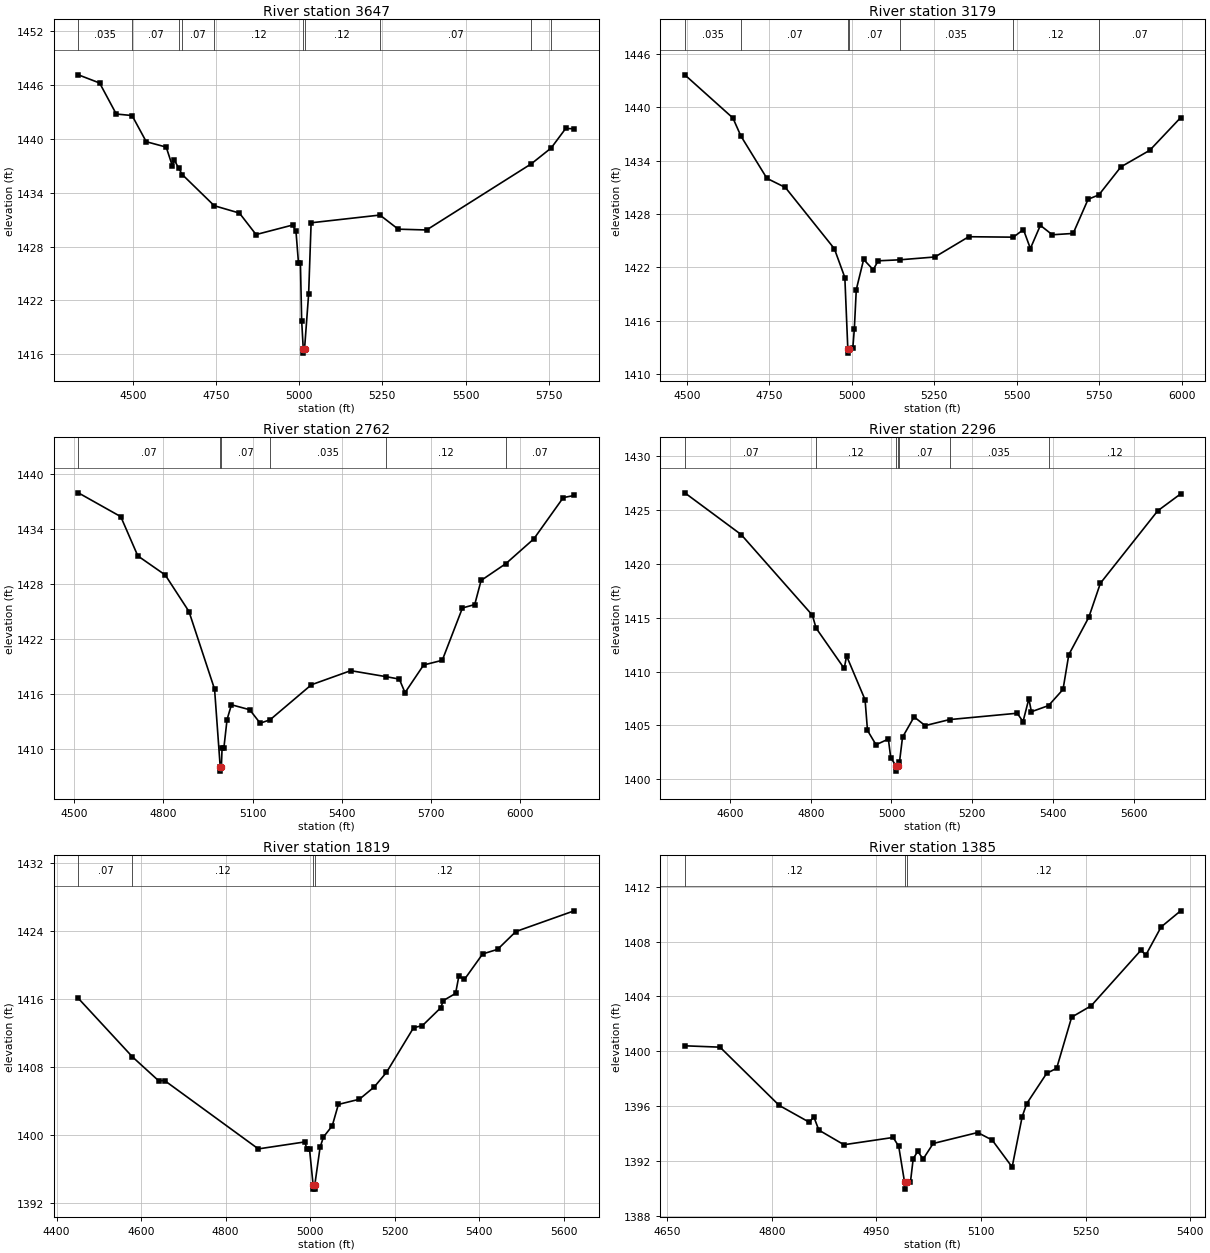
Type RM Length L Ch R = 1 ,3647    ,468,468,468
BEGIN DESCRIPTION:
Stream0191_DS 8.0
END DESCRIPTION:
XS GIS Cut Line= 3
      2121483.79     13908439.04        2121475.       13907775.
      2120924.84     13907158.88
#Sta/Elev= 30
  4336.3  1447.1  4400.3 1446.19  4450.3 1442.74  4497.8 1442.57  4540.4 1439.66
  4600.4 1439.06    4619 1436.95    4624 1437.68  4637.9 1436.71  4648.5 1436.01
  4744.7 1432.54  4820.4 1431.72  4870.4 1429.33  4980.4 1430.39  4990.4 1429.68
  4997.9 1426.18  5003.7 1426.18  5007.5 1419.74  5012.2 1416.64  5012.5 1416.14
  5016.2 1416.64  5028.4  1422.7  5035.9 1430.64  5242.7  1431.5  5297.6 1429.93
  5382.9 1429.84  5697.6  1437.2  5757.3 1438.96  5800.9 1441.13  5826.4  1441.1
#Mann= 10 ,-1 , 0
  4336.3    .035       0  4497.8     .07       0  4637.9    .035       0
  4648.5     .07       0  4744.7     .12       0  5012.2     .05       0
  5016.2     .12       0  5242.7     .07       0  5697.6    .035       0
  5757.3     .07       0
Bank Sta=5012.2,5016.2
XS Rating Curve= 0 ,0
Exp/Cntr=0.3,0.1

Type RM Length L Ch R = 1 ,3179    ,417,417,417
BEGIN DESCRIPTION:
Stream0191_DS 7.0
END DESCRIPTION:
XS GIS Cut Line= 3
      2122043.68     13908152.59        2121875.       13907675.
      2121040.31     13907129.74
#Sta/Elev= 30
  4493.5 1443.65  4639.4 1438.79  4663.5 1436.77  4742.5    1432  4798.5 1430.97
    4947 1424.08  4978.8 1420.84  4987.8 1412.83  4988.1 1412.33  4991.8 1412.83
    5003 1412.91  5007.6 1415.06  5013.5 1419.48  5035.8 1422.87  5064.8 1421.72
    5080 1422.72  5144.6 1422.83  5251.8 1423.15  5354.5 1425.43  5489.6 1425.38
  5520.4 1426.23  5541.4  1424.1  5571.7 1426.71  5607.9 1425.65  5671.1  1425.8
  5716.5 1429.65  5748.9 1430.13  5815.9 1433.29  5903.5 1435.16    5997 1438.83
#Mann= 7 ,-1 , 0
  4493.5    .035       0  4663.5     .07       0  4987.8     .05       0
  4991.8     .07       0  5144.6    .035       0  5489.6     .12       0
  5748.9     .07       0
Bank Sta=4987.8,4991.8
XS Rating Curve= 0 ,0
Exp/Cntr=0.3,0.1

Type RM Length L Ch R = 1 ,2762    ,466,466,466
BEGIN DESCRIPTION:
Stream0191_DS 6.0
END DESCRIPTION:
XS GIS Cut Line= 4
      2122507.21     13907871.33        2122225.       13907475.
      2122077.54     13907394.79      2121118.47     13907067.12
#Sta/Elev= 30
  4513.7  1437.9  4656.5  1435.3  4713.8 1431.02    4806 1428.94  4885.9 1424.95
    4972 1416.48  4990.9 1408.04  4991.1 1407.54  4994.9 1408.04  4997.2 1410.01
  5003.1 1410.01    5014 1413.17  5028.7 1414.78    5090 1414.24  5125.5 1412.77
  5158.6 1413.14  5297.6 1416.96    5430  1418.5  5548.1 1417.85  5593.5 1417.58
  5612.6  1416.1  5675.3 1419.12  5737.9 1419.63  5805.8 1425.34  5847.1 1425.71
  5868.5 1428.34    5952 1430.18  6045.8 1432.87    6145 1437.38  6181.6 1437.61
#Mann= 6 ,-1 , 0
  4513.7     .07       0  4990.9     .05       0  4994.9     .07       0
  5158.6    .035       0  5548.1     .12       0    5952     .07       0
Bank Sta=4990.9,4994.9
XS Rating Curve= 0 ,0
Exp/Cntr=0.3,0.1

Type RM Length L Ch R = 1 ,2296    ,477,477,477
BEGIN DESCRIPTION:
Stream0191_DS 5.0
END DESCRIPTION:
XS GIS Cut Line= 3
      2122701.53     13907512.96        2122425.       13907075.
      2121874.99     13906624.99
#Sta/Elev= 30
  4487.9 1426.61  4627.6 1422.73    4804 1415.24  4813.2 1414.04  4882.9 1410.29
  4888.8 1411.45  4934.6 1407.38  4940.6 1404.53  4961.7  1403.2  4992.3 1403.73
  4998.2    1402    5011 1401.25  5011.3 1400.75    5015 1401.25  5019.8 1401.57
  5027.4  1403.9  5056.1 1405.79  5083.4 1404.98    5144 1405.54  5311.6 1406.13
    5326 1405.35  5340.4 1407.47  5346.8 1406.27  5389.2 1406.84  5425.1 1408.34
  5439.4 1411.57  5488.9 1415.04  5517.7 1418.21  5659.8 1424.94  5716.5 1426.51
#Mann= 7 ,-1 , 0
  4487.9     .07       0  4813.2     .12       0    5011     .05       0
    5015     .12       0  5019.8     .07       0    5144    .035       0
  5389.2     .12       0
Bank Sta=5011,5015
XS Rating Curve= 0 ,0
Exp/Cntr=0.3,0.1

Type RM Length L Ch R = 1 ,1819    ,434,434,434
BEGIN DESCRIPTION:
Stream0191_DS 4.0
END DESCRIPTION:
XS GIS Cut Line= 3
      2122780.66     13907155.21        2122525.       13906675.
      2122030.68     13906285.43
#Sta/Elev= 30
  4451.4 1416.07  4579.5 1409.17  4641.4 1406.36  4655.6 1406.38  4877.4 1398.33
  4987.3 1399.15  4992.6 1398.28  4998.6 1398.28    5007 1394.09  5007.3 1393.59
  5010.8 1393.59    5011 1394.09  5023.5 1398.51  5031.5 1399.73  5052.3 1401.05
  5066.8 1403.57  5116.5 1404.18  5151.7 1405.63  5180.6 1407.34  5244.8 1412.61
  5265.6 1412.85  5308.9 1414.95  5315.3 1415.81  5344.2 1416.65  5351.9 1418.68
    5365 1418.29  5408.3  1421.3  5443.6 1421.84  5486.9 1423.94  5624.8 1426.38
#Mann= 4 ,-1 , 0
  4451.4     .07       0  4579.5     .12       0    5007     .05       0
    5011     .12       0
Bank Sta=5007,5011
XS Rating Curve= 0 ,0
Exp/Cntr=0.3,0.1

Type RM Length L Ch R = 1 ,1385    ,431,431,431
BEGIN DESCRIPTION:
Stream0191_DS 3.0
END DESCRIPTION:
XS GIS Cut Line= 3
      2123025.02     13906675.03        2122825.       13906425.
      2122525.01       13906175.
#Sta/Elev= 30
  4675.4 1400.39  4725.9 1400.29  4810.7 1396.04  4853.9 1394.81  4860.3 1395.21
  4867.5 1394.24  4903.5 1393.17    4974  1393.7    4982 1393.06  4990.4 1390.43
  4990.6 1389.93  4994.4 1390.43  4998.8 1390.43  5002.8 1392.16  5009.3 1392.68
  5017.1 1392.13  5031.4 1393.26  5095.2 1394.06    5116 1393.51  5144.6 1391.54
    5159 1395.22  5165.5 1396.17  5194.1 1398.38  5208.4 1398.75  5229.9 1402.48
  5257.9 1403.31  5329.5 1407.38    5336 1406.99  5358.1 1409.06  5386.1 1410.24
#Mann= 3 ,-1 , 0
  4675.4     .12       0  4990.4     .05       0  4994.4     .12       0
Bank Sta=4990.4,4994.4
XS Rating Curve= 0 ,0
Exp/Cntr=0.3,0.1

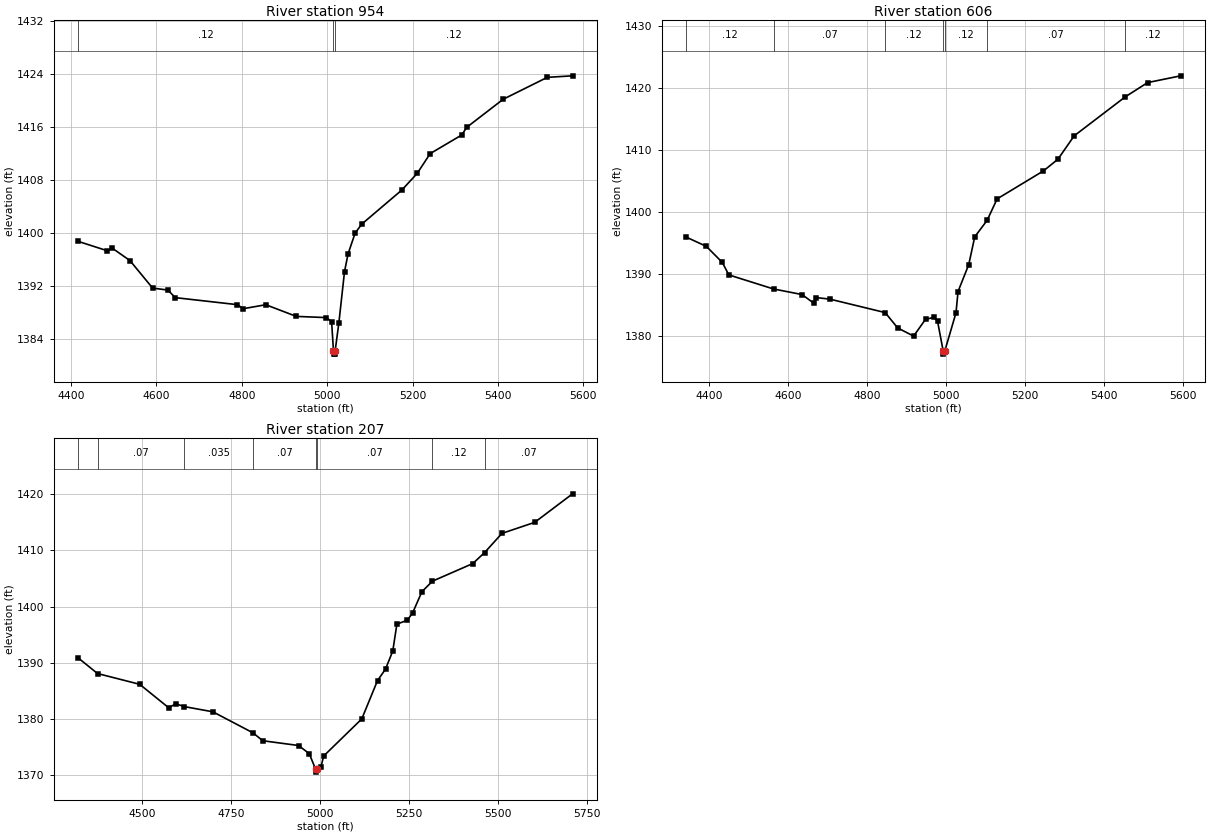
Type RM Length L Ch R = 1 ,954     ,348,348,348
BEGIN DESCRIPTION:
Stream0191_DS 2.0
END DESCRIPTION:
XS GIS Cut Line= 3
      2123147.87      13906558.9        2122925.       13906025.
      2122383.16     13905819.63
#Sta/Elev= 30
  4416.9 1398.75    4485 1397.34    4497 1397.71    4538 1395.86  4591.1 1391.71
    4627 1391.41  4644.1 1390.27  4789.6 1389.21  4803.3  1388.6  4856.3  1389.2
  4927.8 1387.44  4998.1 1387.26  5010.5 1386.63  5014.8 1382.25  5015.1 1381.75
  5018.6 1381.75  5018.8 1382.25  5027.5 1386.47  5040.7 1394.18  5048.9 1396.84
  5065.5 1399.99    5081 1401.35  5175.4 1406.52  5210.9    1409  5241.4 1411.99
  5315.4  1414.8    5327 1415.95  5412.5 1420.19  5515.8 1423.49  5574.9 1423.72
#Mann= 3 ,-1 , 0
  4416.9     .12       0  5014.8     .05       0  5018.8     .12       0
Bank Sta=5014.8,5018.8
XS Rating Curve= 0 ,0
Exp/Cntr=0.3,0.1

Type RM Length L Ch R = 1 ,606     ,399,399,399
BEGIN DESCRIPTION:
Stream0191_DS 1.0
END DESCRIPTION:
XS GIS Cut Line= 3
        2123225.     13906425.03      2123134.83     13905777.61
      2122552.38     13905639.79
#Sta/Elev= 30
  4342.3 1395.93  4392.8 1394.45  4433.2 1391.86  4449.7 1389.85  4562.9 1387.58
  4635.1 1386.68  4664.5 1385.31  4669.5  1386.2  4705.8 1385.94  4845.8 1383.77
  4877.4  1381.3  4917.8 1379.98  4948.1 1382.69  4968.3 1382.98  4978.4  1382.4
  4992.8 1377.57    4993 1377.07  4996.8 1377.57  5025.2 1383.73  5030.4 1387.17
  5057.5 1391.51  5072.7 1395.99  5104.1 1398.65  5129.4 1402.11  5246.9 1406.63
  5283.5 1408.51  5324.6 1412.28  5454.3 1418.58  5510.7 1420.87  5594.5 1421.96
#Mann= 7 ,-1 , 0
  4342.3     .12       0  4562.9     .07       0  4845.8     .12       0
  4992.8     .05       0  4996.8     .12       0  5104.1     .07       0
  5454.3     .12       0
Bank Sta=4992.8,4996.8
XS Rating Curve= 0 ,0
Exp/Cntr=0.3,0.1

Type RM Length L Ch R = 1 ,207     ,0,0,0
BEGIN DESCRIPTION:
Stream0191_DS 0.0
END DESCRIPTION:
XS GIS Cut Line= 4
      2123350.92     13906324.63      2123452.06     13905784.14
      2123444.84     13905654.62      2122751.09     13905505.47
#Sta/Elev= 30
  4320.4 1390.88  4374.6 1388.11    4493  1386.2  4574.4 1382.04  4594.7 1382.73
  4618.9 1382.23  4698.8 1381.31  4811.9 1377.56  4838.9 1376.17  4939.5 1375.32
  4969.6 1373.88  4987.6 1371.09  4987.8 1370.59  4991.6 1371.09  5002.5 1371.51
  5010.1 1373.45  5117.3 1380.05  5161.5 1386.86    5184  1388.9  5204.4 1392.12
    5216  1396.9  5245.3 1397.58  5260.3  1398.9  5286.2 1402.65    5316 1404.53
  5429.4 1407.66  5462.6 1409.62  5511.3 1413.02  5603.3 1414.98  5709.6 1420.05
#Mann= 8 ,-1 , 0
  4320.4     .12       0  4374.6     .07       0  4618.9    .035       0
  4811.9     .07       0  4987.6     .05       0  4991.6     .07       0
    5316     .12       0  5462.6     .07       0
Bank Sta=4987.6,4991.6
XS Rating Curve= 0 ,0
Exp/Cntr=0.3,0.1

Chan Stop Cuts=-1
Use User Specified Reach Order=0
Composite Channel Slope=5