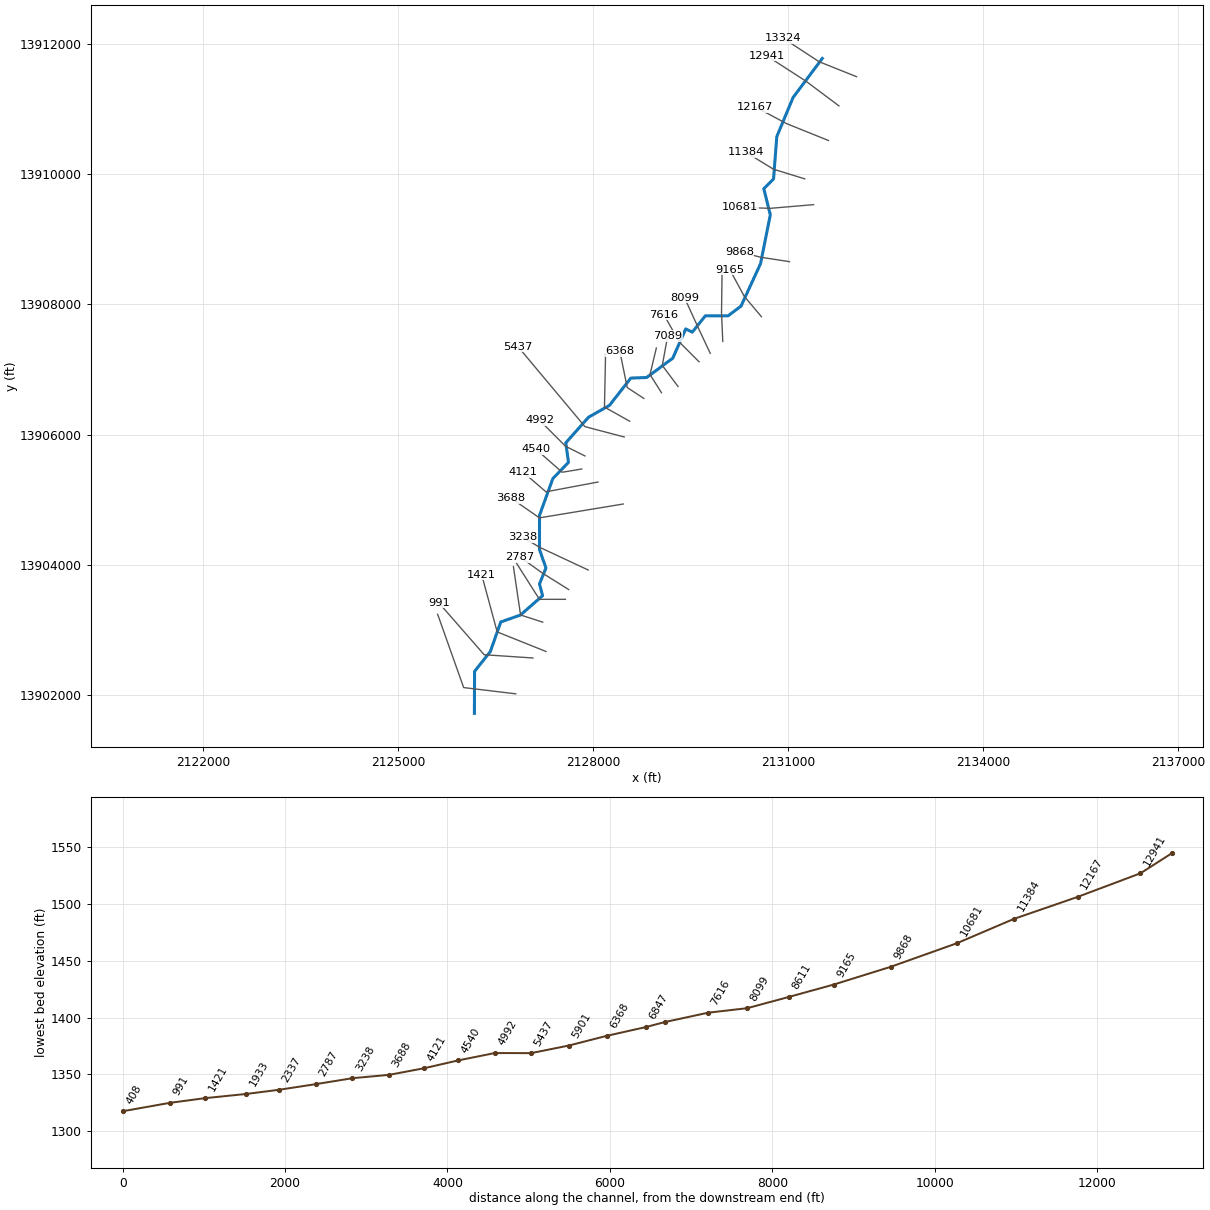
--- Stream0192_DS.prj (project) ---

Proj Title=Stream0192_DS Base Level Engineering
Current Plan=p01
Default Exp/Contr=0.3,0.1
English Units
Geom File=g01
Flow File=f01
Plan File=p01
Y Axis Title=Elevation
X Axis Title(PF)=Main Channel Distance
X Axis Title(XS)=Station
BEGIN DESCRIPTION:
Stream0192_DS
END DESCRIPTION:
DSS Export Rating Curves= 0
DSS Export Rating Curve Sorted= 0
DSS Export Volume Flow Curves= 0
DXF OffsetX= 0
DXF OffsetY= 0
DXF ScaleX= 1
DXF ScaleY= 10

--- Stream0192_DS.p01 (plan) ---

Plan Title=Multiple Run
Short Identifier=Multiple
Geom File=g01
Flow File=f01
Subcritical Flow
K Sum by GR= 0
Std Step Tol= 0.01
Critical Tol= 0.01
Num of Std Step Trials= 20
Max Error Tol= 0.3
Flow Tol Ratio= 0.001
Split Flow NTrial= 30
Split Flow Tol= 0.02
Split Flow Ratio= 0.02
Log Output Level= 0
Friction Slope Method= 1
Unsteady Friction Slope Method= 2
Unsteady Bridges Friction Slope Method= 1
Parabolic Critical Depth
Global Vel Dist=  1 , 1 , 1
Global Log Level= 0
CheckData=True
Encroach Param= -1, 0, 0, 0
BEGIN DESCRIPTION:
Multiple Run
END DESCRIPTION:

--- Stream0192_DS.f01 (steady flow) ---

Flow Title=Multiple
Number of Profiles=7
Profile Names=10-year,25-year,50-year,1pct_min,100-year,1pct_plu,500-year
River Rch & RM= Stream0192_DS,Reach-1,13324
     339     530     698     448     895    1785    1446
River Rch & RM= Stream0192_DS,Reach-1,9868
    1397    2397    3361    2282    4554    9086    8270
River Rch & RM= Stream0192_DS,Reach-1,4992
    1738    3006    4236    2888    5763   11499   10554
Boundary for River Rch & Prof#=Stream0192_DS,Reach-1,1
Up Type=0
Dn Type=3
Dn Slope=0.005
Boundary for River Rch & Prof#=Stream0192_DS,Reach-1,2
Up Type=0
Dn Type=3
Dn Slope=0.005
Boundary for River Rch & Prof#=Stream0192_DS,Reach-1,3
Up Type=0
Dn Type=3
Dn Slope=0.005
Boundary for River Rch & Prof#=Stream0192_DS,Reach-1,4
Up Type=0
Dn Type=3
Dn Slope=0.005
Boundary for River Rch & Prof#=Stream0192_DS,Reach-1,5
Up Type=0
Dn Type=3
Dn Slope=0.005
Boundary for River Rch & Prof#=Stream0192_DS,Reach-1,6
Up Type=0
Dn Type=3
Dn Slope=0.005
Boundary for River Rch & Prof#=Stream0192_DS,Reach-1,7
Up Type=0
Dn Type=3
Dn Slope=0.005

--- Stream0192_DS.g01 (geometry) ---

Geom Title=Existing Conditions
Program Version=4.10

River Reach=Stream0192_DS   ,Reach-1
Reach XY= 30
        2131525.       13911775.        2131075.       13911175.
        2130825.       13910575.        2130775.       13909925.
        2130625.       13909775.        2130725.       13909375.
        2130575.       13908625.        2130275.       13907975.
        2130075.       13907825.        2129725.       13907825.
        2129525.       13907575.        2129425.       13907625.
        2129225.       13907175.      2128823.45     13906878.75
      2128580.08     13906869.97      2128251.82      13906451.3
      2127930.44     13906269.75      2127580.45     13905877.45
      2127621.33     13905576.58      2127380.52     13905327.44
      2127176.22      13904764.5      2127175.52     13904240.22
      2127275.28     13903954.82      2127175.55     13903711.03
      2127223.46     13903530.85      2126881.34     13903233.02
       2126580.4     13903127.71      2126419.23     13902672.47
      2126177.24     13902369.07        2126175.       13901725.

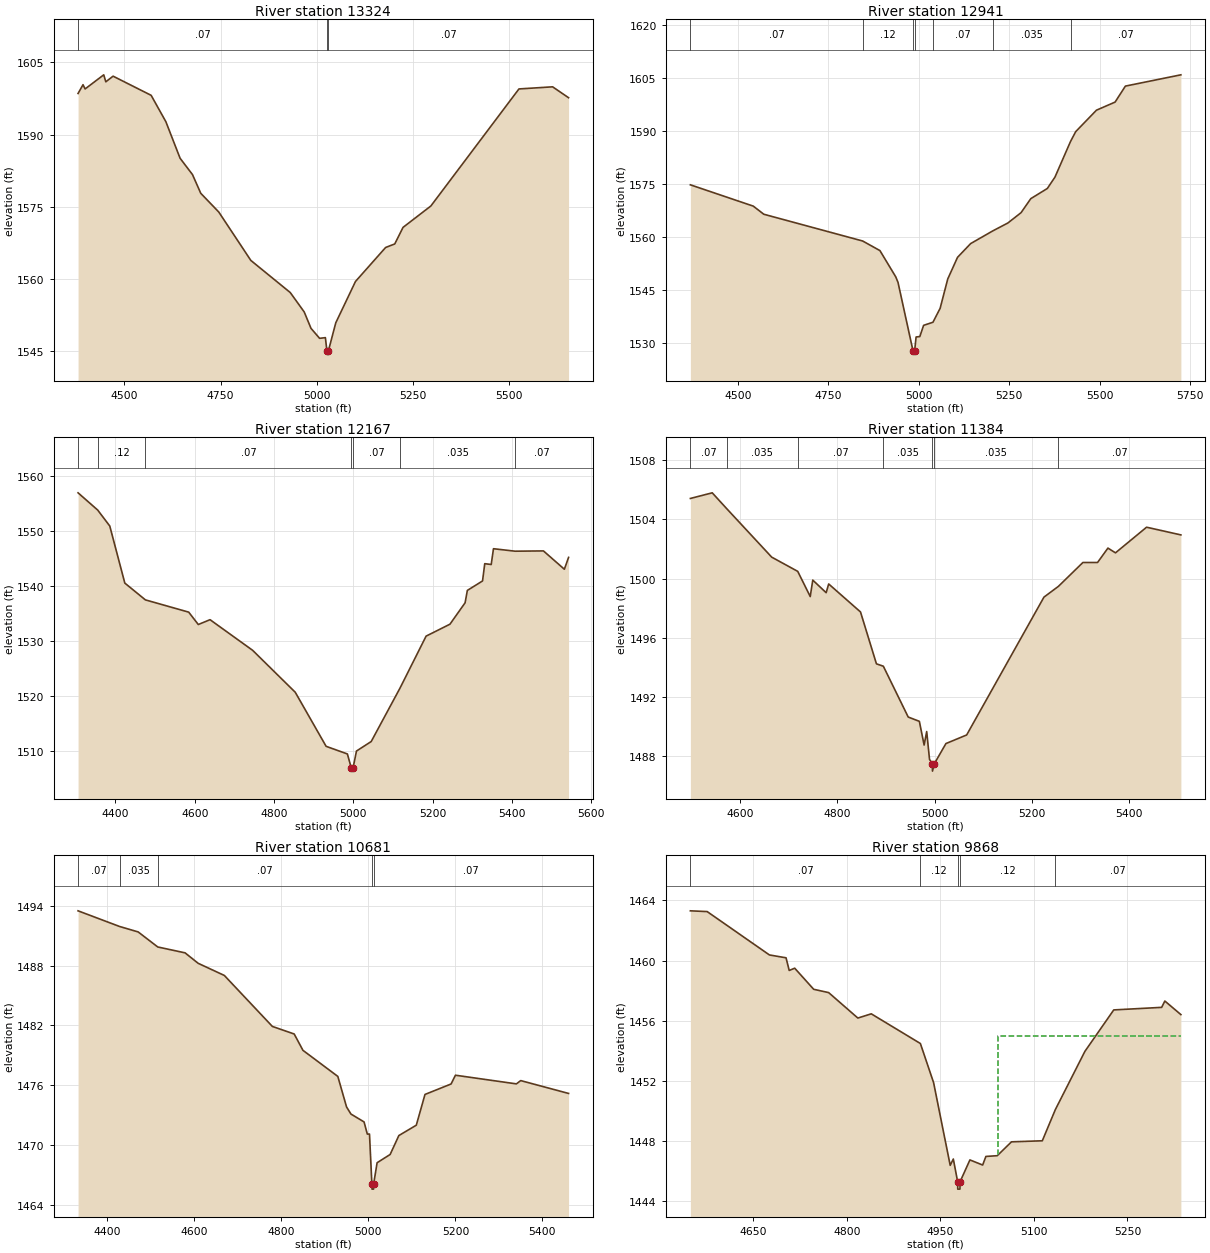
Type RM Length L Ch R = 1 ,13324   ,383,383,383
BEGIN DESCRIPTION:
Stream0192_DS 25.0
END DESCRIPTION:
XS GIS Cut Line= 3
      2132051.52     13911495.02        2131475.       13911725.
      2130926.51     13912083.58
#Sta/Elev= 30
  4379.3 1598.52  4392.2 1600.34  4397.6 1599.46  4446.1 1602.39  4451.5 1600.94
  4470.4 1602.11  4569.4 1598.14  4607.8 1592.65  4644.7 1585.08    4677 1581.69
  4698.5 1577.81  4745.3 1573.93  4828.8 1563.88  4931.3 1557.22  4967.7 1553.18
  4985.2  1549.8  5007.6 1547.72  5022.7 1547.86  5026.6 1545.15  5026.9 1544.65
  5030.6 1545.15  5049.7 1550.94    5101 1559.52  5179.4 1566.57  5203.1  1567.3
  5224.7 1570.74  5297.1 1575.18  5526.2 1599.46  5613.8  1599.9  5655.3 1597.64
#Mann= 3 ,-1 , 0
  4379.3     .07       0  5026.6     .05       0  5030.6     .07       0
Bank Sta=5026.6,5030.6
XS Rating Curve= 0 ,0
Exp/Cntr=0.3,0.1

Type RM Length L Ch R = 1 ,12941   ,774,774,774
BEGIN DESCRIPTION:
Stream0192_DS 24.0
END DESCRIPTION:
XS GIS Cut Line= 3
       2131780.7      13911047.1        2131275.       13911425.
      2130666.09     13911817.96
#Sta/Elev= 30
  4368.7 1574.74  4542.5 1568.72  4571.7 1566.42    4845 1558.85  4892.7 1556.14
  4936.4 1548.72  4942.7 1547.15  4984.5 1527.64  4984.7 1527.14  4988.5 1527.64
  4992.7  1531.7    5003 1531.83  5013.5    1535  5039.3 1535.87  5059.1 1539.81
  5080.2 1548.11  5107.2 1554.23  5143.5 1558.12  5204.7 1561.71  5246.5 1563.95
  5282.8 1566.86  5309.8 1570.83  5355.4  1573.7  5376.5  1576.9  5419.6    1587
  5433.9 1589.78  5491.3 1595.85  5542.8 1598.14  5571.3 1602.66  5724.7 1605.85
#Mann= 7 ,-1 , 0
  4368.7     .07       0    4845     .12       0  4984.5     .05       0
  4988.5     .12       0  5039.3     .07       0  5204.7    .035       0
  5419.6     .07       0
Bank Sta=4984.5,4988.5
XS Rating Curve= 0 ,0
Exp/Cntr=0.3,0.1

Type RM Length L Ch R = 1 ,12167   ,783,783,783
BEGIN DESCRIPTION:
Stream0192_DS 23.0
END DESCRIPTION:
XS GIS Cut Line= 3
      2131619.23     13910515.86        2130975.       13910775.
      2130495.65     13911030.73
#Sta/Elev= 30
  4305.6 1556.92  4355.1 1553.79  4385.6 1550.89  4423.6 1540.51  4475.5 1537.46
  4584.8 1535.23    4609 1532.98  4638.6 1533.86  4746.1 1528.29  4853.6 1520.67
  4931.5 1510.84  4985.2 1509.45  4995.3 1506.83  4995.6 1506.33  4999.3 1506.83
  5008.1 1509.98  5045.3 1511.71  5118.3 1521.47  5183.8 1530.87    5244 1533.04
  5282.2 1536.93  5287.9 1539.18  5326.2  1540.9  5331.8 1544.04  5348.1 1543.89
  5353.8 1546.76  5408.3 1546.31  5479.9 1546.36  5532.7 1543.03  5543.3 1545.18
#Mann= 7 ,-1 , 0
  4305.6     .07       0  4355.1     .12       0  4475.5     .07       0
  4995.3     .05       0  4999.3     .07       0  5118.3    .035       0
  5408.3     .07       0
Bank Sta=4995.3,4999.3
XS Rating Curve= 0 ,0
Exp/Cntr=0.3,0.1

Type RM Length L Ch R = 1 ,11384   ,703,703,703
BEGIN DESCRIPTION:
Stream0192_DS 22.0
END DESCRIPTION:
XS GIS Cut Line= 3
      2131254.68     13909927.31        2130775.       13910075.
      2130343.19     13910338.78
#Sta/Elev= 30
  4498.1 1505.41    4543 1505.79  4572.8 1504.72  4665.2 1501.45  4718.7 1500.49
  4744.4 1498.79  4749.6  1499.9  4777.1 1499.05  4782.3 1499.64  4847.7 1497.75
  4880.4 1494.25  4894.6 1494.09  4945.7 1490.66  4968.6 1490.37  4978.4 1488.77
  4983.7 1489.68  4989.5  1487.8  4995.4 1487.51  4995.6 1487.01  4999.4 1487.51
  5023.2 1488.87  5065.8 1489.45  5224.6 1498.75  5254.4 1499.48  5304.7 1501.09
  5334.8 1501.09  5356.1 1502.06  5371.6 1501.74  5435.5 1503.47    5506 1502.95
#Mann= 7 ,-1 , 0
  4498.1     .07       0  4572.8    .035       0  4718.7     .07       0
  4894.6    .035       0  4995.4    .035       0  4999.4    .035       0
  5254.4     .07       0
Bank Sta=4995.4,4999.4
XS Rating Curve= 0 ,0
Exp/Cntr=0.3,0.1

Type RM Length L Ch R = 1 ,10681   ,813,813,813
BEGIN DESCRIPTION:
Stream0192_DS 21.0
END DESCRIPTION:
XS GIS Cut Line= 3
      2131390.11     13909531.48        2130725.       13909475.
      2130265.04     13909489.81
#Sta/Elev= 30
  4332.5  1493.5  4427.8 1491.93  4470.7 1491.38  4515.7 1489.87  4578.5 1489.28
  4608.6 1488.23  4668.8 1487.01  4779.2 1481.89  4829.4 1481.13  4849.5 1479.49
  4929.7 1476.87  4949.8  1473.8  4959.9 1473.09    4990  1472.3  4997.5 1471.08
  5002.5 1471.08    5008 1466.05  5008.3 1465.55  5011.8 1465.55    5012 1466.05
    5020  1468.2    5050 1469.03    5070 1470.93  5110.1 1471.97  5130.1 1475.06
  5190.1 1476.11  5200.1 1476.99  5340.2 1476.12  5350.2 1476.45  5460.2 1475.16
#Mann= 5 ,-1 , 0
  4332.5     .07       0  4427.8    .035       0  4515.7     .07       0
    5008     .05       0    5012     .07       0
Bank Sta=5008,5012
XS Rating Curve= 0 ,0
Exp/Cntr=0.3,0.1

Type RM Length L Ch R = 1 ,9868    ,703,703,703
BEGIN DESCRIPTION:
Stream0192_DS 20.0
END DESCRIPTION:
XS GIS Cut Line= 3
      2131020.26     13908656.48        2130575.       13908725.
      2130249.69     13908807.46
#Sta/Elev= 30
  4549.5  1463.3  4576.4 1463.25  4676.2 1460.37  4702.8 1460.18  4707.9 1459.34
  4716.7 1459.49  4747.1 1458.09  4771.1 1457.87  4817.9 1456.18  4839.4 1456.46
  4918.1 1454.49  4939.3 1451.89  4965.9  1446.4  4970.9 1446.82  4977.8 1445.32
    4978 1444.82  4981.5 1444.82  4981.8 1445.32  4997.5 1446.76  5017.9 1446.42
  5023.1 1446.99  5041.3 1447.04  5064.1 1447.96  5113.5 1448.03  5134.4  1450.1
  5181.8 1453.97    5228 1456.72  5304.8 1456.89  5309.9 1457.31  5335.6 1456.41
#Mann= 5 ,-1 , 0
  4549.5     .07       0  4918.1     .12       0  4977.8     .05       0
  4981.8     .12       0  5134.4     .07       0
#XS Ineff= 2 , 0
       0                 5043.06       0    1455
Permanent Ineff=
       F       F
Bank Sta=4977.8,4981.8
XS Rating Curve= 0 ,0
Exp/Cntr=0.3,0.1

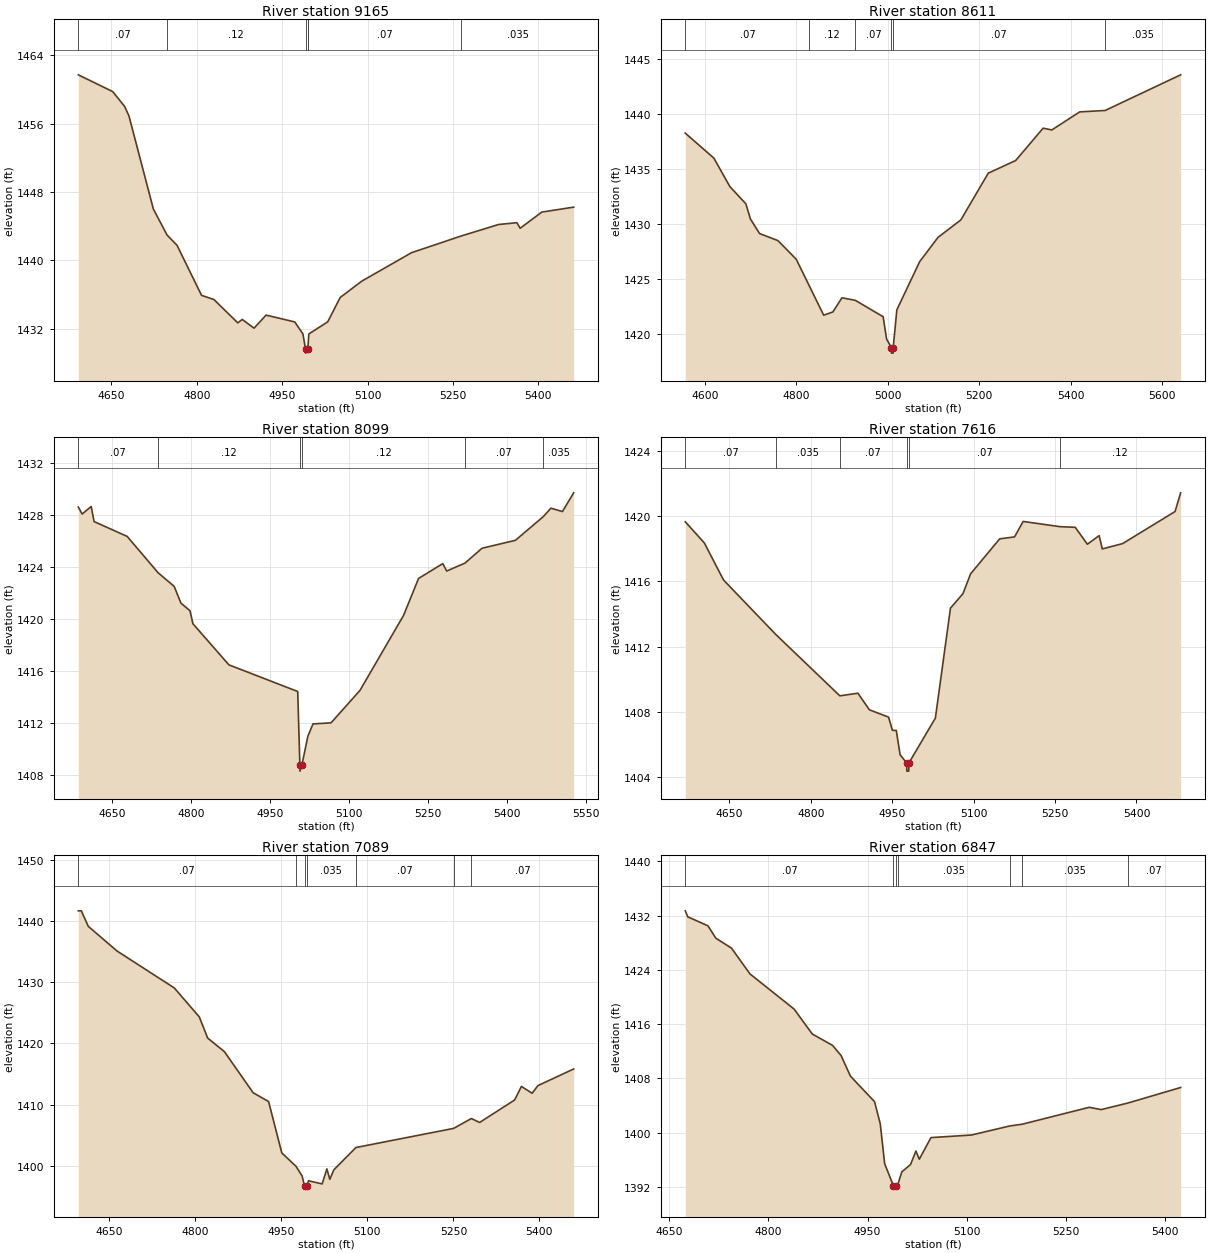
Type RM Length L Ch R = 1 ,9165    ,554,554,554
BEGIN DESCRIPTION:
Stream0192_DS 19.0
END DESCRIPTION:
XS GIS Cut Line= 3
      2130588.02      13907812.7        2130325.       13908125.
      2130104.03     13908530.73
#Sta/Elev= 30
  4591.7 1461.72  4652.1 1459.76  4673.2 1458.01  4680.7 1456.91  4723.6 1446.01
  4747.6 1442.98  4765.3 1441.76  4808.2 1435.92    4830 1435.43  4871.9  1432.7
  4879.7  1433.1  4900.5 1432.08  4921.6 1433.61    4972 1432.81  4986.3 1431.41
  4990.9 1429.66  4991.1 1429.16  4994.9 1429.66  4995.6 1430.34  4996.7  1431.4
  5029.9 1432.82  5051.8 1435.67  5089.7 1437.58  5177.1 1440.91  5264.6 1442.87
  5330.2 1444.21  5362.3 1444.42    5368 1443.77    5406 1445.66    5462 1446.24
#Mann= 6 ,-1 , 0
  4591.7     .07       0  4747.6     .12       0  4990.9     .05       0
  4994.9     .12       0  4995.6     .07       0  5264.6    .035       0
Bank Sta=4990.9,4994.9
XS Rating Curve= 0 ,0
Exp/Cntr=0.3,0.1

Type RM Length L Ch R = 1 ,8611    ,512,512,512
BEGIN DESCRIPTION:
Stream0192_DS 18.0
END DESCRIPTION:
XS GIS Cut Line= 3
      2129994.24     13907432.52        2129975.       13907875.
      2129983.82     13908515.84
#Sta/Elev= 30
  4557.1 1438.22  4619.6 1435.95  4654.7 1433.36  4689.7 1431.79  4699.7 1430.41
  4719.7 1429.09  4759.8 1428.45  4799.8 1426.76  4828.6 1424.32  4859.9 1421.67
  4879.9 1421.96  4899.9 1423.25  4929.1 1423.02    4990 1421.53  4997.5 1419.51
    5008 1418.72  5008.3 1418.22  5011.8 1418.22    5012 1418.72    5020 1422.16
    5070 1426.54    5110 1428.74    5160 1430.33    5220 1434.58    5280 1435.73
    5340 1438.67  5359.1 1438.51    5420 1440.15  5475.8 1440.28  5640.9 1443.52
#Mann= 6 ,-1 , 0
  4557.1     .07       0  4828.6     .12       0  4929.1     .07       0
    5008     .05       0    5012     .07       0  5475.8    .035       0
Bank Sta=5008,5012
XS Rating Curve= 0 ,0
Exp/Cntr=0.3,0.1

Type RM Length L Ch R = 1 ,8099    ,483,483,483
BEGIN DESCRIPTION:
Stream0192_DS 17.0
END DESCRIPTION:
XS GIS Cut Line= 3
      2129801.55      13907250.2        2129625.       13907625.
      2129405.69     13908104.42
#Sta/Elev= 30
  4585.7 1428.63  4592.9 1428.09  4610.2 1428.67  4615.7 1427.51  4678.6 1426.37
  4737.3 1423.58  4767.9 1422.53  4780.8 1421.24    4798 1420.66  4803.5 1419.66
  4871.9  1416.5  5002.7 1414.45  5006.8 1408.83    5007 1408.33  5010.8 1408.83
    5022 1411.01  5031.8 1411.96    5066 1412.04    5121 1414.53  5203.9  1420.3
  5232.4 1423.14  5278.4 1424.28  5285.9 1423.71  5320.7 1424.32    5353 1425.46
  5416.5 1426.07  5469.7  1427.9  5483.9 1428.54  5505.8 1428.28  5527.2 1429.72
#Mann= 6 ,-1 , 0
  4585.7     .07       0  4737.3     .12       0  5006.8     .05       0
  5010.8     .12       0  5320.7     .07       0  5469.7    .035       0
Bank Sta=5006.8,5010.8
XS Rating Curve= 0 ,0
Exp/Cntr=0.3,0.1

Type RM Length L Ch R = 1 ,7616    ,527,527,527
BEGIN DESCRIPTION:
Stream0192_DS 16.0
END DESCRIPTION:
XS GIS Cut Line= 3
      2129629.67     13907120.01        2129325.       13907425.
      2129087.98     13907844.01
#Sta/Elev= 30
  4568.9 1419.67    4604 1418.37  4639.4 1416.09  4735.4 1412.75  4853.6 1408.97
  4886.9 1409.13  4908.1 1408.11  4943.4 1407.66  4950.5 1406.85  4957.6 1406.84
  4964.6 1405.35  4976.8 1404.84    4977 1404.34  4980.5 1404.34  4980.8 1404.84
  5029.6  1407.6  5057.4 1414.36  5080.4 1415.25  5094.5 1416.47    5148 1418.62
  5175.4 1418.74  5191.3 1419.69    5259 1419.37  5287.2 1419.33  5309.6 1418.29
  5331.3 1418.82    5337    1418  5374.6 1418.33  5471.1  1420.3  5481.4 1421.45
#Mann= 6 ,-1 , 0
  4568.9     .07       0  4735.4    .035       0  4853.6     .07       0
  4976.8     .05       0  4980.8     .07       0    5259     .12       0
Bank Sta=4976.8,4980.8
XS Rating Curve= 0 ,0
Exp/Cntr=0.3,0.1

Type RM Length L Ch R = 1 ,7089    ,242,242,242
BEGIN DESCRIPTION:
Stream0192_DS 15.0
END DESCRIPTION:
XS GIS Cut Line= 3
      2129306.41     13906741.07      2129064.11     13907064.09
      2129147.05     13907516.25
#Sta/Elev= 30
  4596.2 1441.68  4601.5 1441.68  4613.6 1439.14  4663.6 1435.12  4763.6 1429.07
  4807.1 1424.34  4821.7 1420.88  4850.9 1418.66  4900.9 1411.95  4927.9 1410.51
  4950.9 1402.11  4975.6 1399.93  4986.3 1398.35  4990.5 1396.69  4990.8 1396.19
  4994.5 1396.69  4997.4 1397.56  5021.3 1397.04  5029.5  1399.5  5034.6 1397.79
  5041.6 1399.34  5080.1 1402.99  5250.5 1406.12  5281.3 1407.73  5295.8 1407.09
  5356.8 1410.76  5368.6 1412.98  5387.3 1411.86  5397.4 1413.11  5459.7 1415.83
#Mann= 7 ,-1 , 0
  4596.2     .07       0  4975.6    .035       0  4990.5    .035       0
  4994.5    .035       0  5080.1     .07       0  5250.5    .035       0
  5281.3     .07       0
Bank Sta=4990.5,4994.5
XS Rating Curve= 0 ,0
Exp/Cntr=0.3,0.1

Type RM Length L Ch R = 1 ,6847    ,479,479,479
BEGIN DESCRIPTION:
Stream0192_DS 14.0
END DESCRIPTION:
XS GIS Cut Line= 3
      2129051.48     13906646.05        2128875.       13906925.
      2128972.91     13907331.79
#Sta/Elev= 30
  4674.6  1432.7  4678.3 1431.82  4708.9 1430.49  4720.7 1428.67  4744.4  1427.2
  4772.4 1423.39    4839 1418.21  4866.5 1414.53    4897 1412.86    4910 1411.36
  4924.1 1408.32  4960.6 1404.55  4969.2 1401.29  4975.9 1395.39  4989.1 1392.15
  4989.4 1391.65  4993.1 1392.15  4996.4 1392.53  5001.7 1394.18    5015 1395.28
  5023.1 1397.27  5028.2 1396.06  5045.8 1399.25    5107 1399.63  5164.6 1400.96
  5183.5 1401.22    5285 1403.72    5303 1403.38  5343.1 1404.34  5423.1 1406.64
#Mann= 7 ,-1 , 0
  4674.6     .07       0  4989.1    .035       0  4993.1     .07       0
  4996.4    .035       0  5164.6     .07       0  5183.5    .035       0
  5343.1     .07       0
Bank Sta=4989.1,4993.1
XS Rating Curve= 0 ,0
Exp/Cntr=0.3,0.1

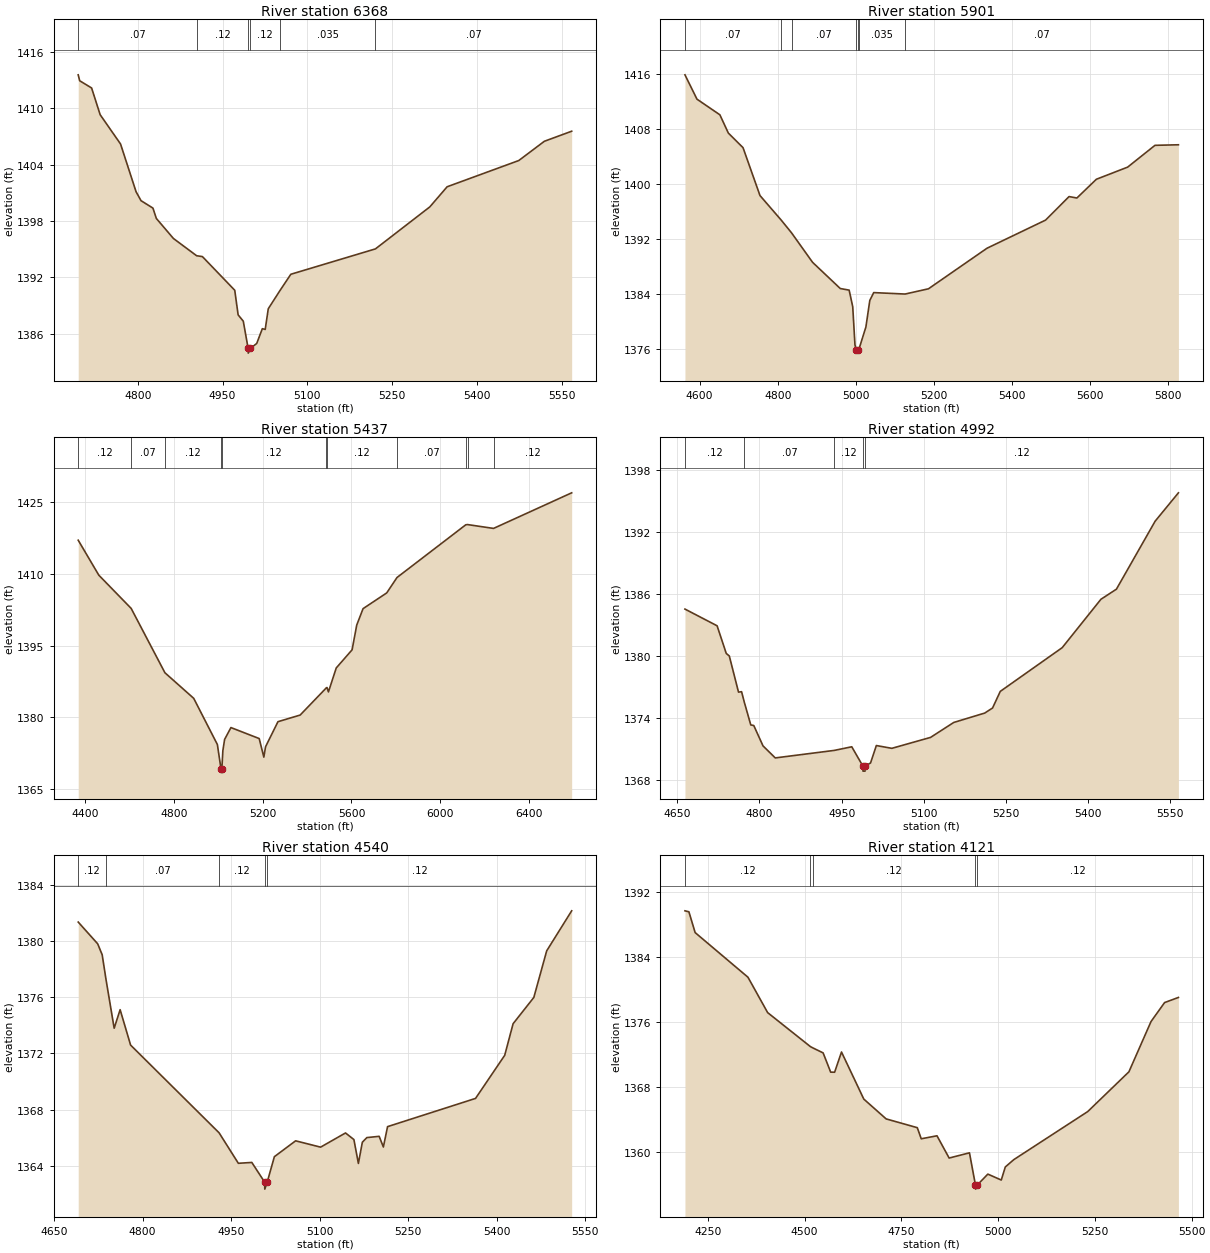
Type RM Length L Ch R = 1 ,6368    ,467,467,467
BEGIN DESCRIPTION:
Stream0192_DS 13.0
END DESCRIPTION:
XS GIS Cut Line= 3
       2128780.6     13906557.56        2128525.       13906725.
      2128410.99     13907280.77
#Sta/Elev= 30
  4694.7 1413.56  4697.3 1412.93  4718.4 1412.16  4733.5 1409.32  4769.6  1406.2
    4797 1401.13  4805.8 1400.17  4826.9 1399.38  4832.9 1398.28  4863.1 1396.15
  4904.2 1394.31  4914.4 1394.22  4971.6 1390.64  4977.6 1388.02  4986.7 1387.35
  4995.3 1384.45  4995.5 1383.95  4999.3 1384.45  5010.5 1384.98  5020.4 1386.55
  5025.5 1386.47  5030.9 1388.67  5051.4 1390.59  5070.8 1392.34  5220.5 1395.04
  5316.7 1399.51  5347.3 1401.65    5474 1404.44  5519.3 1406.49  5567.6 1407.56
#Mann= 6 ,-1 , 0
  4694.7     .07       0  4904.2     .12       0  4995.3     .05       0
  4999.3     .12       0  5051.4    .035       0  5220.5     .07       0
Bank Sta=4995.3,4999.3
XS Rating Curve= 0 ,0
Exp/Cntr=0.3,0.1

Type RM Length L Ch R = 1 ,5901    ,464,464,464
BEGIN DESCRIPTION:
Stream0192_DS 12.0
END DESCRIPTION:
XS GIS Cut Line= 3
      2128561.91     13906208.56        2128175.       13906425.
      2128192.09     13907244.99
#Sta/Elev= 30
  4562.5 1415.87  4593.3 1412.33  4651.9 1410.06  4673.6  1407.4  4711.2 1405.28
  4754.6 1398.32  4809.1 1394.74  4835.4  1392.9  4889.3 1388.61  4960.2  1384.8
  4982.9 1384.57  4992.1 1382.15  4997.8 1376.62    5001 1375.91  5001.2 1375.41
    5005 1375.91  5007.6 1375.91  5025.8 1379.21  5035.8 1383.07  5045.8 1384.21
  5126.1    1384  5185.9 1384.76  5335.9 1390.66  5485.9 1394.75    5546 1398.17
    5566 1397.96    5616 1400.69    5696 1402.45    5766 1405.62    5826  1405.7
#Mann= 7 ,-1 , 0
  4562.5     .07       0  4809.1     .12       0  4835.4     .07       0
    5001     .05       0    5005     .07       0  5007.6    .035       0
  5126.1     .07       0
Bank Sta=5001,5005
XS Rating Curve= 0 ,0
Exp/Cntr=0.3,0.1

Type RM Length L Ch R = 1 ,5437    ,445,445,445
BEGIN DESCRIPTION:
Stream0192_DS 11.0
END DESCRIPTION:
XS GIS Cut Line= 3
      2128478.78     13905966.08        2127875.       13906125.
      2126846.09     13907351.54
#Sta/Elev= 30
  4367.6 1417.08  4460.5 1409.76  4606.4  1402.8  4758.6 1389.33  4888.5 1383.97
  4995.2  1374.3  5011.4 1369.23  5011.7 1368.73  5015.4 1369.23  5019.9 1373.01
  5027.7 1375.36  5056.3 1377.85  5183.8 1375.55  5204.7 1371.66  5212.4 1373.83
  5268.4 1379.08  5368.5 1380.47  5486.8 1386.18  5489.6 1386.23  5496.1 1385.32
  5531.2 1390.33  5602.7 1394.13  5623.6 1399.31  5652.2 1402.75  5758.8 1406.04
  5805.2 1409.27  6115.5 1420.31  6123.6 1420.35  6240.6 1419.55  6592.9    1427
#Mann= 11 ,-1 , 0
  4367.6     .12       0  4606.4     .07       0  4758.6     .12       0
  5011.4     .05       0  5015.4     .12       0  5486.8     .07       0
  5489.6     .12       0  5805.2     .07       0  6115.5     .12       0
  6123.6     .07       0  6240.6     .12       0
Bank Sta=5011.4,5015.4
XS Rating Curve= 0 ,0
Exp/Cntr=0.3,0.1

Type RM Length L Ch R = 1 ,4992    ,452,452,452
BEGIN DESCRIPTION:
Stream0192_DS 10.0
END DESCRIPTION:
XS GIS Cut Line= 3
      2127874.97     13905675.01        2127575.       13905825.
      2127174.97     13906225.03
#Sta/Elev= 30
  4663.9 1384.53  4722.6 1382.91  4739.3 1380.23  4744.9 1379.98  4761.7 1376.48
  4767.3 1376.52  4772.3  1375.5  4784.1  1373.3  4789.6 1373.24  4806.4 1371.27
  4828.8  1370.1  4936.7 1370.83  4968.5 1371.18  4988.7 1369.32    4989 1368.82
  4992.8 1368.82  4993.1 1369.32  5002.8 1369.61  5013.4  1371.3  5041.7 1371.03
  5112.4 1372.09  5154.8 1373.54  5211.4 1374.45  5225.6 1374.94  5239.7 1376.55
  5352.8 1380.79  5423.5 1385.48  5451.8 1386.46  5522.5 1393.05    5565  1395.8
#Mann= 5 ,-1 , 0
  4663.9     .12       0  4772.3     .07       0  4936.7     .12       0
  4988.7     .05       0  4993.1     .12       0
Bank Sta=4988.7,4993.1
XS Rating Curve= 0 ,0
Exp/Cntr=0.3,0.1

Type RM Length L Ch R = 1 ,4540    ,419,419,419
BEGIN DESCRIPTION:
Stream0192_DS 9.0
END DESCRIPTION:
XS GIS Cut Line= 3
      2127825.03     13905475.01        2127525.       13905425.
      2127124.98     13905775.01
#Sta/Elev= 30
    4691 1381.36    4724 1379.81  4731.6 1379.03  4738.2 1377.24  4751.9  1373.8
    4762 1375.12  4779.7  1372.6  4929.6 1366.35  4962.2 1364.18    4985 1364.24
  5006.7 1362.84    5007 1362.34  5011.1 1362.84  5023.2 1364.65  5059.2 1365.78
  5101.5 1365.33  5143.7 1366.34  5157.9 1365.87  5165.5 1364.17  5172.2 1365.68
  5179.8 1366.01  5200.7  1366.1  5207.8 1365.34  5214.9 1366.79  5363.9  1368.8
  5413.3 1371.87  5427.5 1374.12  5462.6 1375.99  5484.4 1379.31  5526.7 1382.16
#Mann= 5 ,-1 , 0
    4691     .12       0  4738.2     .07       0  4929.6     .12       0
  5006.7     .05       0  5011.1     .12       0
Bank Sta=5006.7,5011.1
XS Rating Curve= 0 ,0
Exp/Cntr=0.3,0.1

Type RM Length L Ch R = 1 ,4121    ,433,433,433
BEGIN DESCRIPTION:
Stream0192_DS 8.0
END DESCRIPTION:
XS GIS Cut Line= 3
      2128075.04     13905275.01        2127275.       13905125.
      2126924.97     13905425.03
#Sta/Elev= 30
  4190.9 1389.72  4201.1  1389.6  4217.2 1387.04  4353.7 1381.54  4404.6 1377.18
  4515.2 1372.99  4521.6 1372.83  4547.9 1372.22  4567.4 1369.85  4577.6 1369.84
  4595.4 1372.33    4653 1366.53  4710.7 1364.09  4791.2 1363.01  4801.4 1361.64
  4842.1 1362.01  4873.5 1359.27    4926 1359.91  4941.5 1355.94  4941.8 1355.44
  4946.1 1355.94  4973.5 1357.29  5008.2 1356.56  5018.6 1358.17  5040.5 1359.07
  5231.5 1364.99    5338 1369.89  5395.1 1376.08  5430.2 1378.42  5465.9 1379.05
#Mann= 5 ,-1 , 0
  4190.9     .12       0  4515.2     .07       0  4521.6     .12       0
  4941.5     .05       0  4946.1     .12       0
Bank Sta=4941.5,4946.1
XS Rating Curve= 0 ,0
Exp/Cntr=0.3,0.1

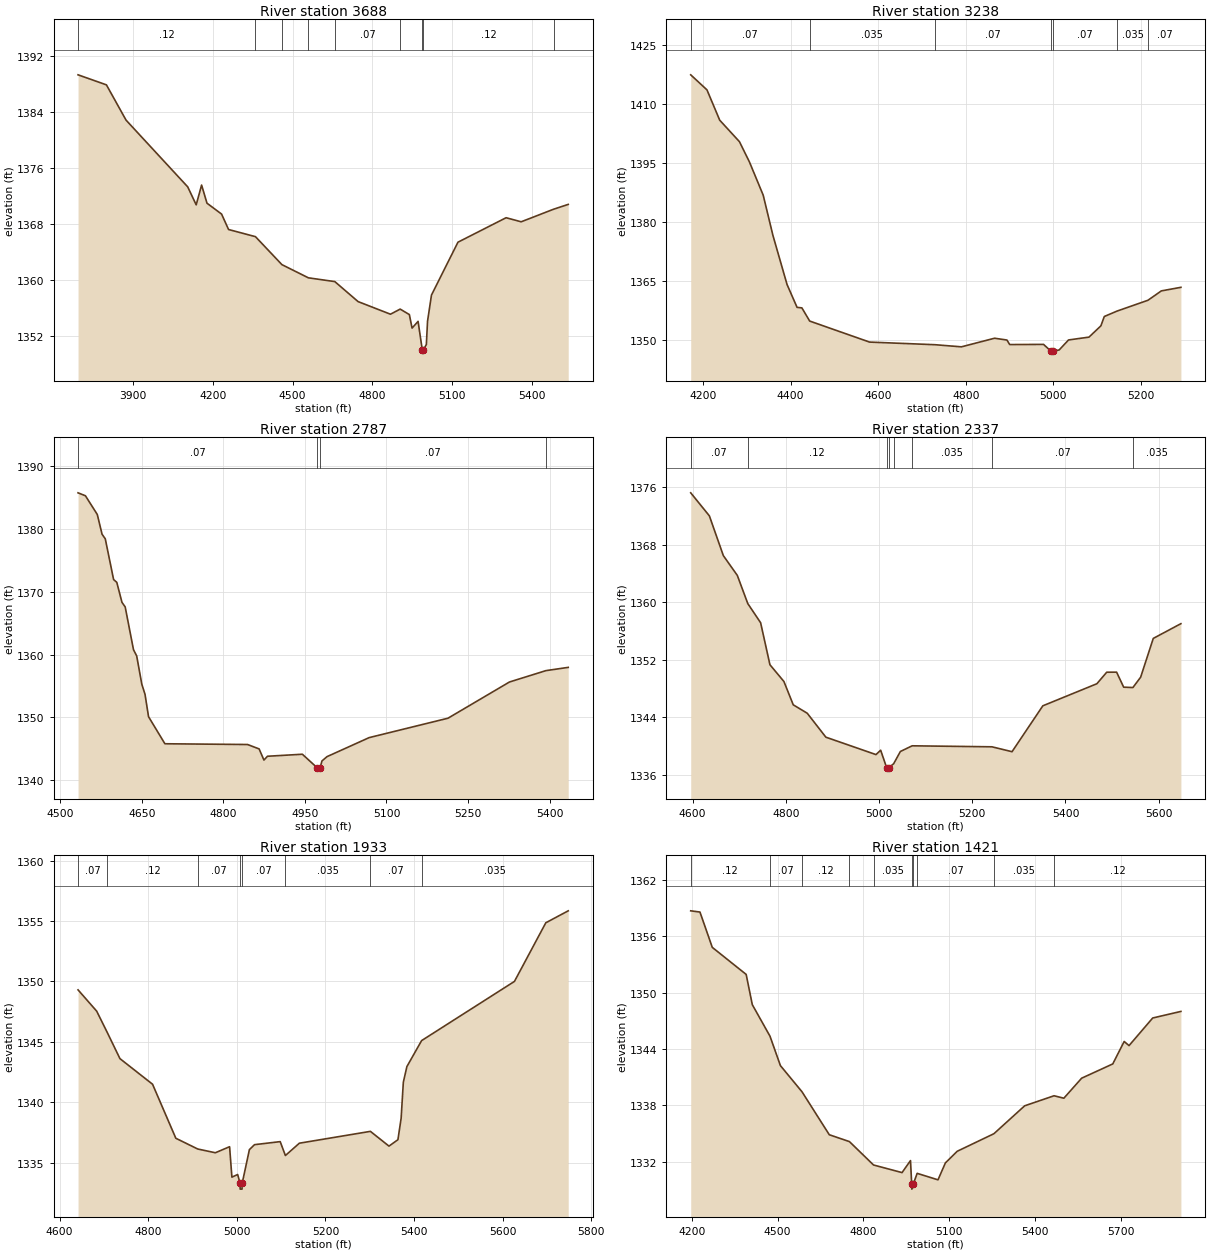
Type RM Length L Ch R = 1 ,3688    ,450,450,450
BEGIN DESCRIPTION:
Stream0192_DS 7.0
END DESCRIPTION:
XS GIS Cut Line= 3
      2128462.88     13904937.74        2127175.       13904725.
      2126734.81     13905030.76
#Sta/Elev= 30
  3694.2  1389.3  3800.8 1387.87  3874.5 1382.84  4106.2 1373.32    4138 1370.76
  4158.3 1373.58  4178.6 1370.99  4233.4 1369.44  4259.6 1367.24  4360.6 1366.22
    4460 1362.23  4559.4 1360.35  4658.8 1359.81  4746.1 1356.96  4867.8 1355.16
  4904.2 1355.89  4938.7 1355.11  4948.9 1353.18  4971.5 1354.14  4987.1 1350.11
  4987.4 1349.61  4991.8 1350.11  5002.6 1350.84    5007 1354.15  5021.8 1357.89
  5121.3 1365.43  5302.1 1368.92  5358.8 1368.34  5480.3 1370.13  5535.5 1370.82
#Mann= 9 ,-1 , 0
  3694.2     .12       0  4360.6    .035       0    4460     .07       0
  4559.4    .035       0  4658.8     .07       0  4904.2     .12       0
  4987.1     .05       0  4991.8     .12       0  5480.3     .07       0
Bank Sta=4987.1,4991.8
XS Rating Curve= 0 ,0
Exp/Cntr=0.3,0.1

Type RM Length L Ch R = 1 ,3238    ,451,451,451
BEGIN DESCRIPTION:
Stream0192_DS 6.0
END DESCRIPTION:
XS GIS Cut Line= 3
      2127925.01       13903925.        2127175.       13904275.
        2126925.       13904425.
#Sta/Elev= 30
  4171.9 1417.47    4209 1413.64  4238.1 1405.93  4283.1 1400.47  4305.9 1395.32
  4337.4 1386.85  4359.5 1376.66  4391.8 1364.14  4414.7 1358.31  4425.7 1358.18
  4443.5 1354.83  4580.2 1349.48  4729.8 1348.81  4789.9 1348.27  4865.6 1350.46
  4893.9    1350  4900.2 1348.85  4977.5 1348.89  4994.3 1347.17  4994.7 1346.67
  4999.2 1347.17  5013.2 1347.48  5034.5 1350.02  5081.2 1350.74  5108.4 1353.61
  5116.2 1355.99  5145.4 1357.37  5215.9 1360.12  5246.4  1362.5  5291.1 1363.41
#Mann= 7 ,-1 , 0
  4171.9     .07       0  4443.5    .035       0  4729.8     .07       0
  4994.3     .05       0  4999.2     .07       0  5145.4    .035       0
  5215.9     .07       0
Bank Sta=4994.3,4999.2
XS Rating Curve= 0 ,0
Exp/Cntr=0.3,0.1

Type RM Length L Ch R = 1 ,2787    ,450,450,450
BEGIN DESCRIPTION:
Stream0192_DS 5.0
END DESCRIPTION:
XS GIS Cut Line= 3
        2127625.       13903625.        2127225.       13903875.
      2126875.01     13904124.99
#Sta/Elev= 30
  4532.6 1385.78  4546.2 1385.31    4568 1382.33  4576.8 1379.18  4582.7 1378.45
    4598 1371.97  4603.9 1371.51  4613.4 1368.33  4619.3 1367.61  4634.6 1360.79
  4640.5 1359.79  4649.9 1355.29  4655.8 1353.68  4662.3 1350.11  4692.4  1345.8
  4844.5 1345.68  4865.7 1344.98  4874.6  1343.2  4881.1 1343.81  4945.3 1344.13
    4973 1341.94  4973.3 1341.44  4977.9 1341.94  4981.3 1343.06  4990.7 1343.75
  5068.2 1346.78  5213.2 1349.87  5326.3 1355.64  5393.3 1357.45  5434.4 1357.97
#Mann= 4 ,-1 , 0
  4532.6     .07       0    4973     .05       0  4977.9     .07       0
  5393.3    .035       0
Bank Sta=4973,4977.9
XS Rating Curve= 0 ,0
Exp/Cntr=0.3,0.1

Type RM Length L Ch R = 1 ,2337    ,404,404,404
BEGIN DESCRIPTION:
Stream0192_DS 4.0
END DESCRIPTION:
XS GIS Cut Line= 3
      2127574.98       13903475.        2127175.       13903475.
        2126825.       13904025.
#Sta/Elev= 30
  4595.8 1375.19  4635.8 1371.99  4665.8 1366.46  4695.8 1363.71  4718.2  1359.8
  4745.8 1357.13  4765.8 1351.29  4795.8 1348.96  4815.8 1345.72  4845.8 1344.55
  4885.8 1341.22  4993.3  1338.8  5003.4 1339.41  5016.1    1337  5016.5  1336.5
  5021.1    1337  5031.2 1337.52  5045.7 1339.23    5071 1340.02  5242.3 1339.88
  5285.3  1339.2  5351.4 1345.58  5467.4 1348.65  5488.5 1350.25  5509.7 1350.26
  5524.9 1348.17  5544.7 1348.12  5561.3 1349.56  5588.4 1354.95  5647.7    1357
#Mann= 8 ,-1 , 0
  4595.8     .07       0  4718.2     .12       0  5016.1     .05       0
  5021.1     .12       0  5031.2     .07       0    5071    .035       0
  5242.3     .07       0  5544.7    .035       0
Bank Sta=5016.1,5021.1
XS Rating Curve= 0 ,0
Exp/Cntr=0.3,0.1

Type RM Length L Ch R = 1 ,1933    ,512,512,512
BEGIN DESCRIPTION:
Stream0192_DS 3.0
END DESCRIPTION:
XS GIS Cut Line= 3
      2127224.98     13903125.01       2126884.8     13903234.62
        2126775.     13903975.01
#Sta/Elev= 30
  4641.8  1349.3  4683.8 1347.54  4707.5 1345.79  4736.3 1343.61  4809.9 1341.49
  4862.4 1337.02  4911.8 1336.13  4951.6 1335.82  4983.7 1336.32  4988.9  1333.8
  5001.9 1334.02  5007.2 1333.31  5007.6 1332.81  5011.8 1332.81  5012.2 1333.31
  5028.4 1336.08    5040 1336.49  5097.9 1336.74  5109.6 1335.59  5141.1 1336.61
  5301.4 1337.59  5343.3 1336.37  5363.5  1336.9  5370.7 1338.67  5375.7 1341.66
  5383.7 1342.95  5416.9  1345.1  5626.4    1350  5697.1 1354.85  5747.7 1355.84
#Mann= 8 ,-1 , 0
  4641.8     .07       0  4707.5     .12       0  4911.8     .07       0
  5007.2     .05       0  5012.2     .07       0  5109.6    .035       0
  5301.4     .07       0  5416.9    .035       0
Bank Sta=5007.2,5012.2
XS Rating Curve= 0 ,0
Exp/Cntr=0.3,0.1

Type RM Length L Ch R = 1 ,1421    ,430,430,430
BEGIN DESCRIPTION:
Stream0192_DS 2.0
END DESCRIPTION:
XS GIS Cut Line= 3
        2127275.       13902675.        2126525.       13902975.
      2126287.68     13903850.12
#Sta/Elev= 30
  4196.4 1358.71  4228.7 1358.58  4271.8 1354.82  4390.3 1351.94  4411.8 1348.72
  4473.7 1345.36  4510.1 1342.23  4585.5 1339.45  4681.1 1334.87  4751.5 1334.14
  4835.8 1331.65  4935.5 1330.84  4965.1 1332.12  4969.3 1329.58  4969.7 1329.08
  4974.4 1329.58  4988.4 1330.76  5061.3 1330.07  5087.1 1331.87  5128.5 1333.11
  5256.9 1334.98  5364.4 1337.95  5467.2 1339.02  5501.5 1338.76  5563.7 1340.89
  5672.6 1342.41  5712.5  1344.8  5729.5 1344.36  5812.3  1347.3  5910.9    1348
#Mann= 10 ,-1 , 0
  4196.4     .12       0  4473.7     .07       0  4585.5     .12       0
  4751.5     .07       0  4835.8    .035       0  4969.3     .05       0
  4974.4    .035       0  4988.4     .07       0  5256.9    .035       0
  5467.2     .12       0
Bank Sta=4969.3,4974.4
XS Rating Curve= 0 ,0
Exp/Cntr=0.3,0.1

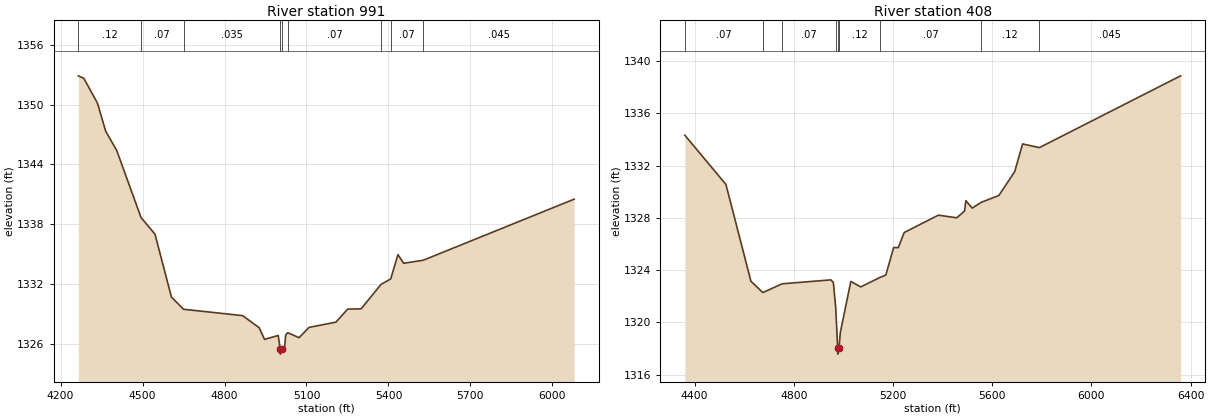
Type RM Length L Ch R = 1 ,991     ,583,583,583
BEGIN DESCRIPTION:
Stream0192_DS 1.0
END DESCRIPTION:
XS GIS Cut Line= 3
      2127075.01       13902575.        2126325.       13902625.
      2125624.99     13903425.01
#Sta/Elev= 30
    4265 1352.88  4285.1 1352.63  4335.2 1350.13  4365.2 1347.32  4405.3 1345.41
  4494.5 1338.67  4545.6    1337  4605.8 1330.69    4650 1329.47  4866.3 1328.83
  4926.5 1327.63  4946.5 1326.45  4996.6 1326.84    5004 1325.47  5004.4 1324.97
  5009.3 1325.47    5020 1325.67  5023.8 1326.88  5031.3 1327.12  5073.1 1326.62
  5109.2 1327.65  5207.9 1328.18  5250.6 1329.48    5300 1329.51  5372.7 1331.96
  5408.3 1332.51  5434.8 1334.95  5455.6 1334.08  5527.8 1334.39  6079.7 1340.51
#Mann= 9 ,-1 , 0
    4265     .12       0  4494.5     .07       0    4650    .035       0
    5004    .035       0  5009.3    .035       0  5031.3     .07       0
  5372.7     .12       0  5408.3     .07       0  5527.8    .045       0
Bank Sta=5004,5009.3
XS Rating Curve= 0 ,0
Exp/Cntr=0.3,0.1

Type RM Length L Ch R = 1 ,408     ,0,0,0
BEGIN DESCRIPTION:
Stream 0192_DS 0.0
END DESCRIPTION:
XS GIS Cut Line= 3
      2126809.76     13902025.02       2126009.6     13902120.87
      2125609.76     13903245.43
#Sta/Elev= 30
  4360.7 1334.32  4526.6 1330.55  4627.3 1323.15  4675.3 1322.28  4753.3 1322.95
  4949.6 1323.25  4959.7 1323.06  4969.3 1321.13  4977.1 1318.07  4977.5 1317.57
  4982.7 1318.07    4988 1319.24  5030.2 1323.13  5070.3 1322.71    5148 1323.44
  5171.4 1323.62  5202.8 1325.72  5221.9 1325.72  5245.2 1326.87  5383.2  1328.2
  5457.5    1328  5488.9 1328.52  5494.2 1329.31  5519.7 1328.74  5554.7 1329.17
  5627.3 1329.71    5691 1331.53  5722.8 1333.65  5790.8 1333.37  6360.1 1338.86
#Mann= 9 ,-1 , 0
  4360.7     .07       0  4675.3    .035       0  4753.3     .07       0
  4969.3     .12       0  4977.1     .05       0  4982.7     .12       0
    5148     .07       0  5554.7     .12       0  5790.8    .045       0
Bank Sta=4977.1,4982.7
XS Rating Curve= 0 ,0
Exp/Cntr=0.3,0.1

Chan Stop Cuts=-1
Use User Specified Reach Order=0
Composite Channel Slope=5