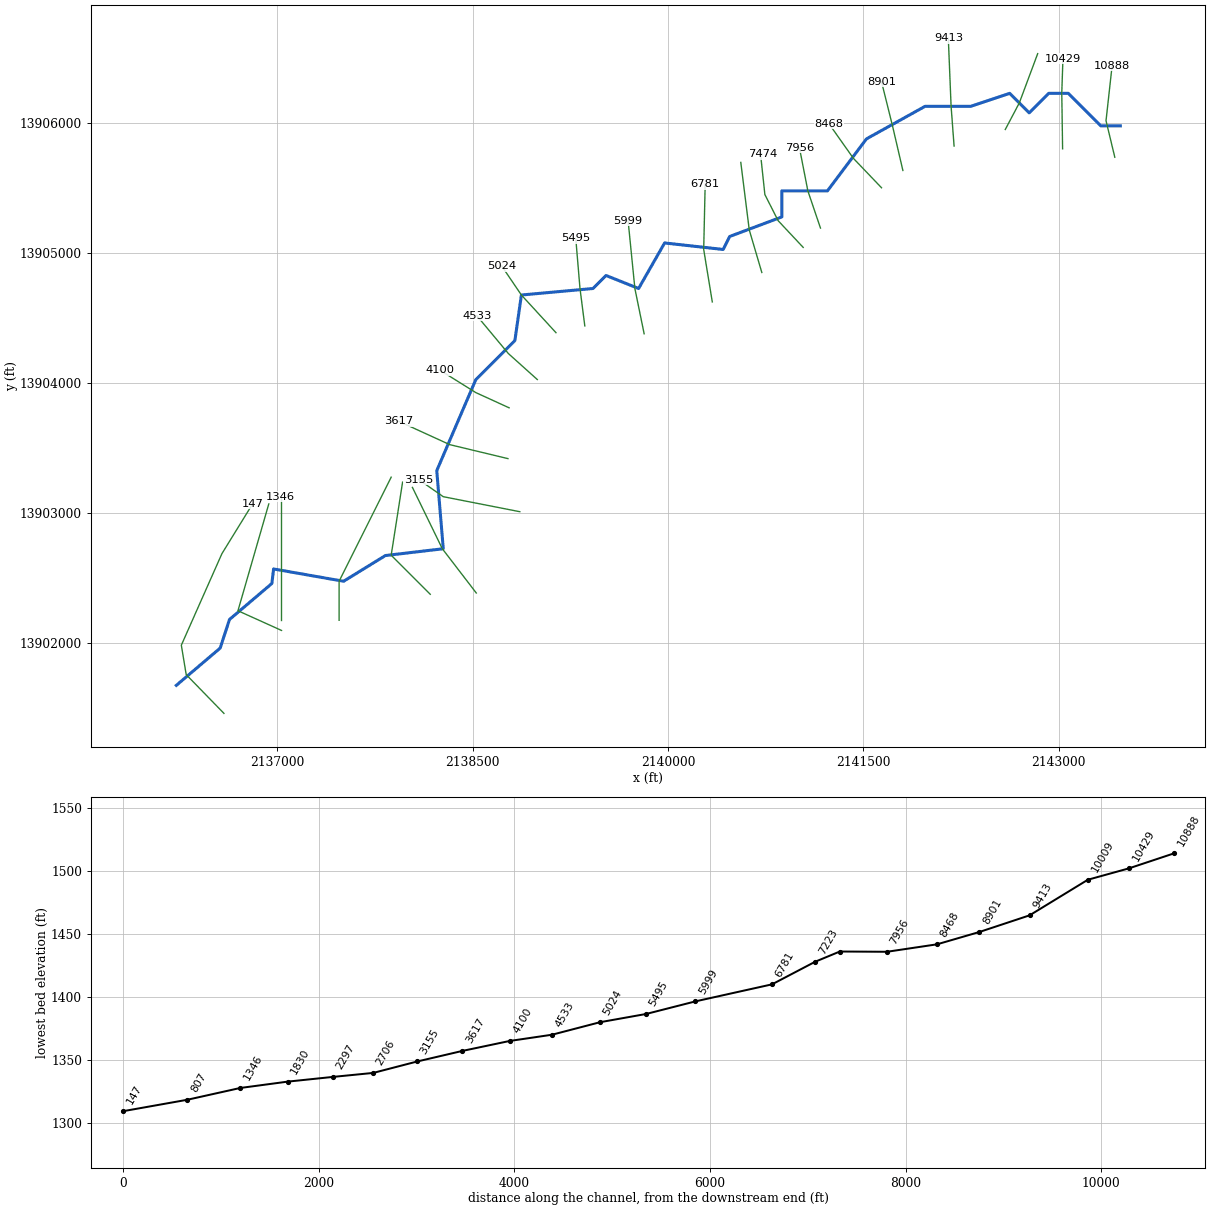
--- Stream0193_DS.prj (project) ---

Proj Title=Stream0193_DS Base Level Engineering
Current Plan=p01
Default Exp/Contr=0.3,0.1
English Units
Geom File=g01
Flow File=f01
Plan File=p01
Y Axis Title=Elevation
X Axis Title(PF)=Main Channel Distance
X Axis Title(XS)=Station
BEGIN DESCRIPTION:
Stream0193_DS
END DESCRIPTION:
DSS Export Rating Curves= 0
DSS Export Rating Curve Sorted= 0
DSS Export Volume Flow Curves= 0
DXF OffsetX= 0
DXF OffsetY= 0
DXF ScaleX= 1
DXF ScaleY= 10

--- Stream0193_DS.p01 (plan) ---

Plan Title=Multiple Run
Short Identifier=Multiple
Geom File=g01
Flow File=f01
Subcritical Flow
K Sum by GR= 0
Std Step Tol= 0.01
Critical Tol= 0.01
Num of Std Step Trials= 20
Max Error Tol= 0.3
Flow Tol Ratio= 0.001
Split Flow NTrial= 30
Split Flow Tol= 0.02
Split Flow Ratio= 0.02
Log Output Level= 0
Friction Slope Method= 1
Unsteady Friction Slope Method= 2
Unsteady Bridges Friction Slope Method= 1
Parabolic Critical Depth
Global Vel Dist=  1 , 1 , 1
Global Log Level= 0
CheckData=True
Encroach Param= -1, 0, 0, 0
BEGIN DESCRIPTION:
Multiple Run
END DESCRIPTION:

--- Stream0193_DS.f01 (steady flow) ---

Flow Title=Multiple
Number of Profiles=7
Profile Names=10-year,25-year,50-year,1pct_min,100-year,1pct_plu,500-year
River Rch & RM= Stream0193_DS,Reach-1,10888
     280     437     577     373     743    1483    1211
River Rch & RM= Stream0193_DS,Reach-1,10429
     655    1083    1482     987    1969    3929    3430
River Rch & RM= Stream0193_DS,Reach-1,6781
    1530    2654    3749    2566    5121   10217    9447
Boundary for River Rch & Prof#=Stream0193_DS,Reach-1,1
Up Type=0
Dn Type=3
Dn Slope=0.005
Boundary for River Rch & Prof#=Stream0193_DS,Reach-1,2
Up Type=0
Dn Type=3
Dn Slope=0.005
Boundary for River Rch & Prof#=Stream0193_DS,Reach-1,3
Up Type=0
Dn Type=3
Dn Slope=0.005
Boundary for River Rch & Prof#=Stream0193_DS,Reach-1,4
Up Type=0
Dn Type=3
Dn Slope=0.005
Boundary for River Rch & Prof#=Stream0193_DS,Reach-1,5
Up Type=0
Dn Type=3
Dn Slope=0.005
Boundary for River Rch & Prof#=Stream0193_DS,Reach-1,6
Up Type=0
Dn Type=3
Dn Slope=0.005
Boundary for River Rch & Prof#=Stream0193_DS,Reach-1,7
Up Type=0
Dn Type=3
Dn Slope=0.005

--- Stream0193_DS.g01 (geometry) ---

Geom Title=Existing Conditions
Program Version=4.10

River Reach=Stream0193_DS   ,Reach-1
Reach XY= 30
        2143475.       13905975.        2143325.       13905975.
        2143075.       13906225.        2142925.       13906225.
        2142775.       13906075.        2142625.       13906225.
        2142325.       13906125.        2141975.       13906125.
        2141525.       13905875.        2141225.       13905475.
        2140875.       13905475.        2140875.       13905275.
        2140475.       13905125.        2140425.       13905025.
        2139975.       13905075.        2139775.       13904725.
        2139525.       13904825.        2139425.       13904725.
        2138875.       13904675.        2138825.       13904325.
        2138525.       13904025.        2138225.       13903325.
        2138275.       13902725.      2137830.52     13902672.65
      2137509.66     13902474.96      2136972.01     13902569.55
      2136958.76     13902457.96      2136633.14     13902181.06
      2136561.74     13901961.35        2136225.       13901675.

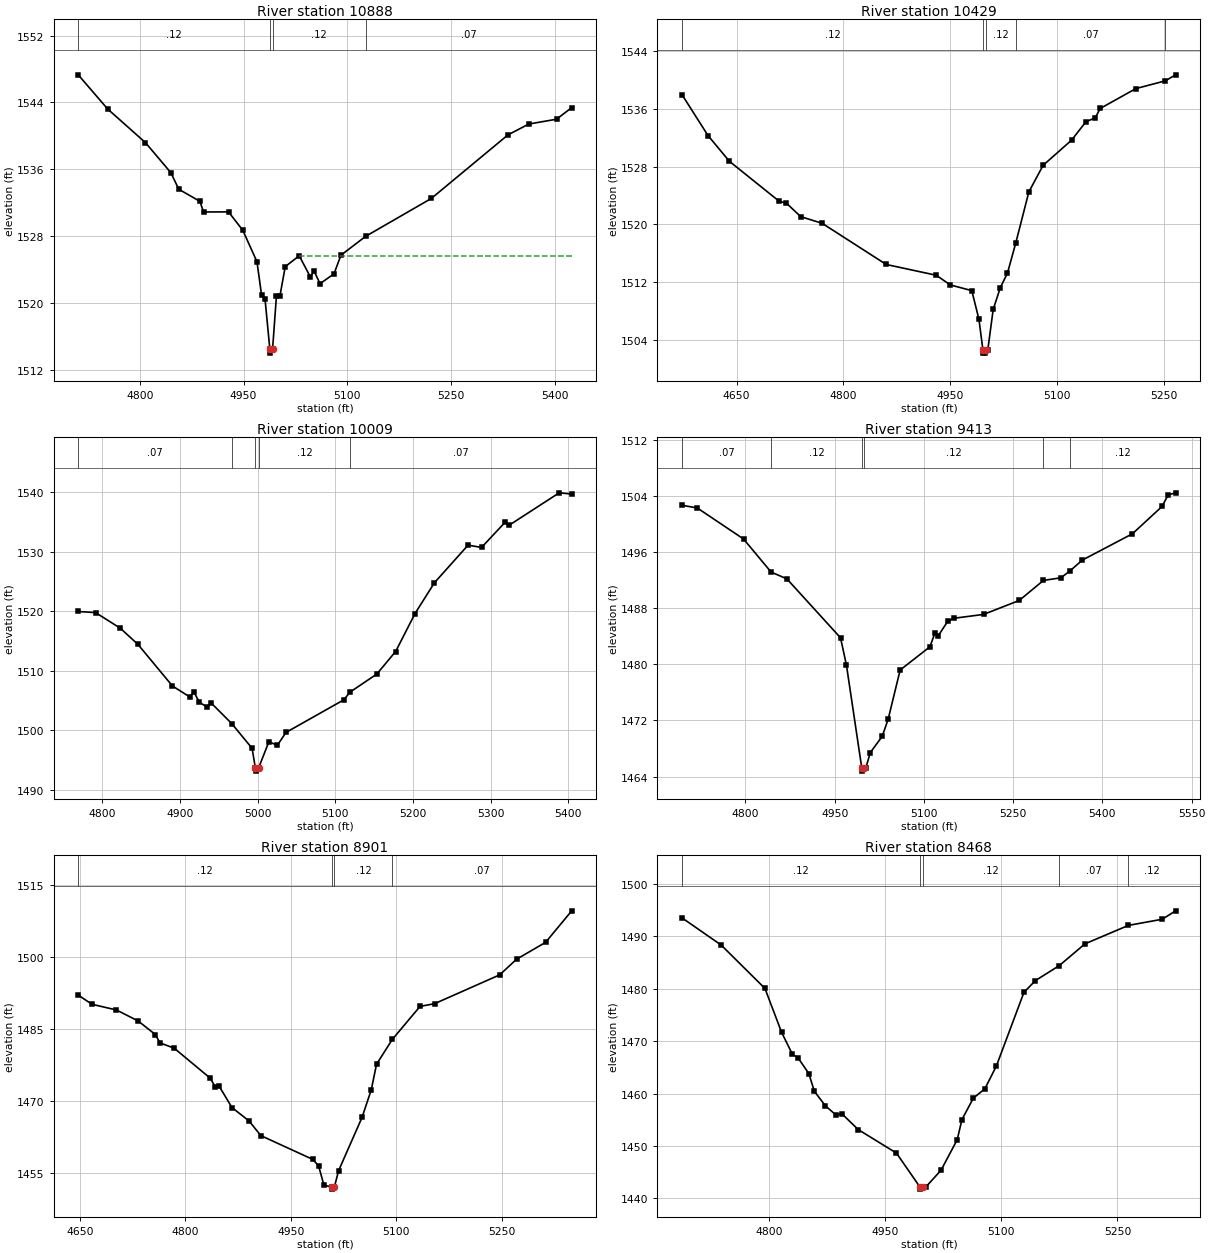
Type RM Length L Ch R = 1 ,10888   ,459,459,459
BEGIN DESCRIPTION:
Stream0193_DS 21.0
END DESCRIPTION:
XS GIS Cut Line= 3
      2143432.27     13905733.62      2143364.72     13906014.72
      2143411.44     13906436.74
#Sta/Elev= 30
  4710.9 1547.31  4753.5 1543.22  4808.1  1539.2  4844.9  1535.6  4856.3 1533.62
  4886.9 1532.17  4892.1  1530.9  4928.3 1530.91  4948.9 1528.71  4969.4 1524.95
    4976 1520.99  4981.1 1520.45    4988 1514.51  4988.3 1514.01    4992 1514.51
  4997.6 1520.89  5002.7 1520.89  5010.3 1524.36  5030.5 1525.66  5046.8  1523.1
  5051.8 1523.86  5060.6 1522.32  5080.8  1523.5  5090.8 1525.72  5126.5 1527.98
  5221.6 1532.52  5332.3 1540.12  5362.5 1541.42  5402.7    1542  5424.6 1543.39
#Mann= 4 ,-1 , 0
  4710.9     .12       0    4988     .05       0    4992     .12       0
  5126.5     .07       0
#XS Ineff= 2 , 0
       0                 5030.72       0 1525.66
Permanent Ineff=
       F       F
Bank Sta=4988,4992
XS Rating Curve= 0 ,0
Exp/Cntr=0.3,0.1

Type RM Length L Ch R = 1 ,10429   ,420,420,420
BEGIN DESCRIPTION:
Stream0193_DS 20.0
END DESCRIPTION:
XS GIS Cut Line= 3
      2143031.23     13905798.75        2143025.       13906225.
      2143033.82     13906490.75
#Sta/Elev= 30
  4573.7 1537.98    4610 1532.33    4640 1528.76    4710  1523.2    4720 1522.95
    4740 1521.08    4770 1520.16    4860 1514.44    4930 1512.95    4950  1511.6
    4980 1510.81    4990 1506.83  4995.5 1502.64  4995.7 1502.14  4999.2 1502.14
  4999.5 1502.64  5002.5 1502.64    5010 1508.21    5020 1511.23    5030 1513.24
  5041.8 1517.48    5060 1524.51    5080  1528.2  5120.1 1531.71  5140.1 1534.26
    5153 1534.78  5160.1 1536.09  5210.1 1538.85  5251.3 1539.92  5265.9 1540.76
#Mann= 5 ,-1 , 0
  4573.7     .12       0  4995.5     .05       0  4999.5     .12       0
  5041.8     .07       0  5251.3     .12       0
Bank Sta=4995.5,4999.5
XS Rating Curve= 0 ,0
Exp/Cntr=0.3,0.1

Type RM Length L Ch R = 1 ,10009   ,596,596,596
BEGIN DESCRIPTION:
Stream0193_DS 19.0
END DESCRIPTION:
XS GIS Cut Line= 3
      2142591.13     13905947.16      2142698.81     13906151.19
      2142839.99     13906530.04
#Sta/Elev= 30
  4769.3 1519.93  4791.7 1519.74  4823.4 1517.12    4846 1514.42  4890.5 1507.41
  4912.5 1505.59  4918.2 1506.37  4925.2 1504.68  4934.5  1503.9  4940.2 1504.57
  4966.8 1501.09    4993 1496.93  4997.3 1493.59  4997.6 1493.09  5001.3 1493.59
  5014.7 1498.05  5025.4 1497.41  5036.7  1499.6  5110.8 1505.06  5119.4 1506.41
  5153.5 1509.41  5177.7  1513.2  5202.7 1519.59  5227.7 1524.77  5270.9 1531.08
  5288.3  1530.7  5318.7 1534.95  5324.2 1534.47  5388.2 1539.88  5404.3 1539.68
#Mann= 5 ,-1 , 0
  4769.3     .07       0  4966.8     .12       0  4997.3     .05       0
  5001.3     .12       0  5119.4     .07       0
Bank Sta=4997.3,5001.3
XS Rating Curve= 0 ,0
Exp/Cntr=0.3,0.1

Type RM Length L Ch R = 1 ,9413    ,512,512,512
BEGIN DESCRIPTION:
Stream0193_DS 18.0
END DESCRIPTION:
XS GIS Cut Line= 3
       2142197.9     13905819.56        2142175.       13906125.
      2142153.63     13906647.66
#Sta/Elev= 30
  4693.7 1502.66  4719.2 1502.28  4796.9 1497.86  4843.3 1493.14  4869.6 1492.19
  4959.9 1483.78  4969.9 1479.86  4995.5 1465.28  4995.7 1464.78  4999.5 1465.28
  5002.5 1465.28    5010 1467.43    5030 1469.74    5040  1472.2  5060.1 1479.19
  5110.1  1482.5  5118.7  1484.5  5123.7 1484.02  5140.1 1486.13  5150.1 1486.56
  5200.2 1487.11  5260.2  1489.1    5301 1491.96  5330.3 1492.33  5345.9 1493.34
  5366.2 1494.85  5450.4  1498.6  5500.4 1502.51  5510.4 1504.14  5523.1 1504.44
#Mann= 6 ,-1 , 0
  4693.7     .07       0  4843.3     .12       0  4995.5     .05       0
  4999.5     .12       0    5301     .07       0  5345.9     .12       0
Bank Sta=4995.5,4999.5
XS Rating Curve= 0 ,0
Exp/Cntr=0.3,0.1

Type RM Length L Ch R = 1 ,8901    ,433,433,433
BEGIN DESCRIPTION:
Stream0193_DS 17.0
END DESCRIPTION:
XS GIS Cut Line= 3
      2141804.68     13905632.03        2141725.       13905975.
      2141640.61     13906314.36
#Sta/Elev= 30
  4647.9 1492.05  4667.5 1490.13  4702.3 1488.94  4733.1 1486.65  4757.8  1483.8
  4763.9  1482.1  4784.4 1480.97  4835.7 1474.71  4843.1 1472.81  4848.2 1473.08
  4866.5  1468.6  4890.9 1465.79  4907.6 1462.74  4981.3 1457.79  4989.7 1456.45
  4997.4 1452.36  5008.3 1452.08  5008.6 1451.58  5012.3 1452.08  5018.1  1455.4
  5051.5 1466.53  5064.6 1472.28  5072.1 1477.61  5094.6 1482.81    5134 1489.69
  5154.6 1490.25  5247.3 1496.27  5271.2 1499.52  5312.5 1503.04  5349.7 1509.62
#Mann= 4 ,-1 , 0
  4647.9     .12       0  5008.3     .05       0  5012.3     .12       0
  5094.6     .07       0
Bank Sta=5008.3,5012.3
XS Rating Curve= 0 ,0
Exp/Cntr=0.3,0.1

Type RM Length L Ch R = 1 ,8468    ,512,512,512
BEGIN DESCRIPTION:
Stream0193_DS 16.0
END DESCRIPTION:
XS GIS Cut Line= 3
      2141640.63     13905499.23        2141425.       13905725.
      2141237.49     13905990.69
#Sta/Elev= 30
  4687.8 1493.53  4738.2 1488.36  4794.8 1480.07  4816.2 1471.72  4830.3 1467.48
  4837.2 1466.89  4851.4 1463.84  4858.6 1460.44  4872.8 1457.68  4886.9 1455.86
  4893.8  1456.2  4915.2 1453.14  4964.6 1448.65  4994.5 1442.27  4994.8 1441.77
  4998.5 1442.27  5003.1 1442.27  5022.2 1445.38  5043.1 1451.21  5049.2 1455.06
    5064 1459.15  5078.8 1460.92  5093.6 1465.25  5129.3 1479.34  5144.1 1481.58
  5174.8 1484.42  5208.1 1488.59  5264.2 1492.11  5307.8 1493.28  5325.2 1494.89
#Mann= 5 ,-1 , 0
  4687.8     .12       0  4994.5     .05       0  4998.5     .12       0
  5174.8     .07       0  5264.2     .12       0
Bank Sta=4994.5,4998.5
XS Rating Curve= 0 ,0
Exp/Cntr=0.3,0.1

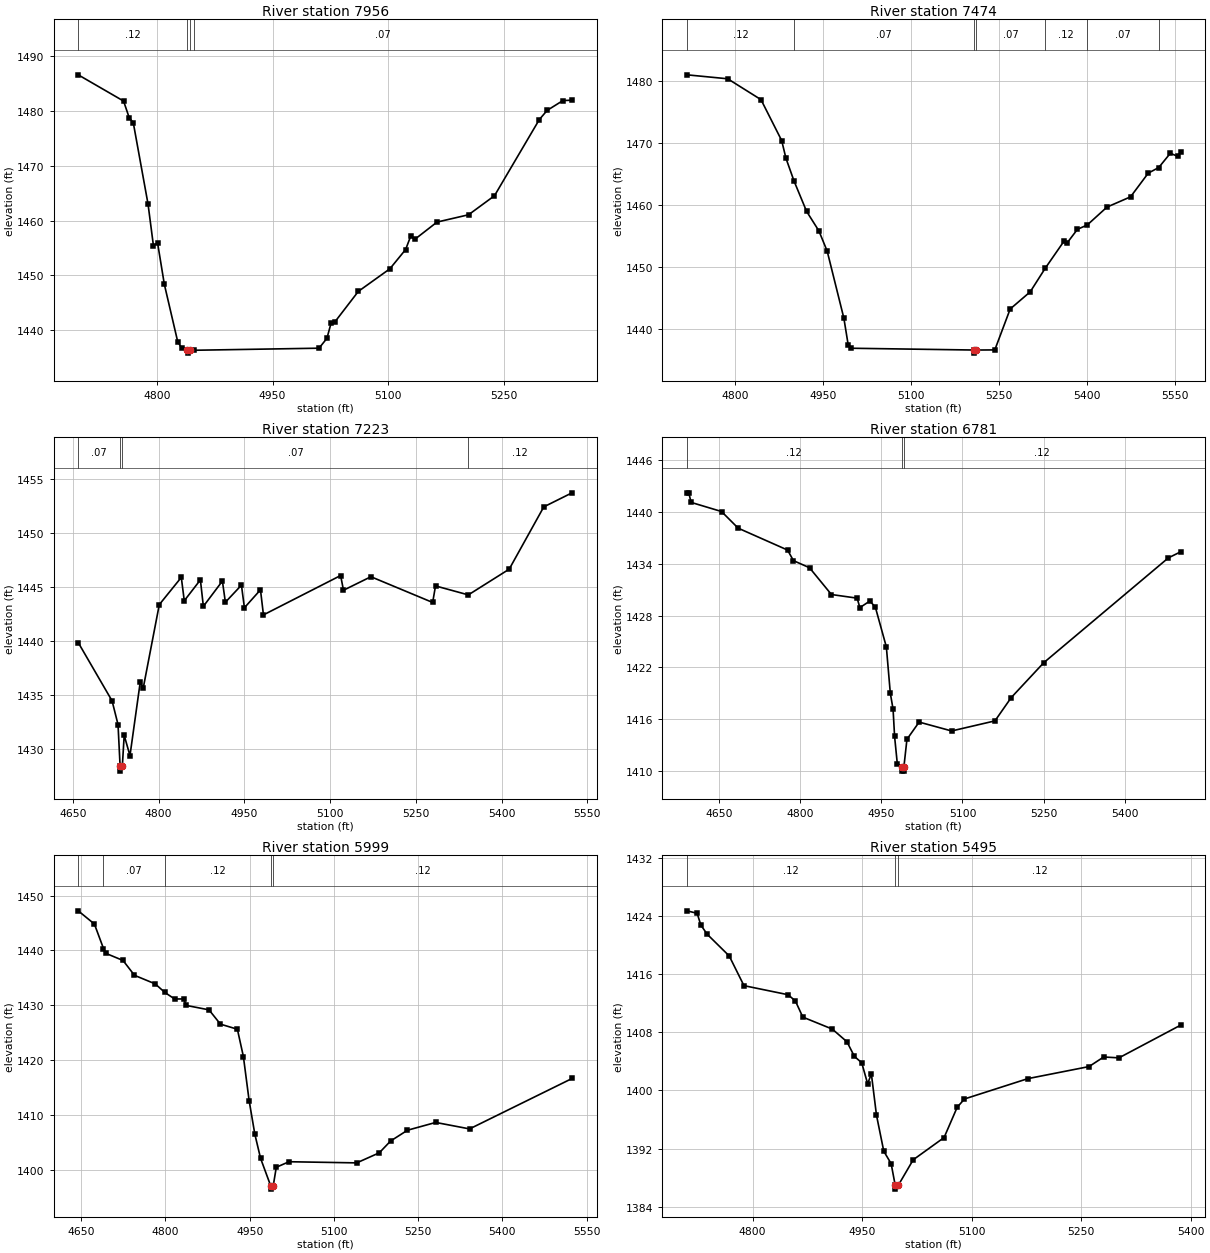
Type RM Length L Ch R = 1 ,7956    ,482,482,482
BEGIN DESCRIPTION:
Stream0193_DS 15.0
END DESCRIPTION:
XS GIS Cut Line= 3
      2141171.85     13905189.37        2141075.       13905475.
       2141010.4     13905806.56
#Sta/Elev= 30
  4698.4 1486.55  4757.1 1481.77  4764.4 1478.74  4769.7 1477.81  4788.8 1462.99
  4795.8 1455.39  4801.1 1455.96  4809.9 1448.38  4827.2 1437.93  4832.5 1436.74
  4839.6 1436.34  4839.9 1435.84  4843.6 1436.34  4847.8 1436.36  5010.2 1436.74
  5020.4 1438.53  5025.8  1441.3  5030.9 1441.56  5061.1 1447.09  5101.9  1451.2
  5122.3 1454.71    5129 1457.18  5134.1 1456.56    5163 1459.72  5203.8 1461.05
  5237.4 1464.52  5295.5 1478.41  5305.6 1480.07    5326 1481.86  5337.8 1481.93
#Mann= 4 ,-1 , 0
  4698.4     .12       0  4839.6     .05       0  4843.6     .12       0
  4847.8     .07       0
Bank Sta=4839.6,4843.6
XS Rating Curve= 0 ,0
Exp/Cntr=0.3,0.1

Type RM Length L Ch R = 1 ,7474    ,251,251,251
BEGIN DESCRIPTION:
Stream0193_DS 14.0
END DESCRIPTION:
XS GIS Cut Line= 5
      2141039.06     13905040.89      2140846.49     13905246.49
      2140744.78     13905447.16      2140710.92     13905764.87
      2140723.97     13905757.04
#Sta/Elev= 30
  4718.3    1481  4787.8 1480.36  4844.5 1476.99  4879.7 1470.39    4887 1467.53
  4900.8 1463.84  4922.2 1458.94  4943.2 1455.78  4957.3 1452.51  4985.7 1441.69
    4993 1437.42  4997.4 1436.83  5207.6 1436.54  5207.8 1436.04  5211.6 1436.54
  5242.9 1436.56  5269.1 1443.17  5303.3 1445.95  5328.8 1449.75  5361.5 1454.22
  5366.5 1453.89  5383.7 1456.04  5400.4 1456.74    5434 1459.63  5474.2 1461.29
  5504.4 1465.12  5522.2 1466.02    5542 1468.33  5554.5 1467.83  5559.7 1468.55
#Mann= 7 ,-1 , 0
  4718.3     .12       0  4900.8     .07       0  5207.6     .05       0
  5211.6     .07       0  5328.8     .12       0  5400.4     .07       0
  5522.2     .12       0
Bank Sta=5207.6,5211.6
XS Rating Curve= 0 ,0
Exp/Cntr=0.3,0.1

Type RM Length L Ch R = 1 ,7223    ,442,442,442
BEGIN DESCRIPTION:
Stream0193_DS 13.0
END DESCRIPTION:
XS GIS Cut Line= 3
      2140721.34      13904848.2        2140625.       13905175.
      2140559.94     13905694.04
#Sta/Elev= 30
  4659.3 1439.84  4718.5 1434.45  4728.9 1432.26  4732.5 1428.45  4732.7 1427.95
  4736.5 1428.45  4739.7 1431.27  4749.8 1429.38  4767.8  1436.2    4773 1435.63
  4801.1 1443.35  4839.6 1445.87  4844.8 1443.71    4873 1445.64  4878.2 1443.19
  4911.5 1445.53  4916.7 1443.57  4944.8 1445.15    4950 1443.06  4978.1 1444.72
  4983.3  1442.4  5118.3 1446.04  5123.3 1444.68  5171.3 1445.93  5279.3 1443.55
  5284.3 1445.08  5341.7 1444.25  5413.2 1446.63  5473.7 1452.39  5523.1 1453.69
#Mann= 4 ,-1 , 0
  4659.3     .07       0  4732.5     .05       0  4736.5     .07       0
  5341.7     .12       0
Bank Sta=4732.5,4736.5
XS Rating Curve= 0 ,0
Exp/Cntr=0.3,0.1

Type RM Length L Ch R = 1 ,6781    ,782,782,782
BEGIN DESCRIPTION:
Stream0193_DS 12.0
END DESCRIPTION:
XS GIS Cut Line= 3
      2140341.12     13904621.68        2140275.       13905025.
      2140286.44     13905527.87
#Sta/Elev= 30
  4591.3 1442.24  4594.7 1442.24    4599 1441.13  4655.2 1440.07  4685.9 1438.14
  4777.1  1435.6    4788 1434.37  4817.6 1433.55  4858.1 1430.44  4905.5 1430.02
  4910.6 1428.92  4929.1 1429.69  4939.2 1428.97  4959.5 1424.36  4966.8    1419
  4971.9 1417.13  4974.7 1413.97  4979.7 1410.81  4987.9 1410.45  4988.1 1409.95
  4991.6 1409.95  4991.9 1410.45  4997.5 1413.64    5020 1415.64    5080 1414.61
    5160 1415.78    5190 1418.48  5250.1 1422.53  5480.1 1434.69    5503  1435.4
#Mann= 3 ,-1 , 0
  4591.3     .12       0  4987.9     .05       0  4991.9     .12       0
Bank Sta=4987.9,4991.9
XS Rating Curve= 0 ,0
Exp/Cntr=0.3,0.1

Type RM Length L Ch R = 1 ,5999    ,504,504,504
BEGIN DESCRIPTION:
Stream0193_DS 11.0
END DESCRIPTION:
XS GIS Cut Line= 3
       2139817.7      13904376.8      2139746.51       13904725.
      2139694.43     13905246.61
#Sta/Elev= 30
  4644.6 1447.22  4673.4 1444.81  4689.6 1440.34  4693.8 1439.46  4724.4 1438.16
  4744.8 1435.45  4781.7 1433.89  4798.7 1432.34  4816.3 1431.13  4832.2 1431.14
  4837.3 1429.95  4877.5 1429.15  4897.9 1426.54  4928.1 1425.61  4938.8 1420.63
    4949 1412.59  4959.2 1406.45  4969.4 1402.05  4987.8 1396.93    4988 1396.43
  4991.8 1396.93  4997.4 1400.42  5020.1 1401.43  5140.7 1401.22  5180.9 1403.06
    5201 1405.21  5231.1 1407.18  5281.4  1408.6  5341.7 1407.42  5524.2 1416.62
#Mann= 5 ,-1 , 0
  4644.6     .12       0  4689.6     .07       0  4798.7     .12       0
  4987.8     .05       0  4991.8     .12       0
Bank Sta=4987.8,4991.8
XS Rating Curve= 0 ,0
Exp/Cntr=0.3,0.1

Type RM Length L Ch R = 1 ,5495    ,471,471,471
BEGIN DESCRIPTION:
Stream0193_DS 10.0
END DESCRIPTION:
XS GIS Cut Line= 3
      2139361.97     13904437.57        2139325.       13904725.
      2139292.54     13905110.13
#Sta/Elev= 30
  4710.2 1424.73  4724.2 1424.39  4729.2 1422.78  4737.9 1421.51  4768.1 1418.52
  4788.3 1414.43  4848.8 1413.18  4858.8 1412.31  4868.9  1410.1  4909.3 1408.45
  4929.4  1406.7  4939.5  1404.7  4949.6 1403.81  4957.7 1400.92  4962.8 1402.29
  4969.8  1396.6  4979.8 1391.64  4989.9 1389.92  4995.5 1386.92  4995.7 1386.42
  4999.5 1386.92  5020.1 1390.46  5062.4 1393.52  5080.3 1397.68  5090.3 1398.83
  5177.1 1401.63  5260.9 1403.29    5281 1404.61  5301.9 1404.49  5386.5    1409
#Mann= 3 ,-1 , 0
  4710.2     .12       0  4995.5     .05       0  4999.5     .12       0
Bank Sta=4995.5,4999.5
XS Rating Curve= 0 ,0
Exp/Cntr=0.3,0.1

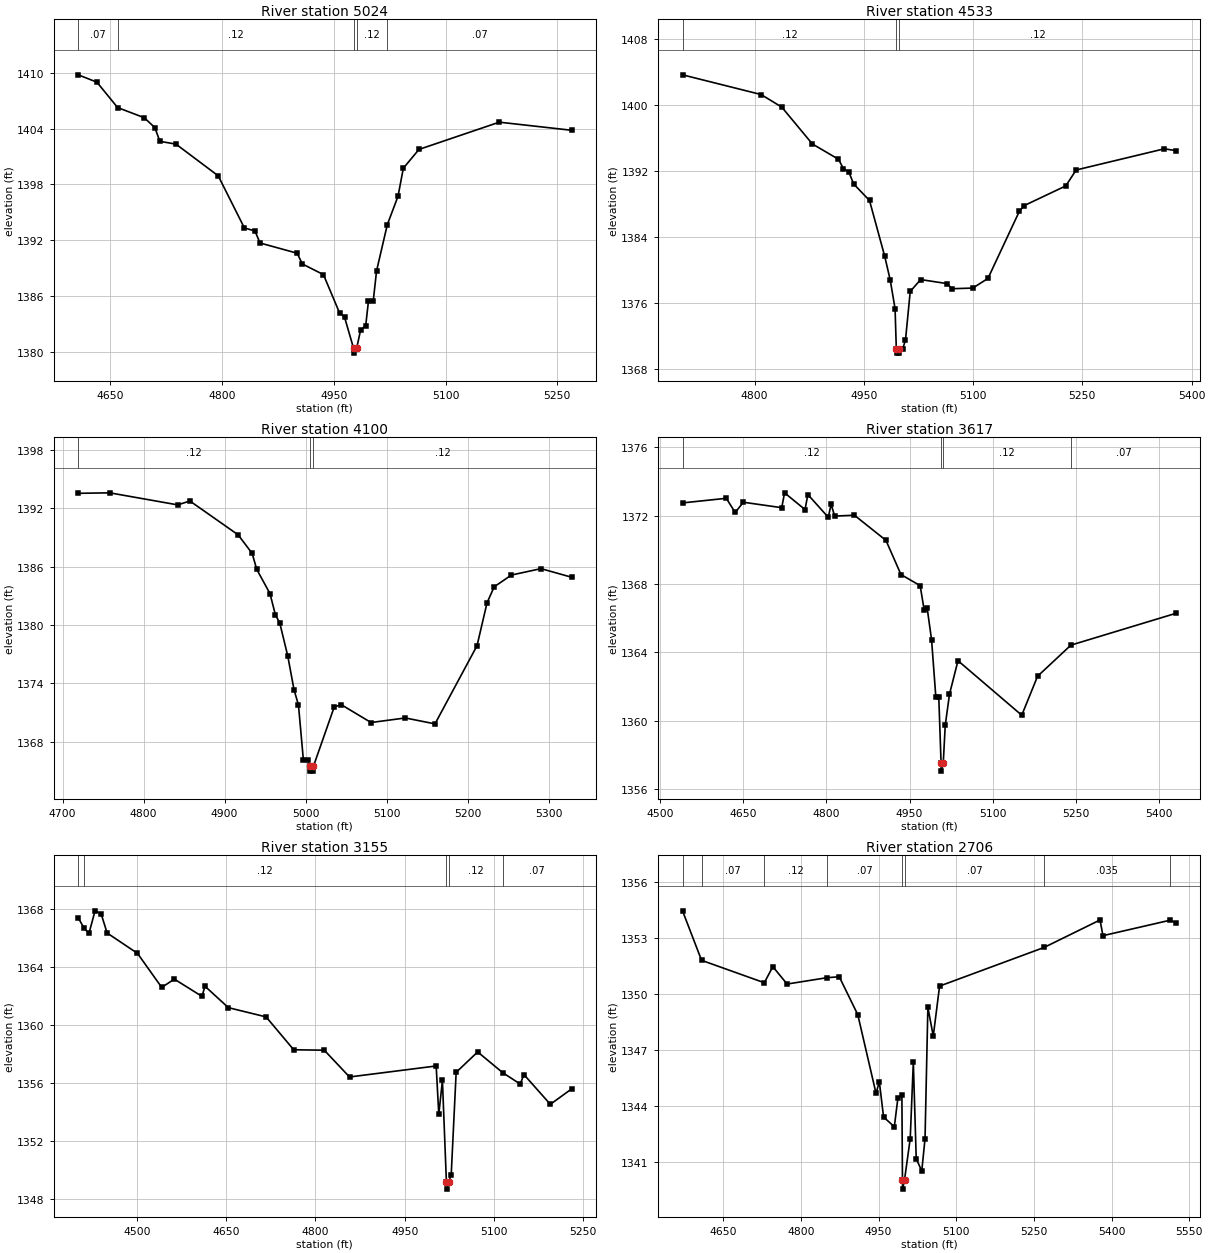
Type RM Length L Ch R = 1 ,5024    ,491,491,491
BEGIN DESCRIPTION:
Stream0193_DS 9.0
END DESCRIPTION:
XS GIS Cut Line= 3
      2139140.63      13904385.5        2138875.       13904675.
      2138723.93      13904897.7
#Sta/Elev= 30
  4607.1 1409.79  4632.2    1409    4660 1406.27  4695.7 1405.18  4709.9 1404.12
  4716.7 1402.64  4738.3 1402.34    4795 1398.93  4830.1 1393.33  4844.3    1393
  4851.1 1391.71    4901 1390.61  4907.8 1389.46  4936.2 1388.31  4957.8  1384.2
  4964.5 1383.74  4976.7 1380.37    4977 1379.87  4980.7 1380.37  4986.1 1382.36
  4992.9 1382.81  4996.6 1385.46    5003 1385.46  5007.5 1388.72  5021.9 1393.68
  5036.3 1396.74  5043.4 1399.75  5064.4 1401.77  5172.2  1404.7  5269.1 1403.83
#Mann= 5 ,-1 , 0
  4607.1     .07       0    4660     .12       0  4976.7     .05       0
  4980.7     .12       0  5021.9     .07       0
Bank Sta=4976.7,4980.7
XS Rating Curve= 0 ,0
Exp/Cntr=0.3,0.1

Type RM Length L Ch R = 1 ,4533    ,433,433,433
BEGIN DESCRIPTION:
Stream0193_DS 8.0
END DESCRIPTION:
XS GIS Cut Line= 3
      2138997.38     13904025.28        2138775.       13904225.
      2138532.97     13904515.74
#Sta/Elev= 30
  4701.1 1403.67    4809 1401.28  4837.4 1399.75  4879.3 1395.29  4915.2 1393.43
  4921.9 1392.31  4929.4 1391.89  4936.1 1390.43  4957.8 1388.43  4978.7 1381.66
  4986.2  1378.8  4992.9 1375.31  4994.6 1370.42  4994.9 1369.92  4998.4 1369.92
  4998.6 1370.42  5003.3 1370.42  5007.2 1371.51  5013.7  1377.4    5028 1378.84
  5064.4 1378.35  5070.9 1377.73  5099.6 1377.81  5120.4 1378.98  5163.4  1387.1
  5169.9  1387.8  5227.2  1390.2  5241.5 1392.13  5362.6  1394.7  5378.3 1394.48
#Mann= 3 ,-1 , 0
  4701.1     .12       0  4994.6     .05       0  4998.6     .12       0
Bank Sta=4994.6,4998.6
XS Rating Curve= 0 ,0
Exp/Cntr=0.3,0.1

Type RM Length L Ch R = 1 ,4100    ,483,483,483
BEGIN DESCRIPTION:
Stream0193_DS 7.0
END DESCRIPTION:
XS GIS Cut Line= 3
      2138780.39     13903808.27        2138525.       13903925.
      2138246.53     13904099.06
#Sta/Elev= 30
  4719.2 1393.54  4758.1 1393.59  4842.1 1392.35  4857.1 1392.75  4916.7 1389.27
    4934 1387.36  4939.7 1385.71    4956 1383.23  4962.7 1381.05  4968.2 1380.17
    4978  1376.8  4985.7 1373.34  4991.2 1371.76  4997.3 1366.09  5002.9 1366.09
  5005.7 1365.46  5005.9 1364.96  5009.4 1364.96  5009.7 1365.46  5035.4 1371.57
  5044.2 1371.79  5080.8 1369.96  5123.2 1370.43  5159.8 1369.82  5211.7 1377.86
  5224.1 1382.28  5232.9 1383.92  5254.1 1385.13  5290.7 1385.79  5328.4 1384.91
#Mann= 3 ,-1 , 0
  4719.2     .12       0  5005.7     .05       0  5009.7     .12       0
Bank Sta=5005.7,5009.7
XS Rating Curve= 0 ,0
Exp/Cntr=0.3,0.1

Type RM Length L Ch R = 1 ,3617    ,462,462,462
BEGIN DESCRIPTION:
Stream0193_DS 6.0
END DESCRIPTION:
XS GIS Cut Line= 3
      2138771.68     13903417.65        2138325.       13903525.
      2137933.98     13903704.12
#Sta/Elev= 30
  4540.6 1372.74  4619.5 1373.01  4635.6 1372.18  4650.3 1372.78  4719.5 1372.46
  4724.6 1373.33  4761.5 1372.35  4766.6 1373.23  4803.4  1371.9  4808.6 1372.66
  4814.9 1371.97  4850.5 1372.02  4907.4 1370.55  4934.5 1368.55  4969.1  1367.9
  4976.4 1366.46  4981.6 1366.62  4989.7 1364.73  4997.4 1361.37  5002.7 1361.37
  5006.8 1357.55    5007 1357.05  5010.8 1357.55  5014.3 1359.72    5022 1361.55
  5037.3 1363.51  5152.3 1360.32  5180.8  1362.6  5240.9 1364.42  5430.1 1366.28
#Mann= 4 ,-1 , 0
  4540.6     .12       0  5006.8     .05       0  5010.8     .12       0
  5240.9     .07       0
Bank Sta=5006.8,5010.8
XS Rating Curve= 0 ,0
Exp/Cntr=0.3,0.1

Type RM Length L Ch R = 1 ,3155    ,449,449,449
BEGIN DESCRIPTION:
Stream0193_DS 5.0
END DESCRIPTION:
XS GIS Cut Line= 3
      2138862.79     13903009.67        2138275.       13903125.
      2138085.95     13903257.04
#Sta/Elev= 30
    4401  1367.4  4411.2 1366.66  4419.1 1366.32  4429.3 1367.88  4439.5 1367.68
  4449.6 1366.35  4500.7 1364.94  4541.4 1362.59  4562.7 1363.16  4609.1 1361.97
  4614.2 1362.67  4653.5 1361.19    4717 1360.55  4763.4 1358.28  4814.8 1358.25
  4857.3  1356.4    5003 1357.16  5007.4 1353.81  5013.5 1356.16  5020.2 1349.15
  5020.5 1348.65  5024.2 1349.15  5028.3 1349.66  5036.6 1356.72  5072.8 1358.13
  5115.1 1356.69  5144.4 1355.91  5150.5 1356.57    5195 1354.51  5230.6 1355.57
#Mann= 5 ,-1 , 0
    4401     .07       0  4411.2     .12       0  5020.2     .05       0
  5024.2     .12       0  5115.1     .07       0
Bank Sta=5020.2,5024.2
XS Rating Curve= 0 ,0
Exp/Cntr=0.3,0.1

Type RM Length L Ch R = 1 ,2706    ,409,409,409
BEGIN DESCRIPTION:
Stream0193_DS 4.0
END DESCRIPTION:
XS GIS Cut Line= 3
       2138528.6      13902384.7      2138267.71       13902725.
      2138038.19     13903196.28
#Sta/Elev= 30
  4571.2 1354.47    4608 1351.82  4729.2 1350.62  4745.7 1351.48  4773.2 1350.55
  4850.3 1350.89    4874 1350.94  4909.8 1348.91  4945.1 1344.69  4951.4 1345.33
  4959.6 1343.43  4980.4 1342.91  4987.4 1344.47    4995 1344.59  4996.1 1340.07
  4996.4 1339.57  5000.1 1340.07  5011.1 1342.27  5017.1 1346.37  5022.7  1341.2
  5033.4 1340.54  5039.7 1342.27  5045.2 1349.31  5055.6 1347.76  5067.8 1350.44
  5269.8 1352.51  5377.8 1353.98  5383.4 1353.14  5513.6 1353.97  5524.2 1353.82
#Mann= 8 ,-1 , 0
  4571.2     .12       0    4608     .07       0  4729.2     .12       0
  4850.3     .07       0  4996.1     .05       0  5000.1     .07       0
  5269.8    .035       0  5513.6     .07       0
Bank Sta=4996.1,5000.1
XS Rating Curve= 0 ,0
Exp/Cntr=0.3,0.1

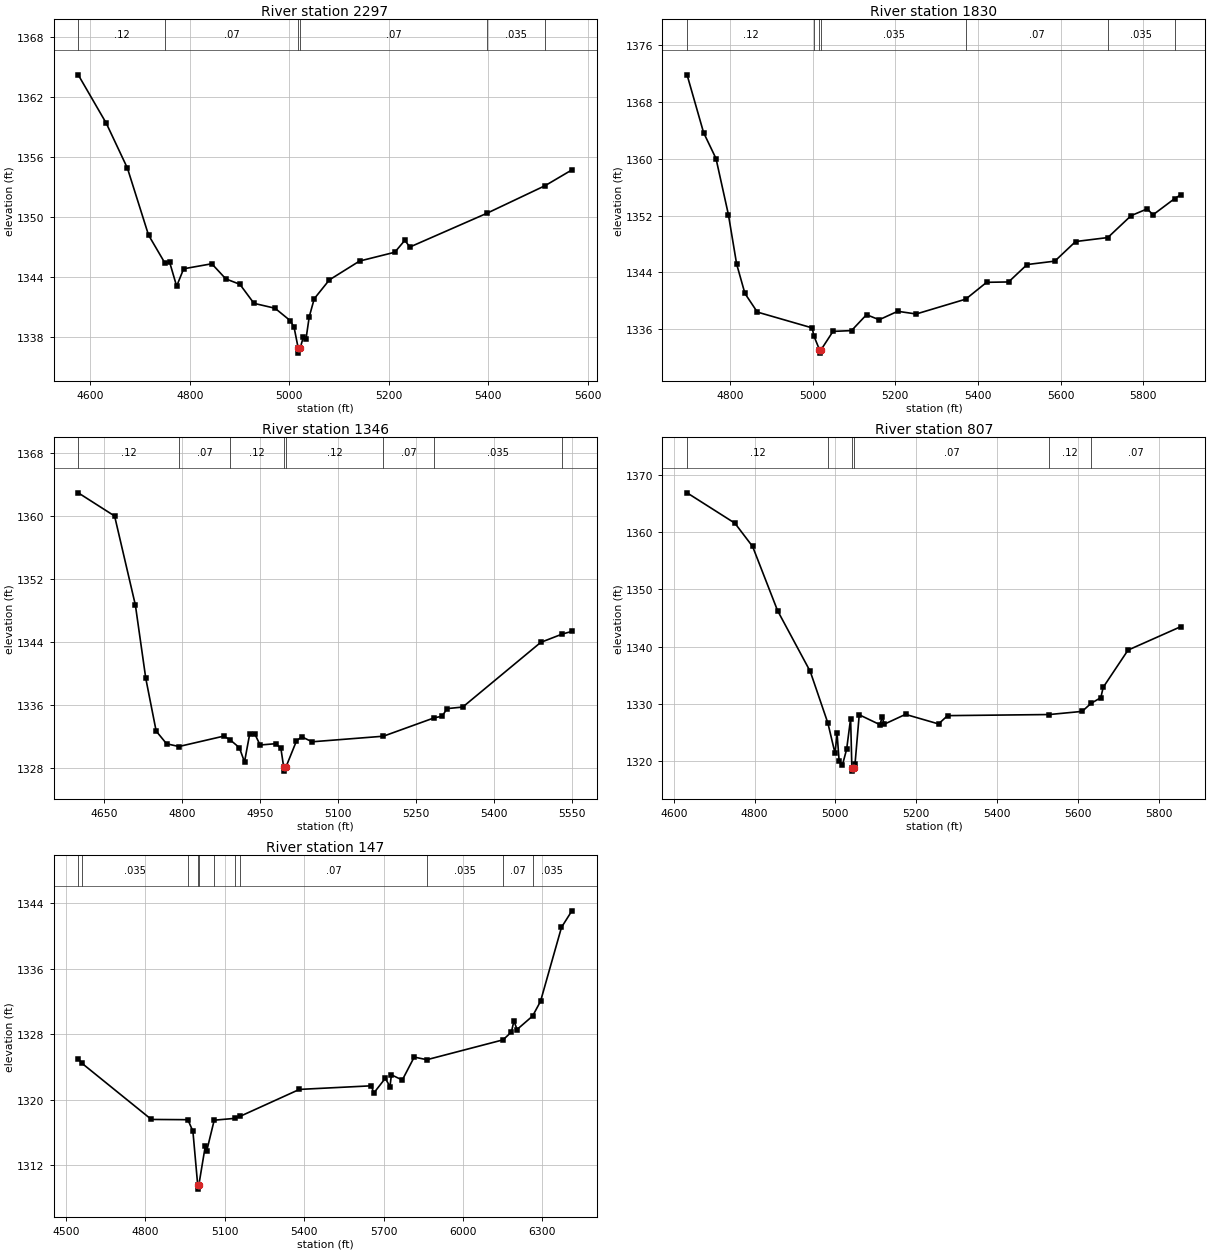
Type RM Length L Ch R = 1 ,2297    ,467,467,467
BEGIN DESCRIPTION:
Stream0193_DS 3.0
END DESCRIPTION:
XS GIS Cut Line= 3
      2138174.97     13902375.03        2137875.       13902675.
      2137962.58     13903237.09
#Sta/Elev= 30
  4575.4  1364.2  4631.9 1359.36  4674.4 1354.88  4716.8 1348.21  4749.9  1345.4
  4759.2 1345.51  4773.4  1343.1  4787.5 1344.84  4844.1 1345.34  4872.3 1343.83
  4900.6 1343.29  4928.9 1341.39  4971.3  1340.9  5002.2 1339.65  5009.7 1338.98
  5017.9 1336.92  5018.1 1336.42  5021.9 1336.92  5028.5 1338.07  5033.6 1337.83
  5040.1 1340.04  5050.2 1341.85  5080.6 1343.73  5141.3 1345.61  5212.2 1346.49
  5232.4 1347.68  5242.5 1347.01  5397.5 1350.38  5514.8 1353.14  5568.5 1354.71
#Mann= 6 ,-1 , 0
  4575.4     .12       0  4749.9     .07       0  5017.9     .05       0
  5021.9     .07       0  5397.5    .035       0  5514.8     .07       0
Bank Sta=5017.9,5021.9
XS Rating Curve= 0 ,0
Exp/Cntr=0.3,0.1

Type RM Length L Ch R = 1 ,1830    ,484,484,484
BEGIN DESCRIPTION:
Stream0193_DS 2.0
END DESCRIPTION:
XS GIS Cut Line= 3
        2137475.     13902174.97        2137475.       13902475.
      2137875.02     13903275.04
#Sta/Elev= 30
  4696.2 1371.81  4736.2 1363.67  4766.2 1360.03  4796.2 1352.14  4816.2 1345.16
  4836.2 1341.03  4866.2 1338.41    4999 1336.18  5002.9 1335.07  5016.5 1333.13
  5016.8 1332.63  5020.7 1333.13  5049.3 1335.69  5094.1  1335.8  5130.4 1338.04
  5161.1 1337.33  5205.9 1338.52  5250.6 1338.14  5370.5 1340.23  5421.1  1342.6
  5474.2 1342.65  5518.9  1345.1    5586 1345.58  5636.3 1348.34  5714.3  1348.9
  5770.5 1351.98  5809.6 1352.94  5823.6  1352.1  5876.1 1354.39  5890.7 1354.92
#Mann= 7 ,-1 , 0
  4696.2     .12       0  5002.9    .035       0  5016.5     .05       0
  5020.7    .035       0  5370.5     .07       0  5714.3    .035       0
  5876.1     .07       0
Bank Sta=5016.5,5020.7
XS Rating Curve= 0 ,0
Exp/Cntr=0.3,0.1

Type RM Length L Ch R = 1 ,1346    ,539,539,539
BEGIN DESCRIPTION:
Stream0193_DS 1.0
END DESCRIPTION:
XS GIS Cut Line= 3
        2137025.     13902175.01        2137025.       13902575.
        2137025.     13903125.01
#Sta/Elev= 30
  4599.5 1362.98  4669.5 1360.03  4709.5  1348.7  4729.5 1339.38  4749.5 1332.68
  4769.5 1331.07  4793.3 1330.72  4879.5 1332.04  4891.6 1331.58  4909.5 1330.58
  4919.5 1328.76  4929.5 1332.33  4939.5 1332.29  4949.5 1330.91  4979.5 1331.08
  4989.5 1330.49  4994.9 1328.09  4995.1 1327.59  4999.1 1328.09  5019.5 1331.43
  5029.5 1331.96  5049.5 1331.32  5186.7 1332.03  5285.1 1334.38  5299.5 1334.56
  5309.5 1335.54  5339.5 1335.74  5489.5 1343.96  5530.9 1345.02  5549.5 1345.36
#Mann= 8 ,-1 , 0
  4599.5     .12       0  4793.3     .07       0  4891.6     .12       0
  4994.9     .05       0  4999.1     .12       0  5186.7     .07       0
  5285.1    .035       0  5530.9     .07       0
Bank Sta=4994.9,4999.1
XS Rating Curve= 0 ,0
Exp/Cntr=0.3,0.1

Type RM Length L Ch R = 1 ,807     ,660,660,660
BEGIN DESCRIPTION:
Stream0193_DS 0.1
END DESCRIPTION:
XS GIS Cut Line= 3
      2137032.77     13902097.12      2136698.27     13902248.36
        2136935.     13903069.31
#Sta/Elev= 30
  4632.9 1366.84  4751.2 1361.54  4795.1 1357.47  4856.9 1346.26  4937.7 1335.65
  4981.4 1326.62  4999.1 1321.34    5004 1324.93  5009.2 1319.99  5017.3 1319.33
  5027.7 1322.05  5037.6 1327.43  5040.7 1318.75    5041 1318.25    5045 1318.75
  5048.5 1319.52  5058.9 1328.09  5110.1 1326.36  5115.4 1327.63  5121.4 1326.46
  5173.4 1328.16  5255.2 1326.49  5277.5 1327.94  5529.1 1328.13  5610.5 1328.68
  5632.4 1330.08  5656.6 1331.07  5662.6 1332.89    5724 1339.38  5854.4 1343.47
#Mann= 6 ,-1 , 0
  4632.9     .12       0  4981.4     .07       0  5040.7     .05       0
    5045     .07       0  5529.1     .12       0  5632.4     .07       0
Bank Sta=5040.7,5045
XS Rating Curve= 0 ,0
Exp/Cntr=0.3,0.1

Type RM Length L Ch R = 1 ,147     ,0,0,0
BEGIN DESCRIPTION:
Stream0193_DS 0.0
END DESCRIPTION:
XS GIS Cut Line= 5
       2136590.7     13901459.68      2136300.77     13901757.51
       2136263.4     13901983.61      2136575.09      13902687.1
      2136811.79     13903071.51
#Sta/Elev= 30
  4546.2 1325.01    4560 1324.46  4822.7 1317.61  4960.5 1317.58  4979.6 1316.18
  4997.7 1309.62  4997.9 1309.12    5002 1309.62  5026.5 1314.38  5031.6 1313.75
  5060.1 1317.52  5137.5 1317.74  5159.3 1318.01    5382 1321.27  5654.5 1321.71
  5662.8 1320.81  5706.6 1322.62  5724.4 1321.62  5729.8 1323.05  5770.9 1322.41
    5816 1325.21  5863.9 1324.89  6151.7 1327.31  6183.3 1328.26  6192.8 1329.62
  6204.6 1328.57  6263.4 1330.21  6293.4 1332.01  6372.6 1341.02  6411.9 1343.03
#Mann= 11 ,-1 , 0
  4546.2     .07       0    4560    .035       0  4960.5     .12       0
  4997.7     .05       0    5002     .12       0  5060.1     .07       0
  5137.5    .035       0  5159.3     .07       0  5863.9    .035       0
  6151.7     .07       0  6263.4    .035       0
Bank Sta=4997.7,5002
XS Rating Curve= 0 ,0
Exp/Cntr=0.3,0.1

Chan Stop Cuts=-1
Use User Specified Reach Order=0
Composite Channel Slope=5