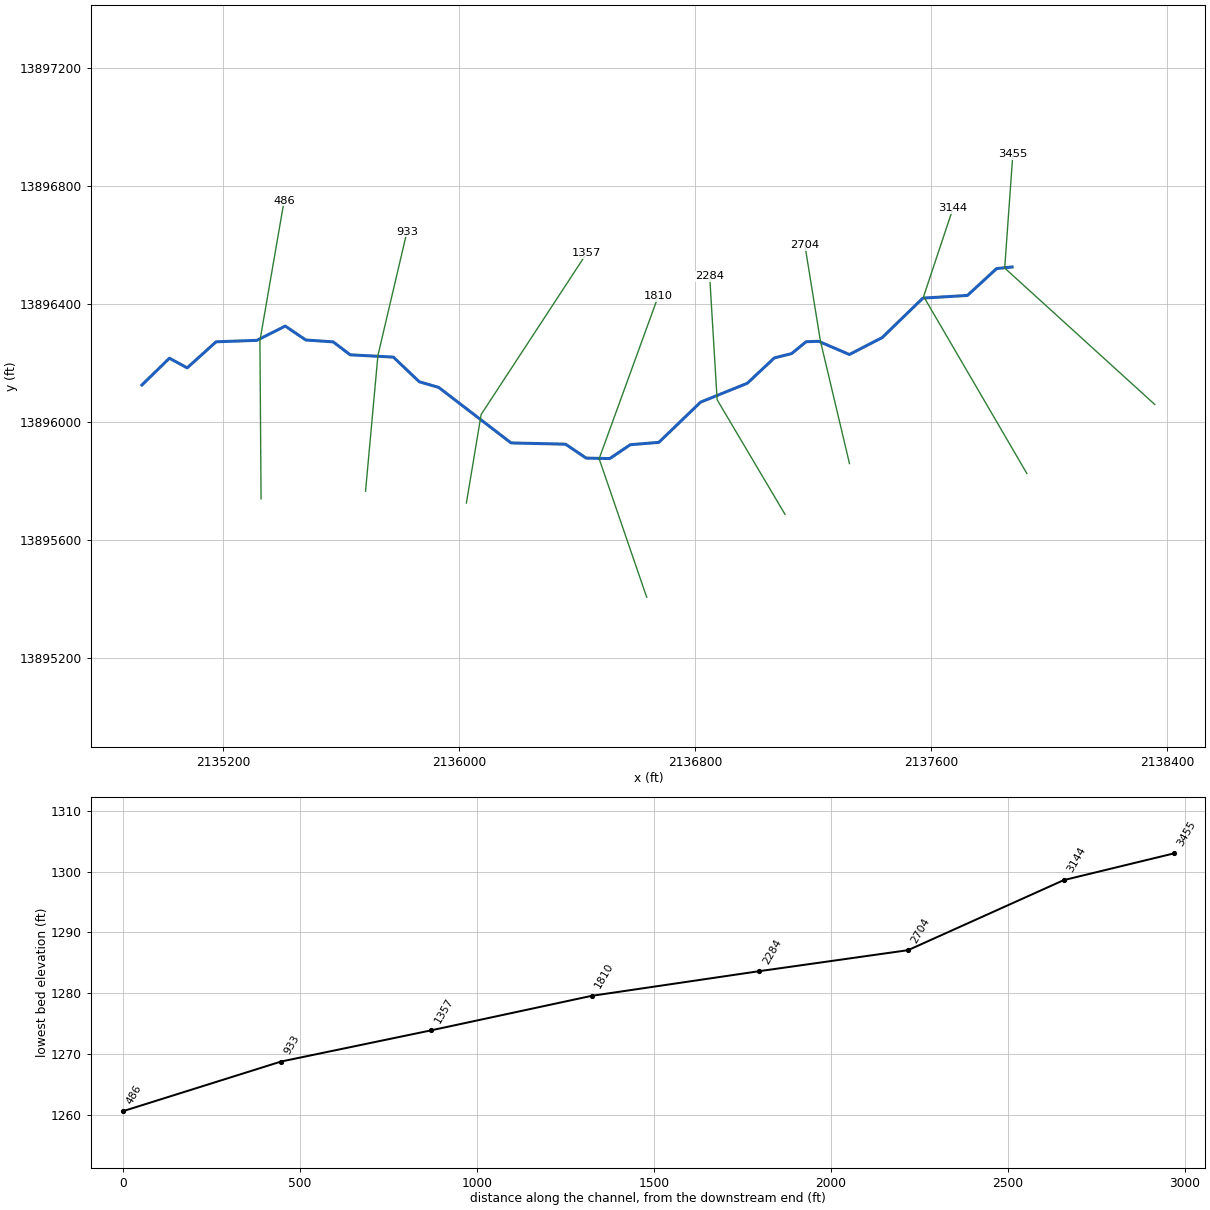
--- Stream0194_DS.prj (project) ---

Proj Title=Stream0194_DS Base Level Engineering
Current Plan=p01
Default Exp/Contr=0.3,0.1
English Units
Geom File=g01
Flow File=f01
Plan File=p01
BEGIN DESCRIPTION:
Stream0194_DS
END DESCRIPTION:

--- Stream0194_DS.p01 (plan) ---

Plan Title=Multiple Run
Short Identifier=Multiple
Geom File=g01
Flow File=f01
Subcritical Flow
K Sum by GR= 0
Std Step Tol= 0.01
Critical Tol= 0.01
Num of Std Step Trials= 20
Max Error Tol= 0.3
Flow Tol Ratio= 0.001
Split Flow NTrial= 30
Split Flow Tol= 0.02
Split Flow Ratio= 0.02
Log Output Level= 0
Friction Slope Method= 1
Unsteady Friction Slope Method= 2
Unsteady Bridges Friction Slope Method= 1
Parabolic Critical Depth
Global Vel Dist=  1 , 1 , 1
Global Log Level= 0
CheckData=True
Encroach Param= -1, 0, 0, 0
BEGIN DESCRIPTION:
Multiple Run
END DESCRIPTION:

--- Stream0194_DS.f01 (steady flow) ---

Flow Title=Multiple
Number of Profiles=7
Profile Names=10-year,25-year,50-year,1pct_min,100-year,1pct_plu,500-year
River Rch & RM= Stream0194_DS,Reach-1,3455
    1272    2173    3037    2058    4105    8191    7417
Boundary for River Rch & Prof#=Stream0194_DS,Reach-1,1
Up Type=0
Dn Type=3
Dn Slope=0.005
Boundary for River Rch & Prof#=Stream0194_DS,Reach-1,2
Up Type=0
Dn Type=3
Dn Slope=0.005
Boundary for River Rch & Prof#=Stream0194_DS,Reach-1,3
Up Type=0
Dn Type=3
Dn Slope=0.005
Boundary for River Rch & Prof#=Stream0194_DS,Reach-1,4
Up Type=0
Dn Type=3
Dn Slope=0.005
Boundary for River Rch & Prof#=Stream0194_DS,Reach-1,5
Up Type=0
Dn Type=3
Dn Slope=0.005
Boundary for River Rch & Prof#=Stream0194_DS,Reach-1,6
Up Type=0
Dn Type=3
Dn Slope=0.005
Boundary for River Rch & Prof#=Stream0194_DS,Reach-1,7
Up Type=0
Dn Type=3
Dn Slope=0.005

--- Stream0194_DS.g01 (geometry) ---

Geom Title=Existing Conditions

River Reach=Stream0194_DS,Reach-1
Reach XY= 30
      2137875.00     13896525.00      2137822.49     13896519.67
      2137723.53     13896428.54      2137572.55     13896419.53
      2137434.68     13896285.76      2137323.28     13896228.34
      2137218.89     13896273.16      2137176.72     13896271.66
      2137127.19     13896231.18      2137068.95     13896216.85
      2136977.29     13896130.85      2136818.94     13896066.86
      2136677.43     13895930.52      2136580.57     13895922.52
      2136511.03     13895875.55      2136430.98     13895877.17
      2136361.08     13895924.31      2136176.47     13895928.55
      2135931.04     13896116.82      2135865.33     13896135.80
      2135777.44     13896219.52      2135630.94     13896227.27
      2135573.40     13896271.14      2135480.56     13896277.49
      2135410.90     13896324.76      2135314.50     13896276.25
      2135176.47     13896271.43      2135078.33     13896183.01
      2135018.33     13896215.83      2134925.00     13896125.00

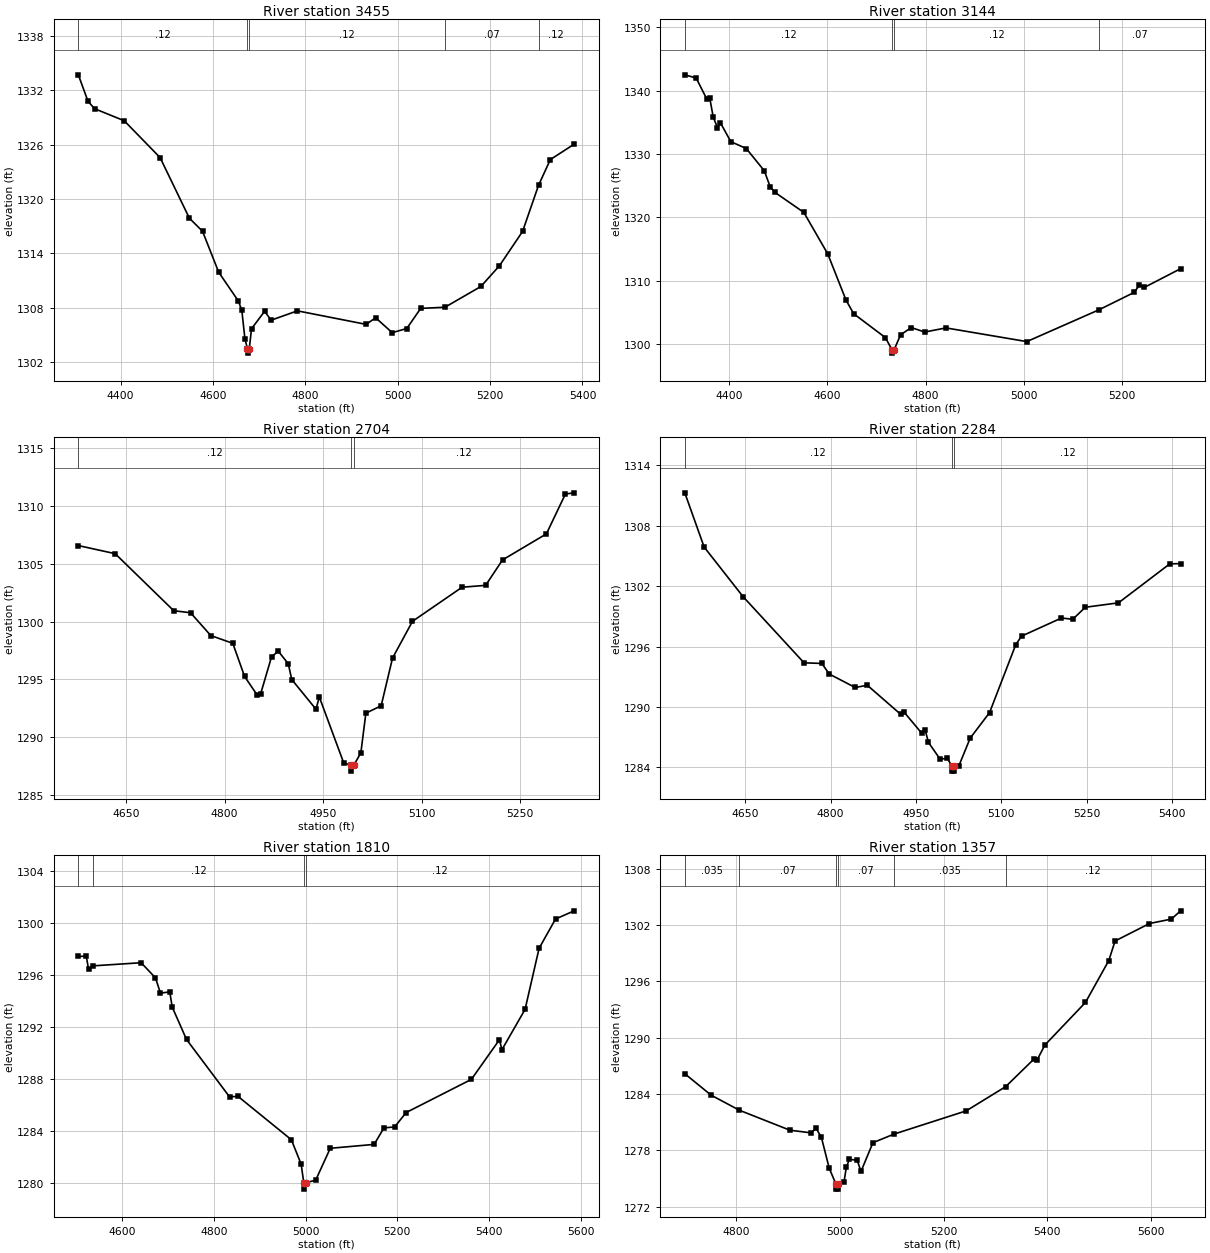
Type RM Length L Ch R = 1,3455,311,311,311
BEGIN DESCRIPTION:
Stream0194_DS 8.0
END DESCRIPTION:
XS GIS Cut Line= 3
      2138358.69     13896058.92      2137849.89     13896521.41
      2137877.46     13896906.44
#Sta/Elev= 30
  4308.4 1333.72  4329.3 1330.80  4343.5 1329.98  4407.7 1328.65  4485.4 1324.58
  4548.9 1317.88  4577.3 1316.44  4612.4 1311.91  4655.0 1308.73  4662.4 1307.70
  4669.2 1304.52  4674.6 1303.48  4674.8 1302.98  4678.6 1303.48  4683.4 1305.67
  4711.7 1307.60  4725.9 1306.62  4782.7 1307.65  4931.3 1306.16  4952.3 1306.88
  4988.1 1305.24  5019.6 1305.70  5049.7 1307.92  5102.3 1308.05  5180.0 1310.34
  5220.2 1312.63  5270.3 1316.42  5304.8 1321.51  5330.4 1324.36  5382.0 1326.06
#Mann=5,-1,0
  4308.4    0.12       0  4674.6    0.05       0  4678.6    0.12       0
  5102.3    0.07       0  5304.8    0.12       0
Bank Sta=4674.6,4678.6
Exp/Cntr=0.3,0.1

Type RM Length L Ch R = 1,3144,440,440,440
BEGIN DESCRIPTION:
Stream0194_DS 7.0
END DESCRIPTION:
XS GIS Cut Line= 3
      2137924.99     13895825.02      2137575.00     13896425.00
      2137674.99     13896724.97
#Sta/Elev= 30
  4309.3 1342.52  4332.4 1342.02  4354.4 1338.66  4360.1 1338.90  4367.2 1335.86
  4375.9 1334.18  4381.6 1334.99  4403.1 1331.97  4434.6 1330.89  4471.4 1327.37
  4483.4 1324.83  4493.3 1323.95  4552.0 1320.80  4600.8 1314.24  4638.0 1306.95
  4653.7 1304.80  4718.2 1301.04  4731.9 1299.09  4732.2 1298.59  4735.9 1299.09
  4749.2 1301.49  4771.1 1302.62  4798.4 1301.92  4841.8 1302.57  5006.5 1300.41
  5153.9 1305.44  5225.3 1308.17  5235.8 1309.29  5246.3 1308.97  5320.1 1311.92
#Mann=4,-1,0
  4309.3    0.12       0  4731.9    0.05       0  4735.9    0.12       0
  5153.9    0.07       0
Bank Sta=4731.9,4735.9
Exp/Cntr=0.3,0.1

Type RM Length L Ch R = 1,2704,420,420,420
BEGIN DESCRIPTION:
Stream0194_DS 6.0
END DESCRIPTION:
XS GIS Cut Line= 3
      2137323.68     13895858.62      2137225.00     13896275.00
      2137172.64     13896598.17
#Sta/Elev= 30
  4577.1 1306.57  4633.2 1305.87  4722.4 1300.94  4748.1 1300.76  4778.9 1298.79
  4812.4 1298.12  4830.3 1295.26  4849.5 1293.65  4854.6 1293.71  4871.4 1296.95
  4881.7 1297.44  4896.9 1296.35  4902.2 1294.99  4939.1 1292.42  4944.2 1293.48
  4981.3 1287.79  4992.7 1287.57  4993.0 1287.07  4996.7 1287.57  5007.5 1288.66
  5015.1 1292.08  5038.4 1292.72  5055.7 1296.84  5086.1 1300.02  5161.7 1302.97
  5197.5 1303.13  5223.3 1305.33  5290.1 1307.58  5319.1 1311.03  5332.4 1311.13
#Mann=3,-1,0
  4577.1    0.12       0  4992.7    0.05       0  4996.7    0.12       0
Bank Sta=4992.7,4996.7
Exp/Cntr=0.3,0.1

Type RM Length L Ch R = 1,2284,474,474,474
BEGIN DESCRIPTION:
Stream0194_DS 5.0
END DESCRIPTION:
XS GIS Cut Line= 3
      2137104.95     13895686.68      2136875.00     13896075.00
      2136849.73     13896494.04
#Sta/Elev= 30
  4543.8 1311.27  4577.8 1305.88  4646.1 1300.96  4753.3 1294.38  4784.6 1294.32
  4797.5 1293.27  4843.1 1291.93  4864.5 1292.15  4923.0 1289.27  4928.8 1289.50
  4960.0 1287.39  4965.9 1287.74  4971.9 1286.47  4992.2 1284.82  5005.1 1284.88
  5013.1 1284.12  5013.4 1283.62  5016.9 1283.62  5017.1 1284.12  5025.2 1284.13
  5045.2 1286.90  5079.2 1289.43  5125.3 1296.19  5135.4 1297.03  5205.5 1298.83
  5225.5 1298.71  5247.4 1299.90  5305.7 1300.34  5395.8 1304.21  5414.9 1304.24
#Mann=3,-1,0
  4543.8    0.12       0  5013.1    0.05       0  5017.1    0.12       0
Bank Sta=5013.1,5017.1
Exp/Cntr=0.3,0.1

Type RM Length L Ch R = 1,1810,453,453,453
BEGIN DESCRIPTION:
Stream0194_DS 4.0
END DESCRIPTION:
XS GIS Cut Line= 3
      2136636.18     13895405.46      2136475.00     13895875.00
      2136675.01     13896425.03
#Sta/Elev= 30
  4504.4 1297.45  4521.6 1297.48  4526.9 1296.45  4537.2 1296.73  4641.4 1296.97
  4672.6 1295.81  4683.6 1294.63  4703.9 1294.73  4709.2 1293.56  4740.4 1291.07
  4834.2 1286.66  4852.8 1286.69  4969.1 1283.36  4990.5 1281.48  4996.2 1280.06
  4996.4 1279.56  5000.2 1280.06  5022.1 1280.24  5054.0 1282.70  5149.8 1283.00
  5171.1 1284.27  5194.4 1284.34  5219.6 1285.45  5361.9 1288.00  5423.1 1291.05
  5428.5 1290.28  5479.0 1293.38  5509.6 1298.08  5545.5 1300.33  5586.1 1300.96
#Mann=4,-1,0
  4504.4    0.07       0  4537.2    0.12       0  4996.2    0.05       0
  5000.2    0.12       0
Bank Sta=4996.2,5000.2
Exp/Cntr=0.3,0.1

Type RM Length L Ch R = 1,1357,424,424,424
BEGIN DESCRIPTION:
Stream0194_DS 3.0
END DESCRIPTION:
XS GIS Cut Line= 3
      2136024.99     13895724.95      2136075.00     13896025.00
      2136432.37     13896571.07
#Sta/Elev= 30
  4700.3 1286.17  4751.0 1283.89  4805.8 1282.28  4903.1 1280.16  4943.7 1279.88
  4953.8 1280.35  4963.9 1279.40  4979.1 1276.09  4992.3 1274.39  4992.6 1273.89
  4996.1 1273.89  4996.3 1274.39  5007.5 1274.62  5012.0 1276.23  5018.0 1277.07
  5033.1 1276.95  5040.3 1275.77  5063.3 1278.83  5104.3 1279.75  5243.5 1282.22
  5319.6 1284.80  5373.9 1287.72  5379.9 1287.60  5395.0 1289.21  5473.4 1293.75
  5518.4 1298.20  5530.6 1300.29  5597.0 1302.15  5639.2 1302.62  5657.1 1303.50
#Mann=6,-1,0
  4700.3   0.035       0  4805.8    0.07       0  4992.3    0.05       0
  4996.3    0.07       0  5104.3   0.035       0  5319.6    0.12       0
Bank Sta=4992.3,4996.3
Exp/Cntr=0.3,0.1

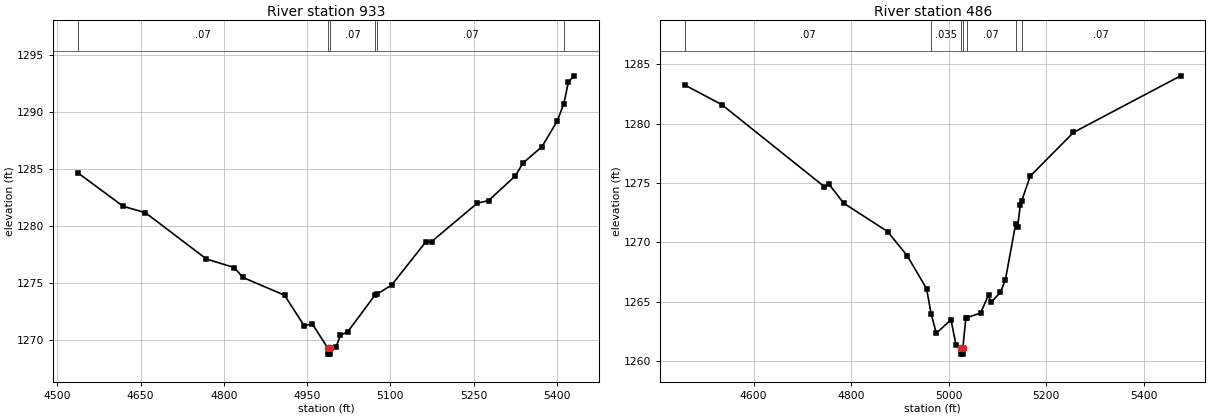
Type RM Length L Ch R = 1,933,447,447,447
BEGIN DESCRIPTION:
Stream0194_DS 2.0
END DESCRIPTION:
XS GIS Cut Line= 3
      2135683.06     13895764.83      2135725.00     13896225.00
      2135823.68     13896644.99
#Sta/Elev= 30
  4537.6 1284.62  4618.6 1281.71  4658.3 1281.16  4768.7 1277.09  4818.9 1276.34
  4834.2 1275.48  4909.3 1273.92  4944.5 1271.26  4959.5 1271.40  4987.6 1269.26
  4987.9 1268.76  4991.4 1268.76  4991.6 1269.26  5002.2 1269.38  5009.9 1270.41
  5023.4 1270.73  5072.0 1273.91  5075.7 1274.00  5102.4 1274.82  5164.0 1278.60
  5174.3 1278.62  5256.5 1281.98  5277.0 1282.21  5325.4 1284.39  5338.7 1285.49
  5373.0 1286.93  5400.3 1289.15  5412.5 1290.69  5420.8 1292.61  5431.1 1293.14
#Mann=6,-1,0
  4537.6    0.07       0  4987.6    0.05       0  4991.6    0.07       0
  5072.0   0.035       0  5075.7    0.07       0  5412.5   0.035       0
Bank Sta=4987.6,4991.6
Exp/Cntr=0.3,0.1

Type RM Length L Ch R = 1,486,0,0,0
BEGIN DESCRIPTION:
Stream0194_DS 1.0
END DESCRIPTION:
XS GIS Cut Line= 3
      2135328.89     13895738.84      2135325.00     13896275.00
      2135407.02     13896749.18
#Sta/Elev= 30
  4458.7 1283.27  4534.9 1281.61  4744.9 1274.71  4754.9 1274.90  4784.9 1273.31
  4874.9 1270.92  4914.9 1268.90  4954.9 1266.11  4964.3 1263.98  4974.9 1262.35
  5005.0 1263.49  5015.2 1261.40  5025.3 1261.09  5025.6 1260.59  5029.1 1260.59
  5029.3 1261.09  5035.5 1263.64  5037.5 1263.66  5065.9 1264.06  5082.0 1265.58
  5087.1 1264.95  5106.5 1265.80  5116.7 1266.87  5137.8 1271.58  5141.8 1271.32
  5147.1 1273.16  5150.3 1273.53  5167.4 1275.58  5256.3 1279.27  5476.1 1284.04
#Mann=7,-1,0
  4458.7    0.07       0  4964.3   0.035       0  5025.3   0.035       0
  5029.3   0.035       0  5037.5    0.07       0  5137.8   0.035       0
  5150.3    0.07       0
Bank Sta=5025.3,5029.3
Exp/Cntr=0.3,0.1

Chan Stop Cuts=-1