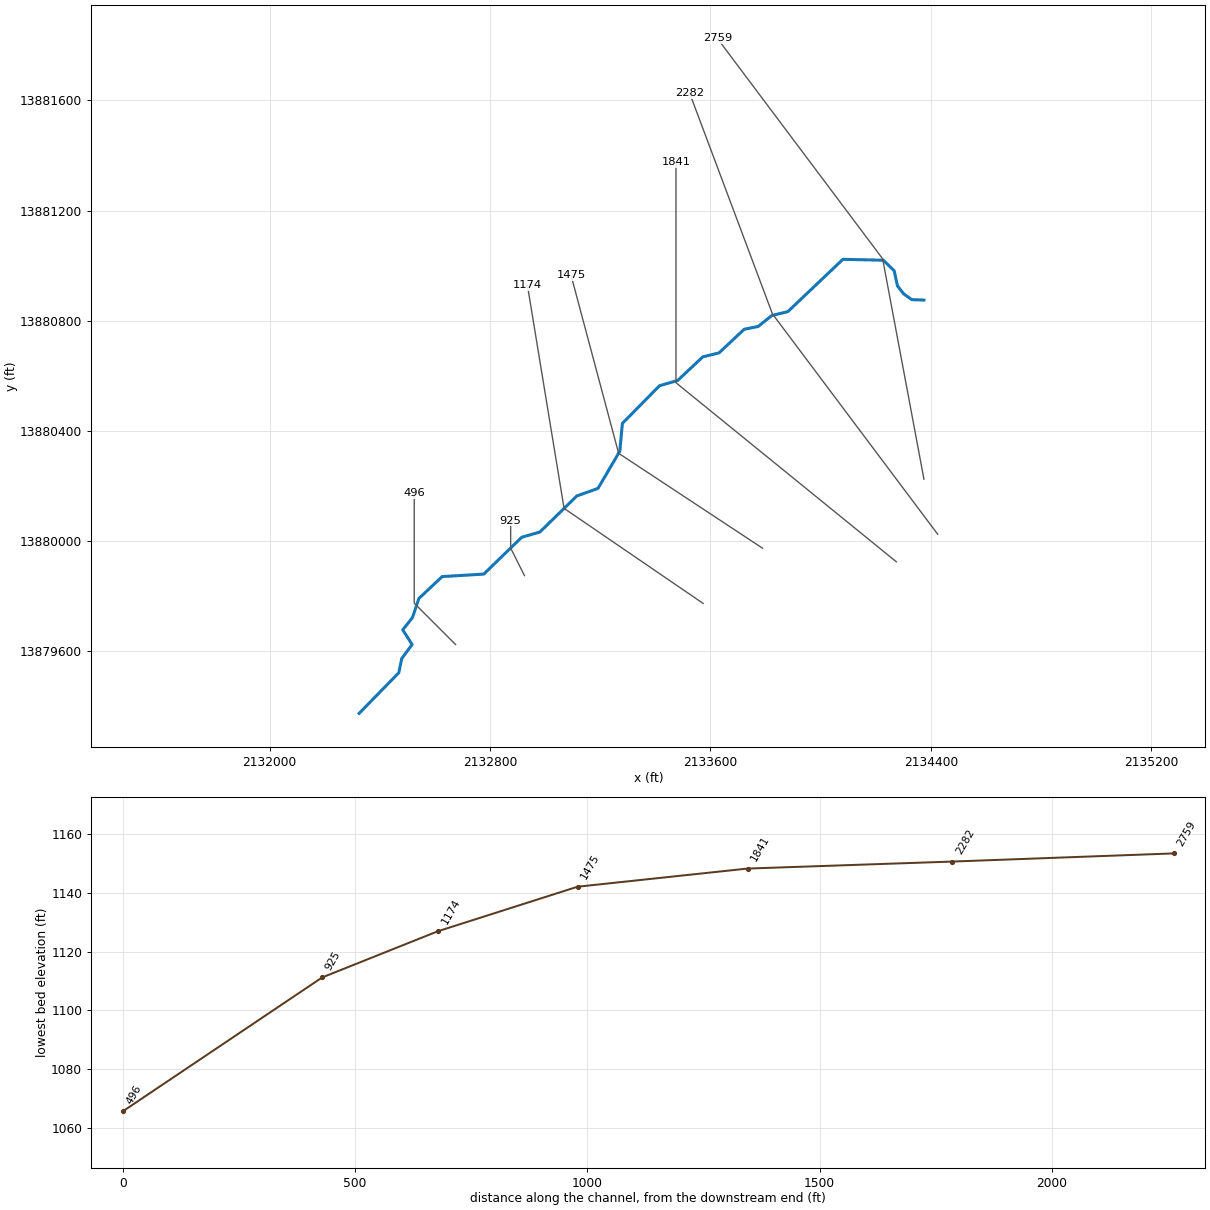
--- Stream0195_DS.prj (project) ---

Proj Title=Stream0195_DS Base Level Engineering
Current Plan=p01
Default Exp/Contr=0.3,0.1
English Units
Geom File=g01
Flow File=f01
Plan File=p01
BEGIN DESCRIPTION:
Stream0195_DS
END DESCRIPTION:

--- Stream0195_DS.p01 (plan) ---

Plan Title=Multiple Run
Short Identifier=Multiple
Geom File=g01
Flow File=f01
Subcritical Flow
K Sum by GR= 0
Std Step Tol= 0.01
Critical Tol= 0.01
Num of Std Step Trials= 20
Max Error Tol= 0.3
Flow Tol Ratio= 0.001
Split Flow NTrial= 30
Split Flow Tol= 0.02
Split Flow Ratio= 0.02
Log Output Level= 0
Friction Slope Method= 1
Unsteady Friction Slope Method= 2
Unsteady Bridges Friction Slope Method= 1
Parabolic Critical Depth
Global Vel Dist=  1 , 1 , 1
Global Log Level= 0
CheckData=True
Encroach Param= -1, 0, 0, 0
BEGIN DESCRIPTION:
Multiple Run
END DESCRIPTION:

--- Stream0195_DS.f01 (steady flow) ---

Flow Title=Multiple
Number of Profiles=7
Profile Names=10-year,25-year,50-year,1pct_min,100-year,1pct_plu,500-year
River Rch & RM= Stream0195_DS,Reach-1,2759
    1378    2354    3288    2223    4435    8849    7984
Boundary for River Rch & Prof#=Stream0195_DS,Reach-1,1
Up Type=0
Dn Type=3
Dn Slope=0.005
Boundary for River Rch & Prof#=Stream0195_DS,Reach-1,2
Up Type=0
Dn Type=3
Dn Slope=0.005
Boundary for River Rch & Prof#=Stream0195_DS,Reach-1,3
Up Type=0
Dn Type=3
Dn Slope=0.005
Boundary for River Rch & Prof#=Stream0195_DS,Reach-1,4
Up Type=0
Dn Type=3
Dn Slope=0.005
Boundary for River Rch & Prof#=Stream0195_DS,Reach-1,5
Up Type=0
Dn Type=3
Dn Slope=0.005
Boundary for River Rch & Prof#=Stream0195_DS,Reach-1,6
Up Type=0
Dn Type=3
Dn Slope=0.005
Boundary for River Rch & Prof#=Stream0195_DS,Reach-1,7
Up Type=0
Dn Type=3
Dn Slope=0.005

--- Stream0195_DS.g01 (geometry) ---

Geom Title=Existing Conditions

River Reach=Stream0195_DS,Reach-1
Reach XY= 30
      2134375.00     13880875.00      2134330.87     13880876.56
      2134301.02     13880897.83      2134278.88     13880926.50
      2134266.99     13880981.38      2134227.70     13881019.65
      2134080.86     13881022.95      2133881.06     13880833.14
      2133822.81     13880818.90      2133773.27     13880779.19
      2133722.71     13880769.15      2133631.04     13880683.18
      2133572.72     13880669.13      2133481.04     13880583.18
      2133415.32     13880564.22      2133280.52     13880427.43
      2133271.17     13880326.58      2133192.05     13880191.49
      2133115.34     13880164.21      2132981.05     13880033.16
      2132915.32     13880014.22      2132777.45     13879880.47
      2132626.46     13879871.46      2132541.62     13879791.71
      2132518.60     13879722.71      2132483.24     13879678.23
      2132517.24     13879625.08      2132479.44     13879573.35
      2132469.20     13879522.71      2132325.00     13879375.00

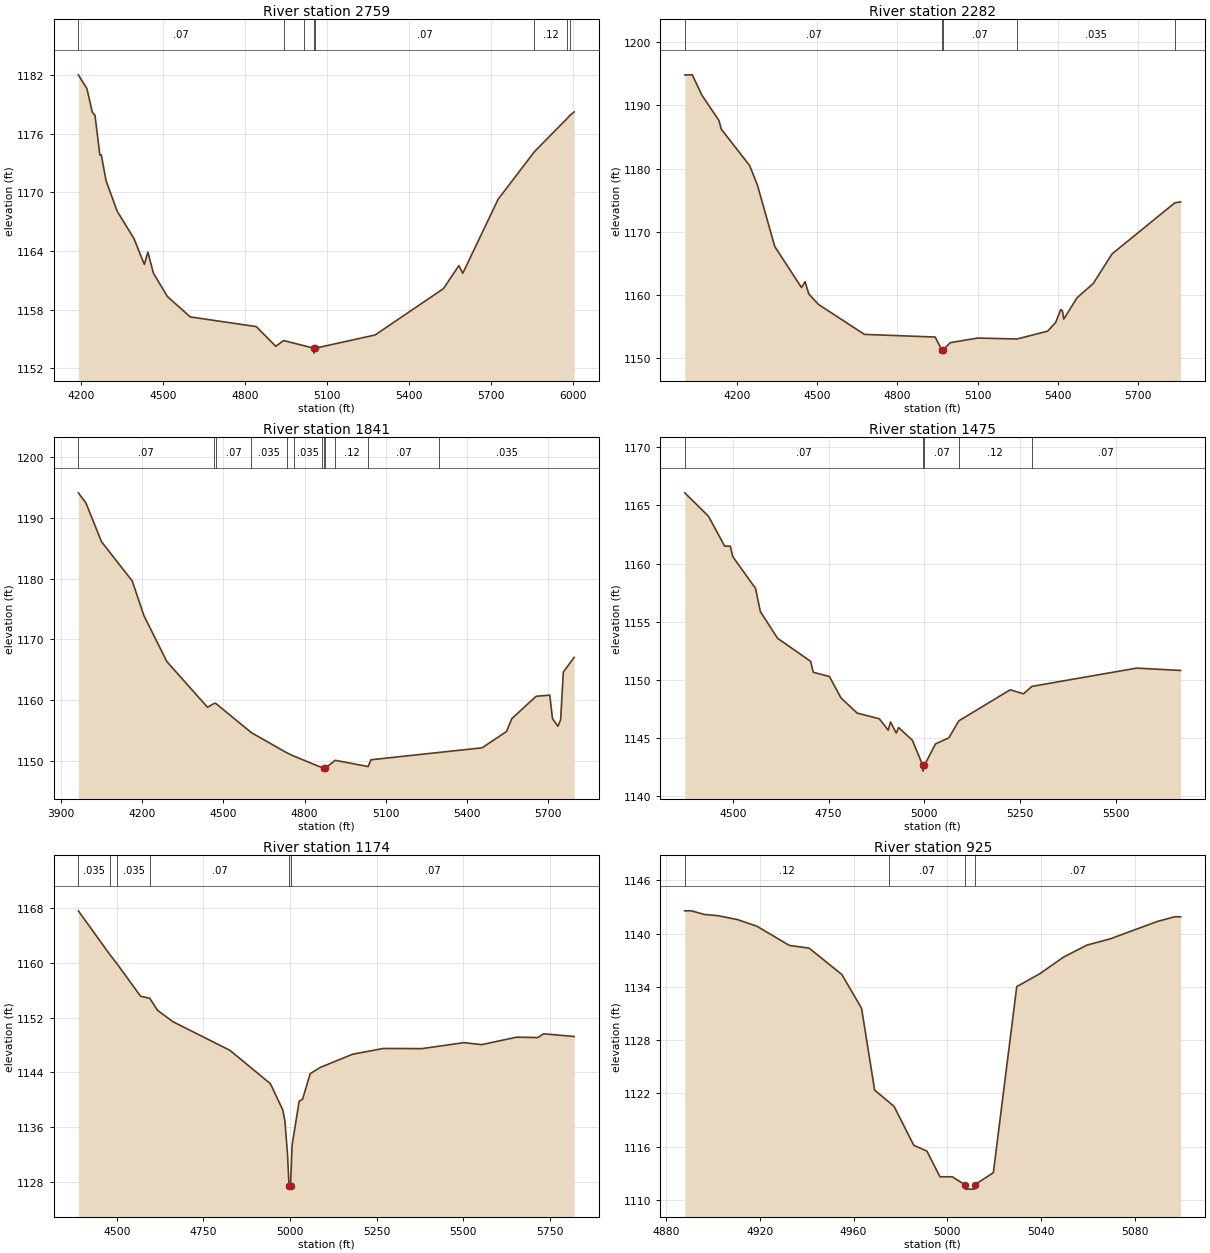
Type RM Length L Ch R = 1,2759,477,477,477
BEGIN DESCRIPTION:
Stream0195_DS 5.0
END DESCRIPTION:
XS GIS Cut Line= 3
      2134375.00     13880225.01      2134225.00     13881025.00
      2133625.02     13881824.98
#Sta/Elev= 30
  4190.6 1182.05  4222.0 1180.64  4241.5 1178.24  4251.6 1177.89  4269.4 1173.83
  4274.5 1173.85  4292.3 1171.17  4333.0 1168.06  4394.1 1165.27  4432.2 1162.62
  4444.9 1163.89  4465.3 1161.73  4516.2 1159.34  4600.1 1157.24  4841.7 1156.25
  4913.0 1154.23  4941.3 1154.82  5017.8 1154.28  5052.5 1154.03  5052.7 1153.53
  5056.6 1154.03  5276.4 1155.39  5526.4 1160.14  5582.7 1162.50  5597.2 1161.72
  5726.4 1169.30  5859.3 1174.18  5979.5 1177.60  5987.5 1177.86  6004.5 1178.25
#Mann=8,-1,0
  4190.6    0.07       0  4941.3   0.035       0  5017.8    0.07       0
  5052.5   0.035       0  5056.6    0.07       0  5859.3    0.12       0
  5979.5   0.035       0  5987.5    0.07       0
Bank Sta=5052.5,5056.6
Exp/Cntr=0.3,0.1

Type RM Length L Ch R = 1,2282,441,441,441
BEGIN DESCRIPTION:
Stream0195_DS 4.0
END DESCRIPTION:
XS GIS Cut Line= 3
      2134424.98     13880025.03      2133825.00     13880825.00
      2133524.99     13881625.03
#Sta/Elev= 30
  4004.8 1194.84  4032.9 1194.86  4068.3 1191.67  4132.9 1187.59  4141.2 1186.25
  4247.5 1180.47  4276.6 1177.36  4341.2 1167.66  4441.2 1161.14  4454.8 1162.07
  4468.3 1160.14  4504.8 1158.47  4676.6 1153.72  4941.2 1153.30  4966.3 1151.25
  4966.5 1150.75  4970.4 1151.25  4997.5 1152.41  5100.0 1153.14  5247.2 1152.99
  5361.7 1154.23  5391.9 1155.62  5410.6 1157.63  5416.8 1157.50  5422.2 1156.15
  5472.0 1159.53  5532.5 1161.79  5602.8 1166.48  5837.7 1174.58  5859.2 1174.71
#Mann=5,-1,0
  4004.8    0.07       0  4966.3    0.05       0  4970.4    0.07       0
  5247.2   0.035       0  5837.7    0.07       0
Bank Sta=4966.3,4970.4
Exp/Cntr=0.3,0.1

Type RM Length L Ch R = 1,1841,366,366,366
BEGIN DESCRIPTION:
Stream0195_DS 3.0
END DESCRIPTION:
XS GIS Cut Line= 3
      2134275.04     13879924.97      2133475.00     13880575.00
      2133475.00     13881374.98
#Sta/Elev= 30
  3964.4 1194.11  3992.4 1192.45  4049.9 1186.08  4163.4 1179.63  4206.5 1173.93
  4291.3 1166.37  4441.2 1158.87  4464.5 1159.45  4470.9 1159.53  4603.4 1154.69
  4733.6 1151.39  4762.4 1150.79  4863.8 1148.94  4872.5 1148.86  4872.8 1148.36
  4876.7 1148.86  4912.8 1150.14  5034.4 1149.11  5045.2 1150.23  5297.7 1151.44
  5455.2 1152.19  5545.2 1154.87  5565.2 1157.00  5655.2 1160.67  5705.2 1160.85
  5715.2 1157.00  5735.2 1155.74  5745.2 1156.79  5755.2 1164.65  5795.2 1167.06
#Mann=12,-1,0
  3964.4    0.07       0  4464.5   0.035       0  4470.9    0.07       0
  4603.4   0.035       0  4733.6    0.07       0  4762.4   0.035       0
  4863.8    0.07       0  4872.5    0.05       0  4876.7    0.07       0
  4912.8    0.12       0  5034.4    0.07       0  5297.7   0.035       0
Bank Sta=4872.5,4876.7
Exp/Cntr=0.3,0.1

Type RM Length L Ch R = 1,1475,301,301,301
BEGIN DESCRIPTION:
Stream0195_DS 2.2
END DESCRIPTION:
XS GIS Cut Line= 3
      2133789.38     13879974.39      2133266.85     13880318.94
      2133093.88     13880966.13
#Sta/Elev= 30
  4374.1 1166.08  4436.0 1164.07  4478.1 1161.51  4493.2 1161.49  4499.2 1160.61
  4559.0 1157.87  4571.5 1155.88  4616.7 1153.58  4702.8 1151.61  4710.0 1150.66
  4752.1 1150.30  4782.3 1148.46  4824.4 1147.16  4882.4 1146.67  4905.7 1145.69
  4911.7 1146.39  4926.8 1145.44  4932.8 1145.92  4968.9 1144.82  4996.0 1142.67
  4996.3 1142.17  5000.2 1142.67  5029.3 1144.51  5064.2 1145.03  5090.3 1146.49
  5224.5 1149.16  5259.4 1148.81  5281.2 1149.45  5554.9 1151.02  5669.9 1150.82
#Mann=5,-1,0
  4374.1    0.07       0  4996.0    0.05       0  5000.2    0.07       0
  5090.3    0.12       0  5281.2    0.07       0
Bank Sta=4996,5000.2
Exp/Cntr=0.3,0.1

Type RM Length L Ch R = 1,1174,249,249,249
BEGIN DESCRIPTION:
Stream0195_DS 2.1
END DESCRIPTION:
XS GIS Cut Line= 3
      2133573.53     13879774.11      2133068.87     13880119.09
      2132935.85     13880928.63
#Sta/Elev= 30
  4388.7 1167.59  4479.1 1161.25  4501.3 1159.80  4568.6 1155.12  4594.9 1154.83
  4617.5 1153.06  4662.2 1151.40  4826.7 1147.22  4943.3 1142.36  4979.2 1138.51
  4985.2 1136.91  4992.6 1132.20  4997.2 1127.47  4997.5 1126.97  5001.2 1126.97
  5001.5 1127.47  5006.0 1133.41  5026.3 1139.79  5036.4 1140.12  5058.2 1143.82
  5087.1 1144.73  5180.7 1146.66  5269.5 1147.50  5381.0 1147.48  5502.6 1148.35
  5553.2 1148.06  5654.6 1149.15  5715.4 1149.09  5731.8 1149.64  5820.4 1149.25
#Mann=6,-1,0
  4388.7   0.035       0  4479.1    0.07       0  4501.3   0.035       0
  4594.9    0.07       0  4997.2    0.05       0  5001.5    0.07       0
Bank Sta=4997.2,5001.5
Exp/Cntr=0.3,0.1

Type RM Length L Ch R = 1,925,429,429,429
BEGIN DESCRIPTION:
Stream0195_DS 2.0
END DESCRIPTION:
XS GIS Cut Line= 3
      2132925.00     13879875.01      2132875.00     13879975.00
      2132875.00     13880075.00
#Sta/Elev= 30
  4887.9 1142.57  4890.7 1142.57  4896.3 1142.16  4901.9 1142.03  4910.3 1141.59
  4918.6 1140.85  4932.6 1138.67  4941.0 1138.37  4955.0 1135.39  4963.4 1131.60
  4969.0 1122.37  4975.1 1121.03  4977.3 1120.54  4985.7 1116.16  4991.3 1115.51
  4996.9 1112.61  5002.2 1112.61  5007.5 1111.72  5007.8 1111.22  5011.6 1111.22
  5011.8 1111.72  5019.7 1113.07  5029.7 1134.03  5039.7 1135.51  5049.7 1137.36
  5059.7 1138.71  5069.7 1139.42  5089.7 1141.37  5097.2 1141.90  5099.7 1141.90
#Mann=4,-1,0
  4887.9    0.12       0  4975.1    0.07       0  5007.5    0.05       0
  5011.8    0.07       0
Bank Sta=5007.5,5011.8
Exp/Cntr=0.3,0.1

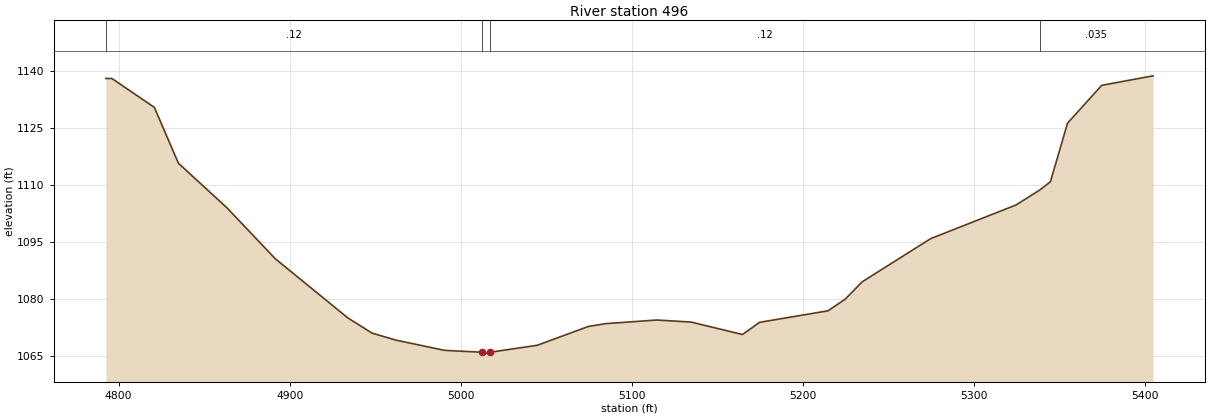
Type RM Length L Ch R = 1,496,0,0,0
BEGIN DESCRIPTION:
Stream0195_DS 1.0
END DESCRIPTION:
XS GIS Cut Line= 3
      2132675.00     13879625.00      2132525.00     13879775.00
      2132525.00     13880174.97
#Sta/Elev= 30
  4792.6 1138.05  4796.1 1138.05  4820.9 1130.47  4835.0 1115.77  4863.3 1104.08
  4891.6 1090.66  4934.0 1075.11  4948.2 1071.10  4962.3 1069.24  4990.6 1066.57
  5012.2 1066.08  5012.6 1065.58  5017.2 1066.08  5044.7 1067.90  5074.7 1072.86
  5084.7 1073.59  5114.7 1074.55  5134.7 1074.00  5164.7 1070.74  5174.7 1073.94
  5214.7 1076.97  5224.7 1080.01  5234.7 1084.60  5274.7 1095.94  5324.7 1104.81
  5338.5 1108.74  5344.7 1110.90  5354.7 1126.30  5374.7 1136.25  5404.7 1138.75
#Mann=4,-1,0
  4792.6    0.12       0  5012.2    0.05       0  5017.2    0.12       0
  5338.5   0.035       0
Bank Sta=5012.2,5017.2
Exp/Cntr=0.3,0.1

Chan Stop Cuts=-1