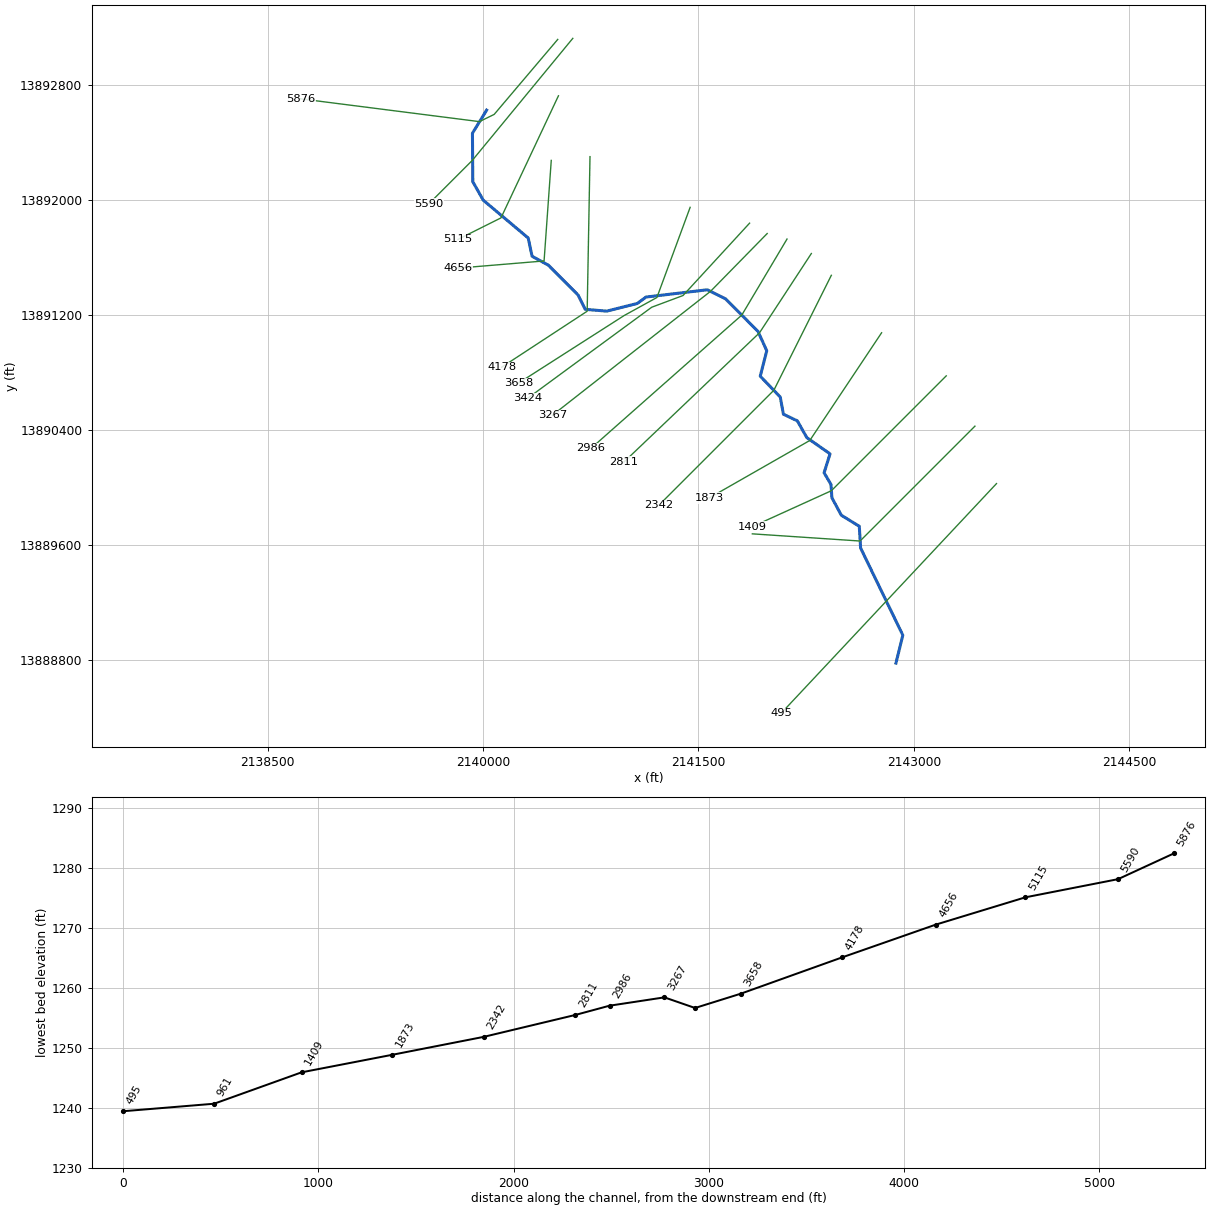
--- Stream0196_DS.prj (project) ---

Proj Title=Stream0196_DS Base Level Engineering
Current Plan=p01
Default Exp/Contr=0.3,0.1
English Units
Geom File=g01
Flow File=f01
Plan File=p01
Y Axis Title=Elevation
X Axis Title(PF)=Main Channel Distance
X Axis Title(XS)=Station
BEGIN DESCRIPTION:
Stream0196_DS
END DESCRIPTION:
DSS Export Rating Curves= 0
DSS Export Rating Curve Sorted= 0
DSS Export Volume Flow Curves= 0
DXF OffsetX= 0
DXF OffsetY= 0
DXF ScaleX= 1
DXF ScaleY= 10

--- Stream0196_DS.p01 (plan) ---

Plan Title=Multiple Run
Short Identifier=Multiple
Geom File=g01
Flow File=f01
Subcritical Flow
K Sum by GR= 0
Std Step Tol= 0.01
Critical Tol= 0.01
Num of Std Step Trials= 20
Max Error Tol= 0.3
Flow Tol Ratio= 0.001
Split Flow NTrial= 30
Split Flow Tol= 0.02
Split Flow Ratio= 0.02
Log Output Level= 0
Friction Slope Method= 1
Unsteady Friction Slope Method= 2
Unsteady Bridges Friction Slope Method= 1
Parabolic Critical Depth
Global Vel Dist=  1 , 1 , 1
Global Log Level= 0
CheckData=True
Encroach Param= -1, 0, 0, 0
BEGIN DESCRIPTION:
Multiple Run
END DESCRIPTION:

--- Stream0196_DS.f01 (steady flow) ---

Flow Title=Multiple
Number of Profiles=7
Profile Names=10-year,25-year,50-year,1pct_min,100-year,1pct_plu,500-year
River Rch & RM= Stream0196_DS,Reach-1,5876
    1140    1936    2695    1818    3627    7236    6497
River Rch & RM= Stream0196_DS,Reach-1,3658
    1487    2554    3582    2430    4848    9674    8795
Boundary for River Rch & Prof#=Stream0196_DS,Reach-1,1
Up Type=0
Dn Type=3
Dn Slope=0.005
Boundary for River Rch & Prof#=Stream0196_DS,Reach-1,2
Up Type=0
Dn Type=3
Dn Slope=0.005
Boundary for River Rch & Prof#=Stream0196_DS,Reach-1,3
Up Type=0
Dn Type=3
Dn Slope=0.005
Boundary for River Rch & Prof#=Stream0196_DS,Reach-1,4
Up Type=0
Dn Type=3
Dn Slope=0.005
Boundary for River Rch & Prof#=Stream0196_DS,Reach-1,5
Up Type=0
Dn Type=3
Dn Slope=0.005
Boundary for River Rch & Prof#=Stream0196_DS,Reach-1,6
Up Type=0
Dn Type=3
Dn Slope=0.005
Boundary for River Rch & Prof#=Stream0196_DS,Reach-1,7
Up Type=0
Dn Type=3
Dn Slope=0.005

--- Stream0196_DS.g01 (geometry) ---

Geom Title=Existing Conditions
Program Version=4.10

River Reach=Stream0196_DS   ,Reach-1
Reach XY= 30
        2140025.       13892625.      2139926.19     13892464.51
      2139928.75     13892126.55      2140001.29     13891998.18
      2140314.48     13891734.78       2140341.3     13891607.87
      2140455.16     13891545.38      2140661.36      13891338.2
      2140711.33     13891238.22      2140861.07     13891225.67
      2141073.43     13891278.79      2141134.66     13891323.62
      2141561.09     13891374.33      2141688.22     13891311.38
      2141914.24     13891084.68      2141975.41       13890950.
      2141930.09      13890772.7      2142069.47     13890627.42
      2142091.31     13890507.87      2142188.55     13890461.51
      2142254.59     13890344.77      2142415.99     13890232.02
      2142374.61       13890100.      2142422.64     13890019.03
      2142428.82     13889926.58      2142494.63     13889804.53
      2142619.64      13889727.7      2142628.76     13889576.56
      2142922.72     13888969.43        2142875.       13888775.

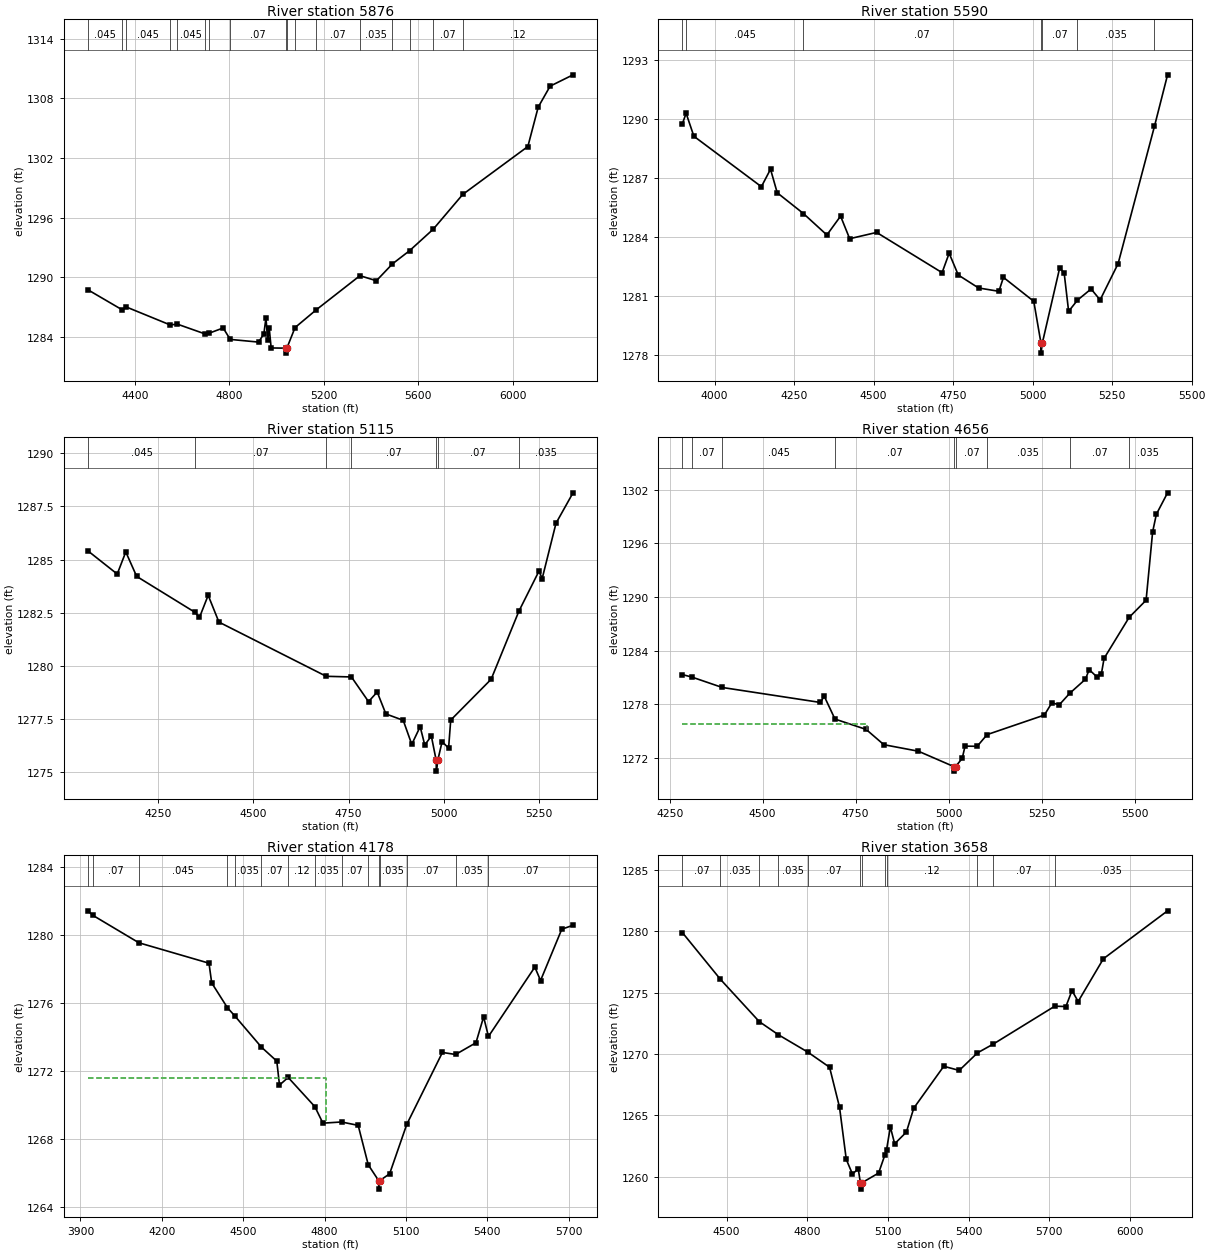
Type RM Length L Ch R = 1 ,5876    ,286,286,286
BEGIN DESCRIPTION:
Stream0196_DS 11.0
END DESCRIPTION:
XS GIS Cut Line= 4
      2140520.06     13893117.44      2140077.58     13892595.46
      2139974.72     13892545.11      2138728.71       13892704.
#Sta/Elev= 30
  4201.2 1288.74  4346.8 1286.72  4363.9 1287.01  4549.3 1285.21  4580.6 1285.28
  4696.4 1284.31    4713 1284.36  4774.1  1284.9    4804 1283.75    4924 1283.48
  4946.5  1284.3  4955.2 1285.89  4963.4 1283.68    4969 1284.93  4977.4 1282.89
  5039.9 1282.87  5040.1 1282.37  5043.9 1282.87  5078.6 1284.94  5168.6 1286.73
  5353.5 1290.16  5423.1 1289.65  5491.4 1291.35  5564.1 1292.68  5663.8 1294.83
    5789 1298.33  6064.8 1303.15  6108.6 1307.11    6159 1309.22  6256.1 1310.36
#Mann= 17 ,-1 , 0
  4201.2    .045       0  4346.8    .035       0  4363.9    .045       0
  4549.3    .035       0  4580.6    .045       0  4696.4     .07       0
    4713    .035       0    4804     .07       0  5039.9     .05       0
  5043.9     .07       0  5078.6    .035       0  5168.6     .07       0
  5353.5    .035       0  5491.4     .07       0  5564.1    .035       0
  5663.8     .07       0    5789     .12       0
Bank Sta=5039.9,5043.9
XS Rating Curve= 0 ,0
Exp/Cntr=0.3,0.1

Type RM Length L Ch R = 1 ,5590    ,475,475,475
BEGIN DESCRIPTION:
Stream0196_DS 10.0
END DESCRIPTION:
XS GIS Cut Line= 3
      2140625.02     13893125.02        2139925.       13892275.
      2139625.02     13891975.02
#Sta/Elev= 30
  3898.8 1289.78  3910.3  1290.3  3934.7 1289.13    4147 1286.56  4175.7 1287.45
  4196.8 1286.25  4279.3 1285.19  4352.9  1284.1    4396 1285.06  4424.6 1283.91
  4509.3 1284.23  4715.2 1282.18  4737.4 1283.17  4766.1 1282.06  4829.9  1281.4
  4893.8 1281.23  4908.1 1281.94  5003.5 1280.72  5026.2 1278.58  5026.5 1278.08
  5030.2 1278.58  5084.8 1282.41    5099 1282.17  5113.1 1280.21    5141 1280.78
  5183.8 1281.35  5212.1 1280.79  5268.7 1282.64  5382.9 1289.63  5424.2 1292.26
#Mann= 7 ,-1 , 0
  3898.8     .07       0  3910.3    .045       0  4279.3     .07       0
  5026.2     .05       0  5030.2     .07       0    5141    .035       0
  5382.9     .07       0
Bank Sta=5026.2,5030.2
XS Rating Curve= 0 ,0
Exp/Cntr=0.3,0.1

Type RM Length L Ch R = 1 ,5115    ,459,459,459
BEGIN DESCRIPTION:
Stream0196_DS 9.0
END DESCRIPTION:
XS GIS Cut Line= 3
        2140525.     13892725.01        2140125.       13891875.
      2139825.03     13891725.01
#Sta/Elev= 30
  4064.9 1285.41  4141.9 1284.32  4164.4 1285.36    4193 1284.21  4346.2 1282.52
  4358.1 1282.28  4380.9 1283.32  4409.2 1282.06  4691.2 1279.51  4757.4 1279.48
  4802.3 1278.32  4825.1 1278.77  4847.9 1277.74  4893.5 1277.44  4915.9 1276.31
    4938 1277.14  4950.1 1276.28  4967.4  1276.7  4980.2 1275.55  4980.5 1275.05
  4984.2 1275.55  4995.7 1276.44  5012.7 1276.13  5018.3 1277.45  5124.5 1279.37
  5197.4 1282.57  5250.3 1284.46  5258.7 1284.11    5295 1286.71  5339.7 1288.14
#Mann= 7 ,-1 , 0
  4064.9    .045       0  4346.2     .07       0  4691.2    .045       0
  4757.4     .07       0  4980.2     .05       0  4984.2     .07       0
  5197.4    .035       0
Bank Sta=4980.2,4984.2
XS Rating Curve= 0 ,0
Exp/Cntr=0.3,0.1

Type RM Length L Ch R = 1 ,4656    ,478,478,478
BEGIN DESCRIPTION:
Stream0196_DS 8.0
END DESCRIPTION:
XS GIS Cut Line= 3
        2140475.     13892274.97        2140425.       13891575.
      2139825.03       13891525.
#Sta/Elev= 30
  4284.5 1281.31  4310.1 1281.03  4391.4 1279.87  4655.4 1278.19  4665.4  1278.9
  4694.4 1276.33  4778.2 1275.17  4825.8 1273.46  4918.6 1272.73  5014.4    1271
  5014.6  1270.5  5018.4    1271  5036.4 1271.93    5044  1273.3  5076.6 1273.28
  5103.3 1274.59  5257.2 1276.78  5277.3 1278.15  5297.3 1277.93  5325.2 1279.21
  5367.6 1280.79  5377.6 1281.87  5397.7 1281.08  5410.2 1281.34  5417.7 1283.13
    5485 1287.72  5530.6 1289.64  5548.2  1297.3  5558.2 1299.27  5588.3 1301.67
#Mann= 9 ,-1 , 0
  4284.5    .045       0  4310.1     .07       0  4391.4    .045       0
  4694.4     .07       0  5014.4     .05       0  5018.4     .07       0
  5103.3    .035       0  5325.2     .07       0    5485    .035       0
#XS Ineff= 2 , 0
       0 4779.49 1275.75               0
Permanent Ineff=
       F       F
Bank Sta=5014.4,5018.4
XS Rating Curve= 0 ,0
Exp/Cntr=0.3,0.1

Type RM Length L Ch R = 1 ,4178    ,520,520,520
BEGIN DESCRIPTION:
Stream0196_DS 7.0
END DESCRIPTION:
XS GIS Cut Line= 3
      2140744.69     13892301.33        2140725.       13891225.
      2140129.21     13890834.82
#Sta/Elev= 30
  3927.5 1281.43  3946.2 1281.16  4115.5 1279.55  4373.9 1278.35  4383.9 1277.19
  4441.9 1275.73    4469 1275.25  4567.4 1273.41  4623.9 1272.59  4633.9 1271.18
  4665.8 1271.63  4764.3 1269.91    4794 1268.94  4862.7 1269.01    4924 1268.81
  4961.2 1266.49  4999.5 1265.56  4999.8 1265.06  5003.5 1265.56  5039.9 1265.96
  5103.2 1268.87  5234.6  1273.1  5283.2 1272.98  5358.3 1273.67  5386.5 1275.19
  5404.4 1274.04  5575.4 1278.12  5596.5 1277.33  5674.8 1280.35  5716.2 1280.58
#Mann= 15 ,-1 , 0
  3927.5    .045       0  3946.2     .07       0  4115.5    .045       0
  4441.9     .07       0    4469    .035       0  4567.4     .07       0
  4665.8     .12       0  4764.3    .035       0  4862.7     .07       0
  4961.2    .035       0  4999.5    .035       0  5003.5    .035       0
  5103.2     .07       0  5283.2    .035       0  5404.4     .07       0
#XS Ineff= 2 , 0
       0 4806.22 1271.62               0
Permanent Ineff=
       F       F
Bank Sta=4999.5,5003.5
XS Rating Curve= 0 ,0
Exp/Cntr=0.3,0.1

Type RM Length L Ch R = 1 ,3658    ,234,234,234
BEGIN DESCRIPTION:
Stream0196_DS 6.4
END DESCRIPTION:
XS GIS Cut Line= 4
      2141441.92      13891948.3      2141210.53     13891320.59
      2140982.21      13891194.8      2140245.63     13890723.57
#Sta/Elev= 30
  4335.8 1279.87  4477.2 1276.07  4621.6 1272.63  4692.9 1271.56  4802.1 1270.15
  4882.9 1268.92  4919.9 1265.67    4945 1261.42  4968.1 1260.22  4989.4 1260.66
  4997.7  1259.5    4998    1259  5001.9  1259.5  5065.3 1260.31  5088.1 1261.75
  5094.9 1262.21  5108.9 1264.06    5125 1262.69  5168.5 1263.64    5196 1265.59
  5307.6    1269  5365.1 1268.66  5432.9 1270.09  5491.3  1270.8  5720.5 1273.89
  5761.8 1273.86  5784.5 1275.16  5807.4 1274.27  5901.3 1277.75  6139.9 1281.65
#Mann= 12 ,-1 , 0
  4335.8     .07       0  4477.2    .035       0  4621.6     .12       0
  4692.9    .035       0  4802.1     .07       0  4997.7     .05       0
  5001.9     .07       0  5088.1     .07       0  5094.9     .12       0
  5432.9    .035       0  5491.3     .07       0  5720.5    .035       0
Bank Sta=4997.7,5001.9
XS Rating Curve= 0 ,0
Exp/Cntr=0.3,0.1

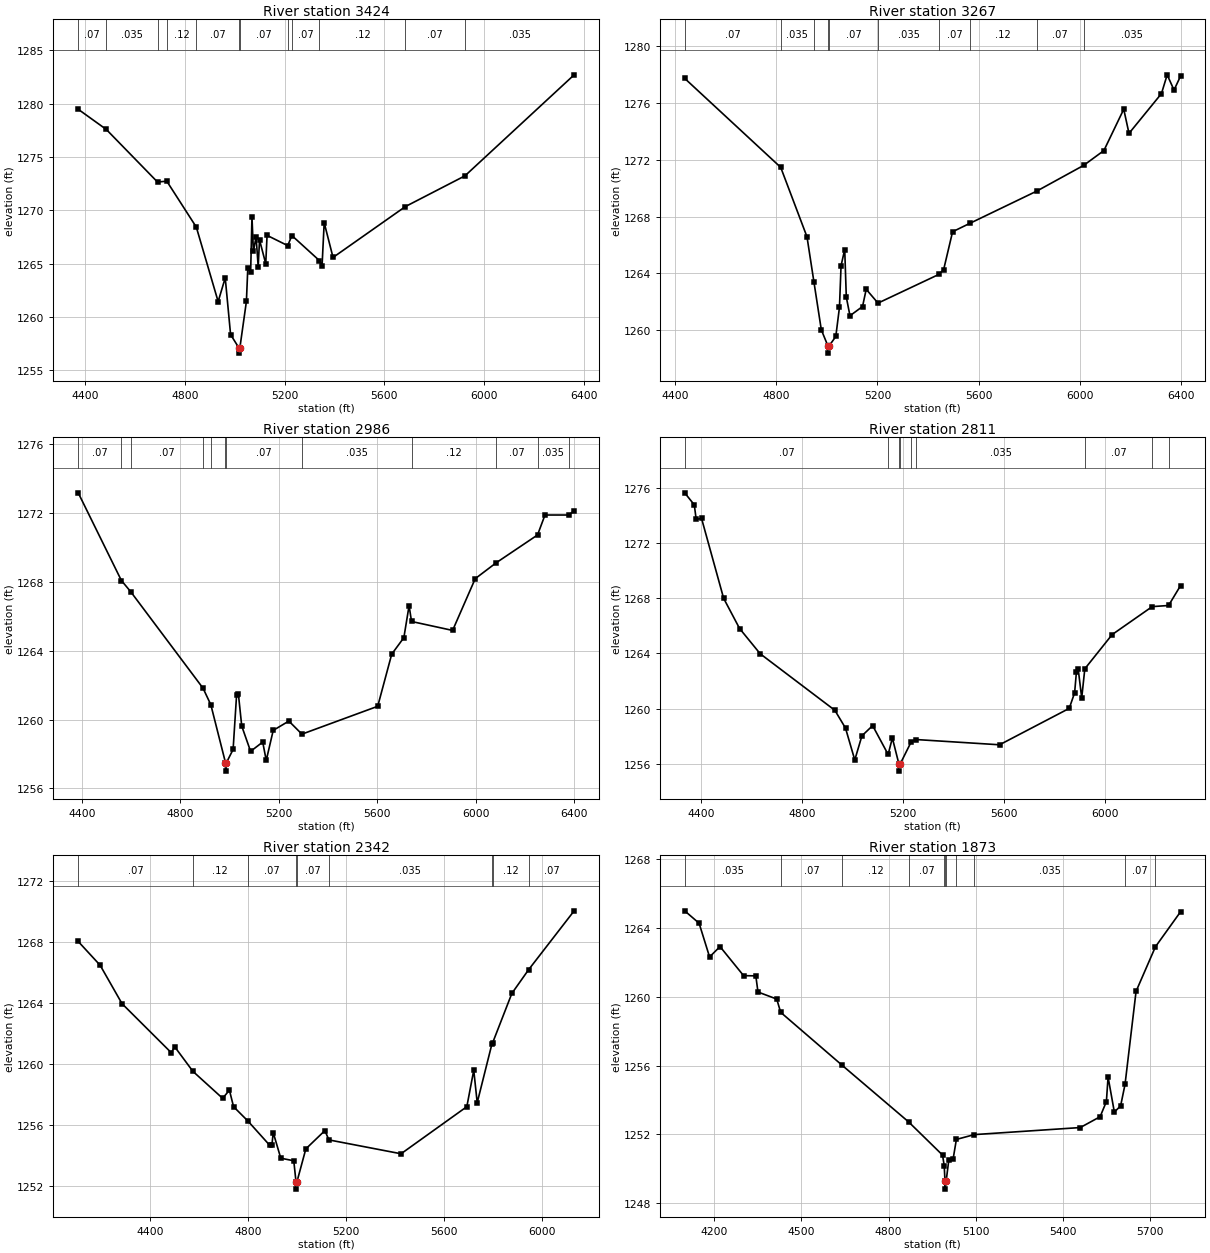
Type RM Length L Ch R = 1 ,3424    ,157,157,157
BEGIN DESCRIPTION:
Stream0196_DS 6.3
END DESCRIPTION:
XS GIS Cut Line= 4
      2141855.85     13891838.21      2141392.51     13891334.37
      2141174.41     13891252.83      2140309.22     13890617.75
#Sta/Elev= 30
  4371.2 1279.48  4483.9 1277.59  4689.5 1272.66  4726.7 1272.74  4845.3 1268.43
  4932.9 1261.45  4961.3 1263.68  4982.8 1258.36  5015.9 1257.12  5016.1 1256.62
  5020.1 1257.12  5046.3 1261.47  5051.9 1264.62  5063.3  1264.2  5068.6  1269.4
  5074.4 1266.16  5085.1 1267.52  5093.6 1264.73  5098.9 1267.24  5123.9    1265
  5129.2 1267.66  5212.1  1266.7  5228.9 1267.64  5339.6 1265.29    5350 1264.83
  5358.5 1268.85    5394 1265.59  5684.5 1270.36  5923.5 1273.24  6361.8 1282.71
#Mann= 12 ,-1 , 0
  4371.2     .07       0  4483.9    .035       0  4689.5     .07       0
  4726.7     .12       0  4845.3     .07       0  5015.9     .05       0
  5020.1     .07       0  5212.1    .035       0  5228.9     .07       0
  5339.6     .12       0  5684.5     .07       0  5923.5    .035       0
Bank Sta=5015.9,5020.1
XS Rating Curve= 0 ,0
Exp/Cntr=0.3,0.1

Type RM Length L Ch R = 1 ,3267    ,281,281,281
BEGIN DESCRIPTION:
Stream0196_DS 6.2
END DESCRIPTION:
XS GIS Cut Line= 3
       2141978.4     13891765.93      2141584.67     13891364.21
      2140483.26     13890500.95
#Sta/Elev= 30
  4437.5 1277.72  4817.4 1271.46  4921.4 1266.57  4948.7 1263.41    4978 1260.03
  5004.3 1258.89  5004.5 1258.39  5008.5 1258.89  5035.3 1259.56  5049.8 1261.61
  5056.1 1264.54  5070.6 1265.68  5076.9 1262.33  5091.4 1261.02  5141.1 1261.67
  5155.6 1262.88  5202.3 1261.91  5443.2 1263.93    5462 1264.27  5497.3 1266.93
  5565.5 1267.52  5830.4 1269.79  6015.9  1271.6  6095.8 1272.64  6174.4 1275.55
  6195.2 1273.85  6323.6 1276.65  6346.2 1277.97  6373.3  1276.9  6399.4 1277.89
#Mann= 10 ,-1 , 0
  4437.5     .07       0  4817.4    .035       0  4948.7     .07       0
  5004.3     .05       0  5008.5     .07       0  5202.3    .035       0
  5443.2     .07       0  5565.5     .12       0  5830.4     .07       0
  6015.9    .035       0
Bank Sta=5004.3,5008.5
XS Rating Curve= 0 ,0
Exp/Cntr=0.3,0.1

Type RM Length L Ch R = 1 ,2986    ,175,175,175
BEGIN DESCRIPTION:
Stream0196_DS 6.1
END DESCRIPTION:
XS GIS Cut Line= 3
       2142116.4     13891727.52      2141801.67     13891198.34
      2140752.08     13890270.64
#Sta/Elev= 30
  4384.3 1273.18  4559.9 1268.08  4597.3 1267.44  4891.9 1261.82  4923.5 1260.86
    4983  1257.5  4983.2    1257  4987.2  1257.5  5014.1 1258.26  5028.3 1261.44
  5035.6 1261.48  5049.2 1259.62  5085.2 1258.15  5134.5 1258.69  5148.8 1257.62
  5177.2 1259.37  5240.8 1259.91  5293.9 1259.15  5602.1 1260.77    5659  1263.8
  5708.4 1264.76  5729.6 1266.62  5739.6  1265.7  5906.6 1265.18  5998.6 1268.19
  6083.5 1269.11  6251.9 1270.73  6282.2 1271.89    6380 1271.89  6400.8 1272.15
#Mann= 12 ,-1 , 0
  4384.3     .07       0  4559.9    .035       0  4597.3     .07       0
  4891.9    .035       0  4923.5     .07       0    4983     .05       0
  4987.2     .07       0  5293.9    .035       0  5739.6     .12       0
  6083.5     .07       0  6251.9    .035       0    6380     .07       0
Bank Sta=4983,4987.2
XS Rating Curve= 0 ,0
Exp/Cntr=0.3,0.1

Type RM Length L Ch R = 1 ,2811    ,469,469,469
BEGIN DESCRIPTION:
Stream0196_DS 6.0
END DESCRIPTION:
XS GIS Cut Line= 3
      2142285.84     13891626.78        2141925.       13891075.
       2140981.3     13890175.36
#Sta/Elev= 30
    4336 1275.64    4374 1274.77  4381.6 1273.71  4402.7 1273.79  4490.2 1267.99
  4553.4  1265.8  4634.9 1263.97  4930.5 1259.87  4972.6 1258.58  5009.3 1256.27
  5037.6 1258.02    5080 1258.76  5141.3 1256.67  5158.1 1257.86  5184.2 1255.96
  5184.5 1255.46  5188.5 1255.96  5233.1  1257.6  5252.4 1257.75  5582.4 1257.37
  5858.2 1260.01  5879.5 1261.14  5886.5 1262.62  5893.4  1262.9  5907.6 1260.77
  5919.9 1262.88    6028 1265.36  6186.7 1267.39  6251.4 1267.47  6299.1 1268.92
#Mann= 9 ,-1 , 0
    4336     .07       0  5141.3    .035       0  5184.2     .05       0
  5188.5    .035       0  5233.1     .07       0  5252.4    .035       0
  5919.9     .07       0  6186.7    .035       0  6251.4     .07       0
Bank Sta=5184.2,5188.5
XS Rating Curve= 0 ,0
Exp/Cntr=0.3,0.1

Type RM Length L Ch R = 1 ,2342    ,469,469,469
BEGIN DESCRIPTION:
Stream0196_DS 5.0
END DESCRIPTION:
XS GIS Cut Line= 3
      2142425.01     13891475.02        2142025.       13890675.
      2141225.01     13889875.01
#Sta/Elev= 30
  4105.8 1268.06  4195.3  1266.5  4284.7 1263.98    4486 1260.76  4499.9 1261.15
  4574.2 1259.54  4695.6 1257.77  4723.5  1258.3  4740.3 1257.22  4798.3 1256.29
  4888.4 1254.68  4896.8 1254.68  4902.4 1255.52  4933.2 1253.84  4986.3 1253.67
  4995.3 1252.31  4995.6 1251.81  4999.6 1252.31  5035.6 1254.45  5113.4 1255.65
  5129.8 1255.04  5424.5 1254.13  5693.2 1257.22  5721.5 1259.61  5735.6 1257.48
  5795.3 1261.31  5798.4  1261.4  5877.1 1264.65  5945.2  1266.2  6131.6 1270.07
#Mann= 9 ,-1 , 0
  4105.8     .07       0  4574.2     .12       0  4798.3     .07       0
  4995.3     .05       0  4999.6     .07       0  5129.8    .035       0
  5795.3     .07       0  5798.4     .12       0  5945.2     .07       0
Bank Sta=4995.3,4999.6
XS Rating Curve= 0 ,0
Exp/Cntr=0.3,0.1

Type RM Length L Ch R = 1 ,1873    ,464,464,464
BEGIN DESCRIPTION:
Stream0196_DS 4.0
END DESCRIPTION:
XS GIS Cut Line= 3
      2142775.02     13891075.03        2142275.       13890325.
      2141574.96     13889924.98
#Sta/Elev= 30
  4098.1    1265  4147.7 1264.28  4183.8 1262.32  4219.8 1262.92    4301 1261.23
    4343 1261.22  4350.5 1260.28  4415.1 1259.87  4428.6  1259.1    4641 1256.01
  4869.1 1252.73    4986  1250.8  4991.8 1250.18  4994.3 1249.32  4994.6 1248.82
  4998.7 1249.32  5007.4 1250.49  5022.6 1250.59  5033.7 1251.71  5095.5 1251.99
  5460.2  1252.4  5528.6 1253.03  5550.2 1253.91    5556 1255.34  5577.6  1253.3
  5599.2 1253.66  5614.4 1254.91  5652.4 1260.32  5719.1 1262.91  5805.8 1264.95
#Mann= 11 ,-1 , 0
  4098.1    .035       0  4428.6     .07       0    4641     .12       0
  4869.1     .07       0  4991.8    .035       0  4994.3    .035       0
  4998.7    .035       0  5033.7     .07       0  5095.5    .035       0
  5614.4     .07       0  5719.1     .12       0
Bank Sta=4994.3,4998.7
XS Rating Curve= 0 ,0
Exp/Cntr=0.3,0.1

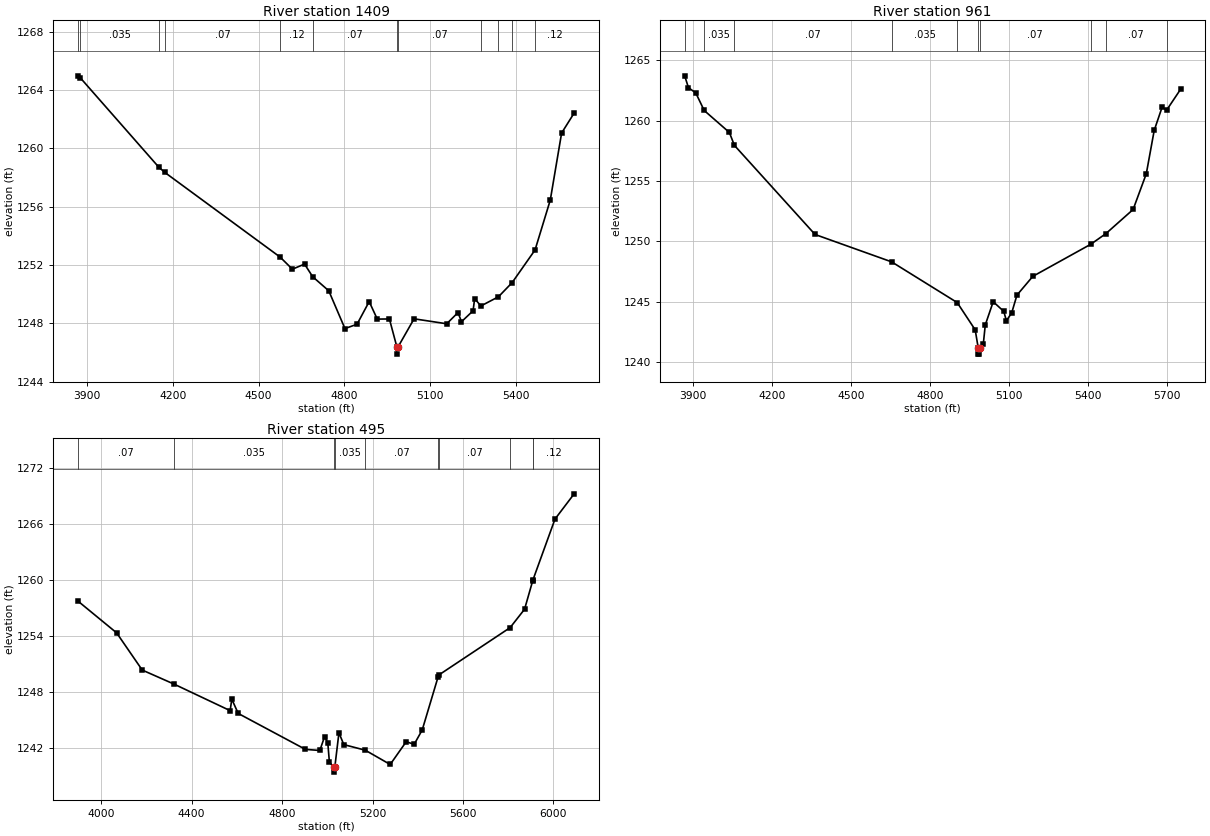
Type RM Length L Ch R = 1 ,1409    ,448,448,448
BEGIN DESCRIPTION:
Stream0196_DS 3.0
END DESCRIPTION:
XS GIS Cut Line= 3
        2143225.       13890775.        2142425.       13889975.
      2141875.03     13889725.01
#Sta/Elev= 30
  3868.6 1264.97  3875.2 1264.85  4150.6 1258.71  4171.7 1258.35  4575.1 1252.55
  4618.1 1251.72  4660.6 1252.07  4689.3  1251.2  4745.4 1250.24    4802 1247.65
  4844.4 1247.95  4886.8  1249.5  4915.1  1248.3  4957.6 1248.31  4983.6  1246.4
  4983.9  1245.9    4988  1246.4  5043.9 1248.32  5158.2 1247.98  5197.7 1248.75
  5209.8 1248.12  5250.4 1248.87  5255.9 1249.71  5277.6  1249.2  5339.2 1249.83
  5387.1  1250.8  5467.3 1253.04  5520.6 1256.46  5560.2 1261.05  5604.1 1262.42
#Mann= 12 ,-1 , 0
  3868.6     .07       0  3875.2    .035       0  4150.6     .12       0
  4171.7     .07       0  4575.1     .12       0  4689.3     .07       0
  4983.6     .05       0    4988     .07       0  5277.6    .035       0
  5339.2     .12       0  5387.1     .07       0  5467.3     .12       0
Bank Sta=4983.6,4988
XS Rating Curve= 0 ,0
Exp/Cntr=0.3,0.1

Type RM Length L Ch R = 1 ,961     ,466,466,466
BEGIN DESCRIPTION:
Stream0196_DS 2.0
END DESCRIPTION:
XS GIS Cut Line= 3
      2143425.01     13890425.01        2142625.       13889625.
      2141874.95       13889675.
#Sta/Elev= 30
  3868.3 1263.72  3882.5 1262.75  3910.7 1262.29  3942.4 1260.85    4038 1259.03
  4057.1 1257.96  4363.3 1250.58  4654.3 1248.31  4903.1 1244.94  4971.4 1242.68
    4983 1241.17  4983.4 1240.67  4987.7 1240.67  4988.1 1241.17  5002.2 1241.51
  5009.7 1243.09  5039.8 1245.01  5079.9 1244.21  5089.9 1243.44  5109.9 1244.08
    5130 1245.56  5190.1 1247.11  5410.3 1249.77  5467.6 1250.65    5571 1252.65
  5621.1 1255.61  5651.1  1259.2  5681.2 1261.13    5698 1260.87  5751.4 1262.61
#Mann= 10 ,-1 , 0
  3868.3     .07       0  3942.4    .035       0  4057.1     .07       0
  4654.3    .035       0  4903.1     .07       0    4983     .05       0
  4988.1     .07       0  5410.3     .12       0  5467.6     .07       0
    5698     .12       0
Bank Sta=4983,4988.1
XS Rating Curve= 0 ,0
Exp/Cntr=0.3,0.1

Type RM Length L Ch R = 1 ,495     ,0,0,0
BEGIN DESCRIPTION:
Stream0196_DS 1.0
END DESCRIPTION:
XS GIS Cut Line= 3
      2143575.02     13890025.02        2142825.       13889225.
        2142075.       13888425.
#Sta/Elev= 30
  3898.3 1257.73  4068.1 1254.35  4181.4 1250.36  4321.6 1248.86  4570.2 1246.01
  4577.5 1247.24  4605.9 1245.71  4902.9 1241.86  4966.8 1241.74  4987.8 1243.22
    5002 1242.58  5008.9 1240.54  5027.7 1239.92  5028.1 1239.42  5032.9 1239.92
  5051.3 1243.64  5072.8 1242.37  5167.8 1241.77    5278 1240.24  5348.8 1242.68
    5384  1242.4  5419.6 1243.94  5489.8 1249.63  5492.3 1249.82  5808.4 1254.91
  5872.2 1256.88  5908.3 1259.94  5908.8 1259.99  6006.7 1266.54  6091.5 1269.25
#Mann= 10 ,-1 , 0
  3898.3     .07       0  4321.6    .035       0  5027.7    .035       0
  5032.9    .035       0  5167.8     .07       0  5489.8     .12       0
  5492.3     .07       0  5808.4    .035       0  5908.3     .07       0
  5908.8     .12       0
Bank Sta=5027.7,5032.9
XS Rating Curve= 0 ,0
Exp/Cntr=0.3,0.1

Chan Stop Cuts=-1
Use User Specified Reach Order=0
Composite Channel Slope=5