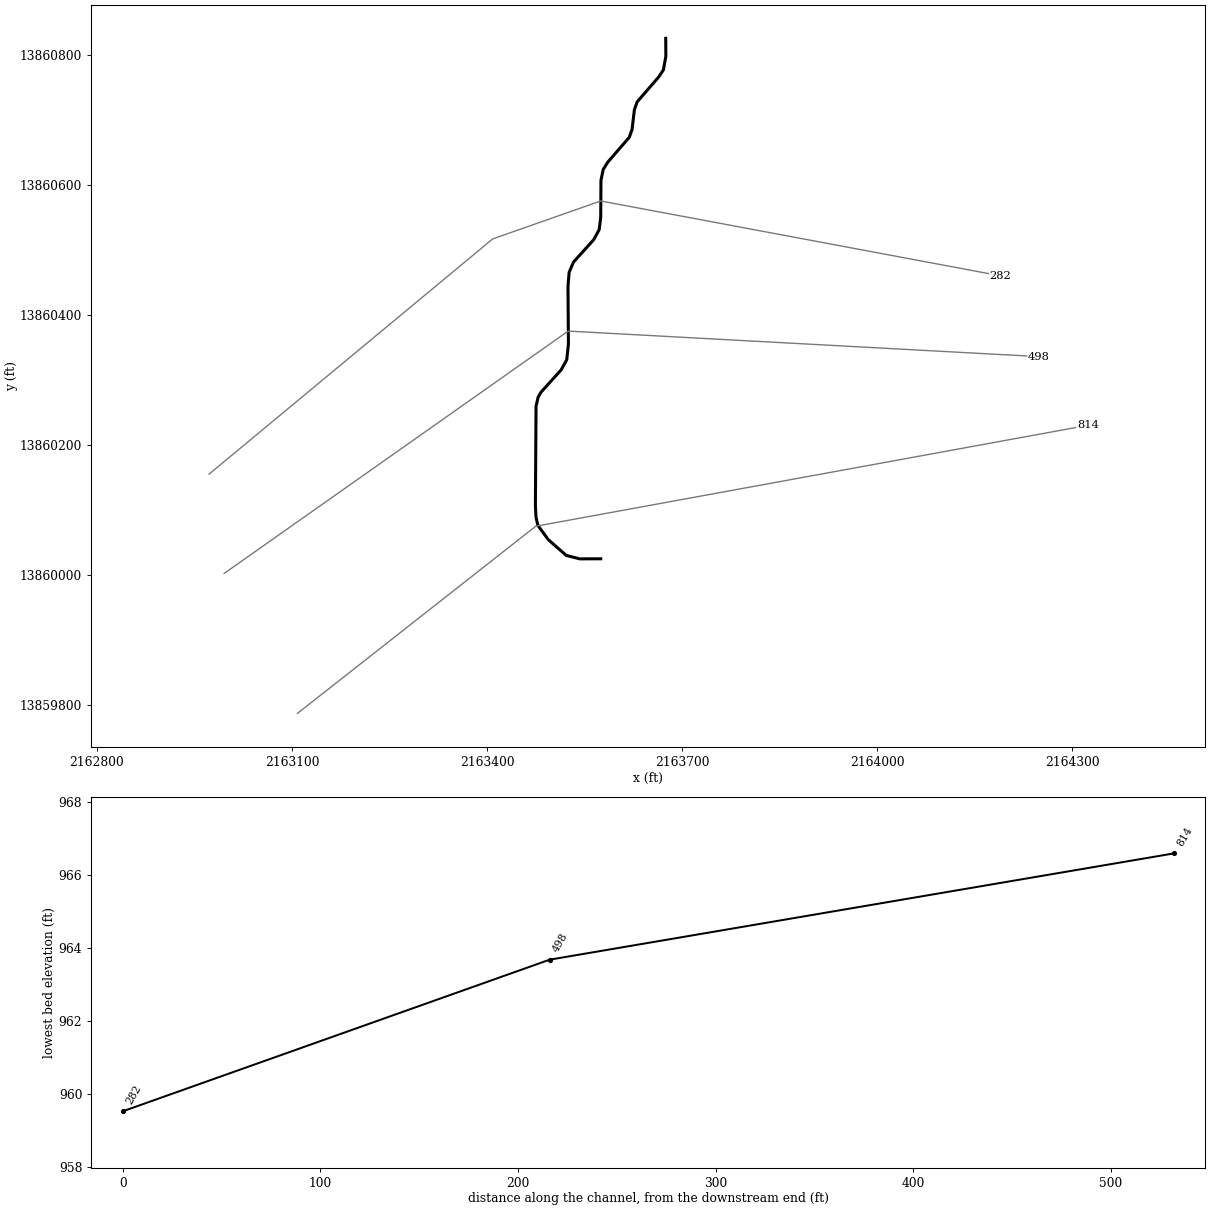
--- Stream0197_DS.prj (project) ---

Proj Title=Stream0197_DS Base Level Engineering
Current Plan=p01
Default Exp/Contr=0.3,0.1
English Units
Geom File=g01
Flow File=f01
Plan File=p01
BEGIN DESCRIPTION:
Stream0197_DS
END DESCRIPTION:

--- Stream0197_DS.p01 (plan) ---

Plan Title=Multiple Run
Short Identifier=Multiple
Geom File=g01
Flow File=f01
Subcritical Flow
K Sum by GR= 0
Std Step Tol= 0.01
Critical Tol= 0.01
Num of Std Step Trials= 20
Max Error Tol= 0.3
Flow Tol Ratio= 0.001
Split Flow NTrial= 30
Split Flow Tol= 0.02
Split Flow Ratio= 0.02
Log Output Level= 0
Friction Slope Method= 1
Unsteady Friction Slope Method= 2
Unsteady Bridges Friction Slope Method= 1
Parabolic Critical Depth
Global Vel Dist=  1 , 1 , 1
Global Log Level= 0
CheckData=True
Encroach Param= -1, 0, 0, 0
BEGIN DESCRIPTION:
Multiple Run
END DESCRIPTION:

--- Stream0197_DS.f01 (steady flow) ---

Flow Title=Multiple
Number of Profiles=7
Profile Names=10-year,25-year,50-year,1pct_min,100-year,1pct_plu,500-year
River Rch & RM= Stream0197_DS,Reach-1,814
    1051    1777    2466    1658    3307    6599    5888
Boundary for River Rch & Prof#=Stream0197_DS,Reach-1,1
Up Type=0
Dn Type=3
Dn Slope=0.005
Boundary for River Rch & Prof#=Stream0197_DS,Reach-1,2
Up Type=0
Dn Type=3
Dn Slope=0.005
Boundary for River Rch & Prof#=Stream0197_DS,Reach-1,3
Up Type=0
Dn Type=3
Dn Slope=0.005
Boundary for River Rch & Prof#=Stream0197_DS,Reach-1,4
Up Type=0
Dn Type=3
Dn Slope=0.005
Boundary for River Rch & Prof#=Stream0197_DS,Reach-1,5
Up Type=0
Dn Type=3
Dn Slope=0.005
Boundary for River Rch & Prof#=Stream0197_DS,Reach-1,6
Up Type=0
Dn Type=3
Dn Slope=0.005
Boundary for River Rch & Prof#=Stream0197_DS,Reach-1,7
Up Type=0
Dn Type=3
Dn Slope=0.005

--- Stream0197_DS.g01 (geometry) ---

Geom Title=Existing Conditions

River Reach=Stream0197_DS,Reach-1
Reach XY= 30
      2163575.00     13860025.00      2163542.92     13860024.84
      2163522.05     13860030.13      2163494.28     13860054.44
      2163478.37     13860076.26      2163475.46     13860088.75
      2163474.52     13860106.58      2163475.52     13860259.78
      2163478.78     13860273.43      2163483.14     13860281.06
      2163514.14     13860315.36      2163522.73     13860330.94
      2163525.32     13860354.87      2163524.64     13860443.33
      2163526.39     13860465.33      2163533.14     13860481.06
      2163564.11     13860515.37      2163572.64     13860530.98
      2163575.00     13860550.00      2163575.36     13860606.67
      2163578.82     13860623.42      2163585.83     13860634.65
      2163618.90     13860672.81      2163623.19     13860684.84
      2163626.77     13860715.18      2163630.95     13860727.25
      2163664.02     13860765.41      2163671.40     13860776.49
      2163675.18     13860797.32      2163675.00     13860825.00

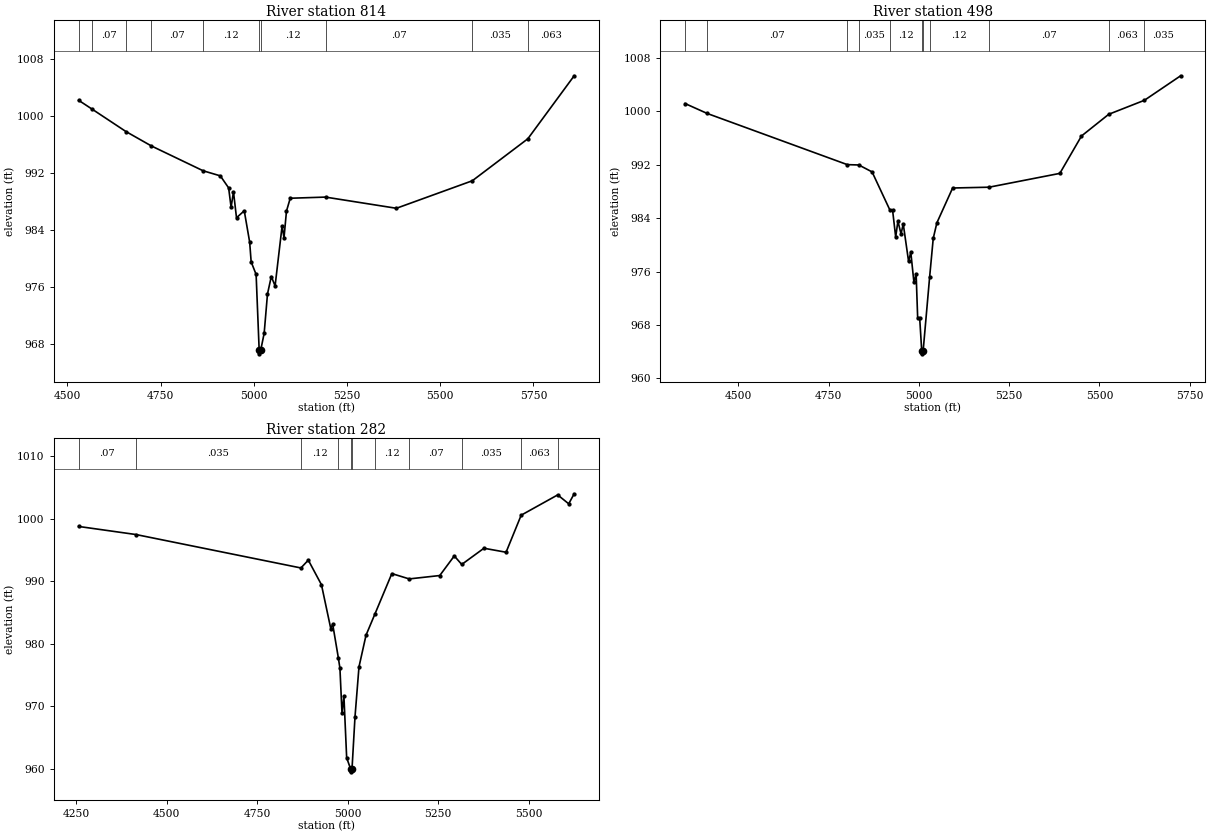
Type RM Length L Ch R = 1,814,316,316,316
BEGIN DESCRIPTION:
Stream0197_DS 2.0
END DESCRIPTION:
XS GIS Cut Line= 3
      2163108.52     13859787.35      2163475.00     13860075.00
      2164324.08     13860230.06
#Sta/Elev= 30
  4530.4 1002.17  4567.1 1000.91  4657.2  997.79  4725.7  995.76  4864.4  992.28
  4910.4  991.57  4932.7  989.88  4939.3  987.16  4945.7  989.33  4953.8  985.69
  4974.6  986.67  4989.1  982.27  4993.1  979.50  5006.4  977.74  5014.6  967.10
  5014.8  966.60  5018.7  967.10  5028.0  969.49  5036.9  975.00  5047.1  977.45
  5057.3  976.13  5076.1  984.54  5081.2  982.87  5087.8  986.62  5097.9  988.43
  5192.5  988.59  5382.6  987.02  5586.2  990.88  5735.1  996.77  5859.4 1005.61
#Mann=10,-1,0
  4530.4   0.035       0  4567.1    0.07       0  4657.2   0.035       0
  4725.7    0.07       0  4864.4    0.12       0  5014.6    0.05       0
  5018.7    0.12       0  5192.5    0.07       0  5586.2   0.035       0
  5735.1   0.063       0
Bank Sta=5014.6,5018.7
Exp/Cntr=0.3,0.1

Type RM Length L Ch R = 1,498,216,216,216
BEGIN DESCRIPTION:
Stream0197_DS 1.0
END DESCRIPTION:
XS GIS Cut Line= 3
      2162995.70     13860002.41      2163525.00     13860375.00
      2164249.15     13860335.73
#Sta/Elev= 30
  4352.4 1001.18  4413.9  999.69  4801.7  992.03  4833.5  991.98  4870.3  990.94
  4919.7  985.22  4927.0  985.24  4935.7  981.18  4941.8  983.57  4950.5  981.65
  4956.6  983.15  4971.4  977.53  4977.5  978.92  4986.2  974.39  4992.3  975.65
  4996.6  969.01  5002.2  969.01  5007.7  964.19  5007.9  963.69  5011.8  964.19
  5029.8  975.27  5039.7  980.99  5049.8  983.32  5093.4  988.53  5194.3  988.65
  5390.3  990.72  5450.3  996.32  5525.7  999.57  5624.6 1001.67  5724.9 1005.34
#Mann=11,-1,0
  4352.4   0.035       0  4413.9    0.07       0  4801.7    0.12       0
  4833.5   0.035       0  4919.7    0.12       0  5007.7    0.05       0
  5011.8    0.12       0  5029.8    0.12       0  5194.3    0.07       0
  5525.7   0.063       0  5624.6   0.035       0
Bank Sta=5007.7,5011.8
Exp/Cntr=0.3,0.1

Type RM Length L Ch R = 1,282,0,0,0
BEGIN DESCRIPTION:
Stream0197_DS 0.1
END DESCRIPTION:
XS GIS Cut Line= 4
      2162972.65     13860155.17      2163408.86     13860516.69
      2163575.00     13860575.00      2164189.81     13860459.98
#Sta/Elev= 30
  4257.4  998.74  4415.6  997.45  4871.1  992.11  4891.5  993.36  4927.8  989.43
  4953.5  982.43  4958.8  983.12  4974.5  977.73  4978.8  976.08  4984.5  968.91
  4989.8  971.66  4997.4  961.78  5008.1  960.04  5008.4  959.54  5012.2  960.04
  5020.4  968.32  5031.4  976.31  5050.9  981.38  5075.9  984.82  5122.1  991.21
  5170.0  990.36  5254.4  990.90  5294.5  994.03  5315.1  992.67  5376.4  995.26
  5437.5  994.62  5479.2 1000.54  5580.0 1003.78  5610.4 1002.36  5625.5 1003.96
#Mann=11,-1,0
  4257.4    0.07       0  4415.6   0.035       0  4871.1    0.12       0
  4974.5    0.12       0  5008.1    0.05       0  5012.2    0.12       0
  5075.9    0.12       0  5170.0    0.07       0  5315.1   0.035       0
  5479.2   0.063       0  5580.0   0.035       0
Bank Sta=5008.1,5012.2
Exp/Cntr=0.3,0.1

Chan Stop Cuts=-1