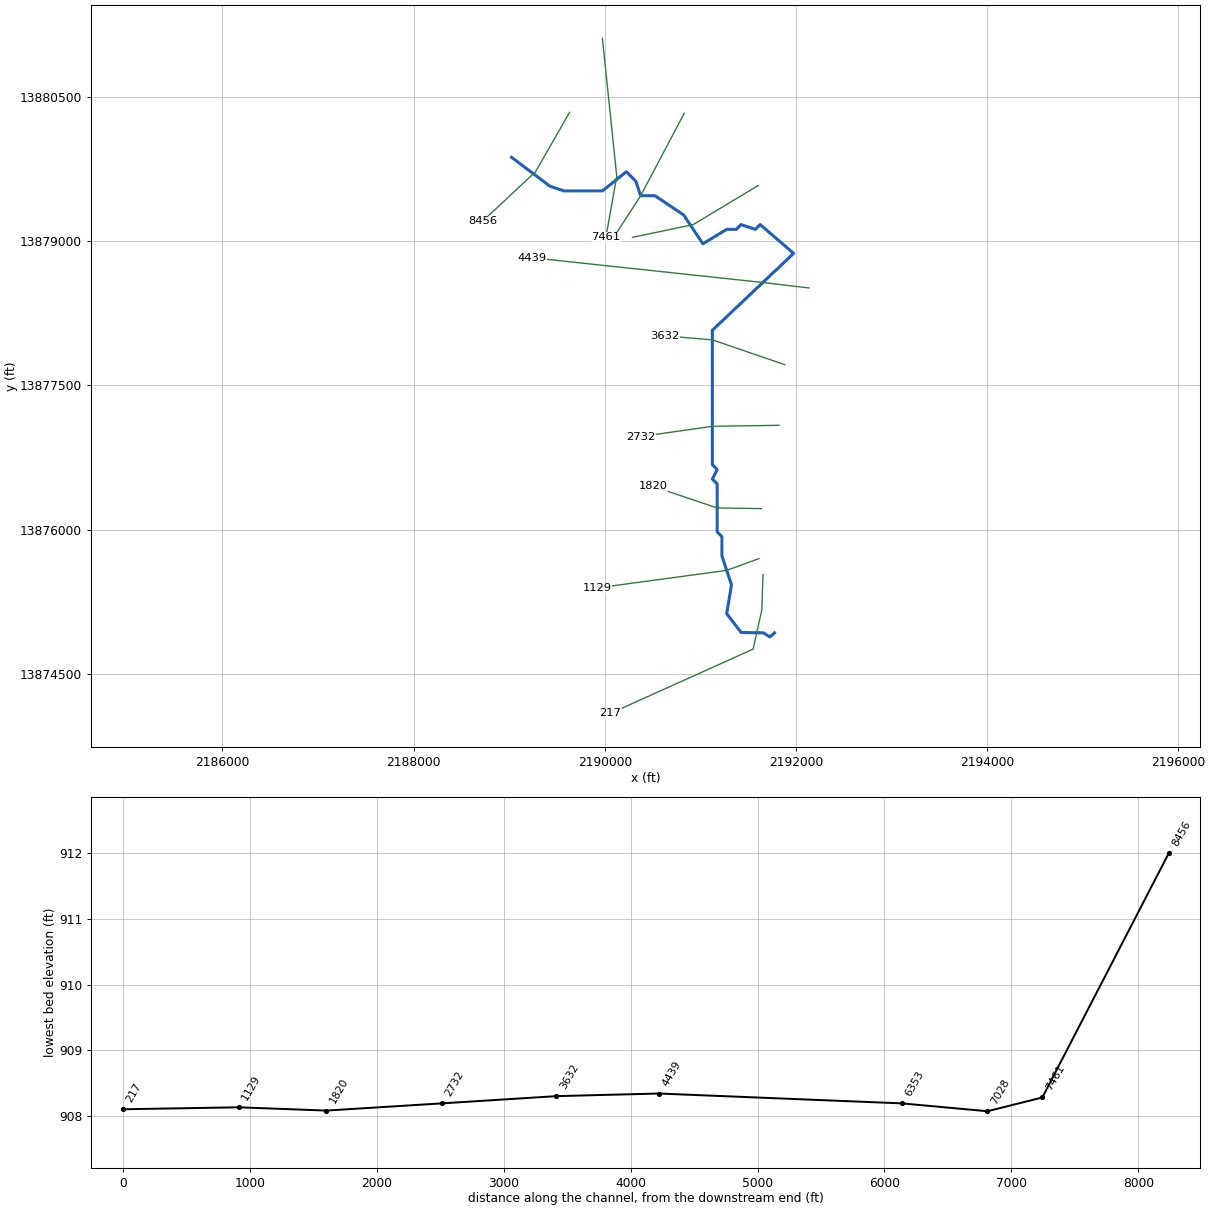
--- Stream0198_DS.prj (project) ---

Proj Title=Stream0198_DS Base Level Engineering
Current Plan=p01
Default Exp/Contr=0.3,0.1
English Units
Geom File=g01
Flow File=f01
Plan File=p01
BEGIN DESCRIPTION:
Stream0198_DS
END DESCRIPTION:

--- Stream0198_DS.p01 (plan) ---

Plan Title=Multiple Run
Short Identifier=Multiple
Geom File=g01
Flow File=f01
Subcritical Flow
K Sum by GR= 0
Std Step Tol= 0.01
Critical Tol= 0.01
Num of Std Step Trials= 20
Max Error Tol= 0.3
Flow Tol Ratio= 0.001
Split Flow NTrial= 30
Split Flow Tol= 0.02
Split Flow Ratio= 0.02
Log Output Level= 0
Friction Slope Method= 1
Unsteady Friction Slope Method= 2
Unsteady Bridges Friction Slope Method= 1
Parabolic Critical Depth
Global Vel Dist=  1 , 1 , 1
Global Log Level= 0
CheckData=True
Encroach Param= -1, 0, 0, 0
BEGIN DESCRIPTION:
Multiple Run
END DESCRIPTION:

--- Stream0198_DS.f01 (steady flow) ---

Flow Title=Multiple
Number of Profiles=7
Profile Names=10-year,25-year,50-year,1pct_min,100-year,1pct_plu,500-year
River Rch & RM= Stream0198_DS,Reach-1,8456
    1106    1866    2586    1735    3462    6908    6141
Boundary for River Rch & Prof#=Stream0198_DS,Reach-1,1
Up Type=0
Dn Type=3
Dn Slope=0.005
Boundary for River Rch & Prof#=Stream0198_DS,Reach-1,2
Up Type=0
Dn Type=3
Dn Slope=0.005
Boundary for River Rch & Prof#=Stream0198_DS,Reach-1,3
Up Type=0
Dn Type=3
Dn Slope=0.005
Boundary for River Rch & Prof#=Stream0198_DS,Reach-1,4
Up Type=0
Dn Type=3
Dn Slope=0.005
Boundary for River Rch & Prof#=Stream0198_DS,Reach-1,5
Up Type=0
Dn Type=3
Dn Slope=0.005
Boundary for River Rch & Prof#=Stream0198_DS,Reach-1,6
Up Type=0
Dn Type=3
Dn Slope=0.005
Boundary for River Rch & Prof#=Stream0198_DS,Reach-1,7
Up Type=0
Dn Type=3
Dn Slope=0.005

--- Stream0198_DS.g01 (geometry) ---

Geom Title=Existing Conditions

River Reach=Stream0198_DS,Reach-1
Reach XY= 30
      2189025.00     13879875.00      2189425.00     13879575.00
      2189575.00     13879525.00      2189975.00     13879525.00
      2190225.00     13879725.00      2190325.00     13879625.00
      2190375.00     13879475.00      2190525.00     13879475.00
      2190825.00     13879275.00      2191025.00     13878975.00
      2191275.00     13879125.00      2191375.00     13879125.00
      2191425.00     13879175.00      2191575.00     13879125.00
      2191625.00     13879175.00      2191975.00     13878875.00
      2191125.00     13878075.00      2191125.00     13876675.00
      2191175.00     13876625.00      2191125.00     13876525.00
      2191175.00     13876475.00      2191175.00     13875975.00
      2191225.00     13875925.00      2191225.00     13875725.00
      2191325.00     13875425.00      2191275.00     13875125.00
      2191426.25     13874928.45      2191661.15     13874924.23
      2191725.14     13874881.91      2191775.00     13874925.00

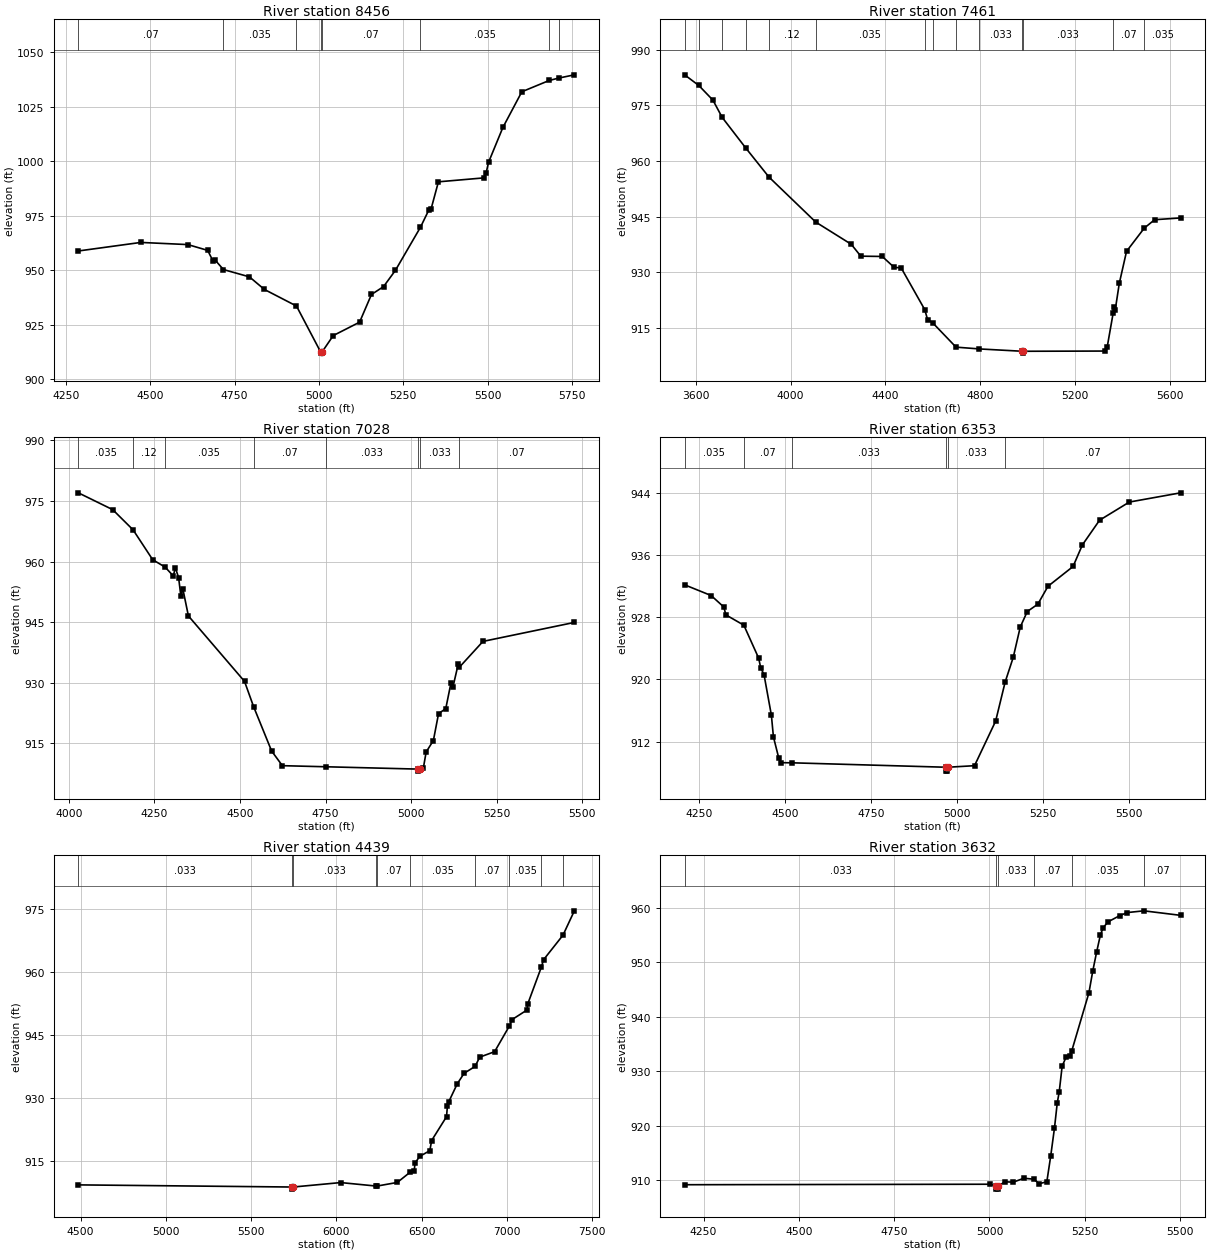
Type RM Length L Ch R = 1,8456,995,995,995
BEGIN DESCRIPTION:
Stream0198_DS 9.0
END DESCRIPTION:
XS GIS Cut Line= 3
      2189631.15     13880342.68      2189275.00     13879725.00
      2188721.13     13879209.28
#Sta/Elev= 30
  4287.0  958.87  4472.1  962.79  4611.5  961.80  4670.3  959.14  4686.1  954.24
  4691.9  954.76  4717.0  950.34  4793.9  947.00  4838.4  941.21  4933.4  933.61
  5005.1  912.50  5005.3  912.00  5009.1  912.50  5042.3  920.05  5120.4  926.20
  5155.6  938.92  5191.3  942.50  5226.5  949.96  5300.8  969.76  5325.6  977.68
  5332.5  978.28  5354.0  990.60  5488.3  992.40  5495.2  994.54  5502.5  999.54
  5545.0 1015.53  5601.2 1031.92  5682.6 1037.12  5709.9 1038.17  5756.8 1039.69
#Mann=8,-1,0
  4287.0    0.07       0  4717.0   0.035       0  4933.4    0.07       0
  5005.1    0.05       0  5009.1    0.07       0  5300.8   0.035       0
  5682.6    0.12       0  5709.9   0.035       0
Bank Sta=5005.1,5009.1
Exp/Cntr=0.3,0.1

Type RM Length L Ch R = 1,7461,433,433,433
BEGIN DESCRIPTION:
Stream0198_DS 8.0
END DESCRIPTION:
XS GIS Cut Line= 3
      2189974.73     13881113.77      2190125.00     13879675.00
      2190010.94     13879040.57
#Sta/Elev= 30
  3553.4  983.25  3613.1  980.39  3672.8  976.43  3711.7  971.79  3810.3  963.61
  3908.9  955.72  4106.1  943.59  4256.0  937.60  4296.2  934.40  4386.7  934.32
  4437.0  931.37  4466.3  931.26  4565.9  919.99  4577.7  917.33  4599.1  916.46
  4697.7  909.89  4796.3  909.41  4977.9  908.78  4978.1  908.28  4981.9  908.78
  5325.1  908.84  5335.3  910.01  5360.2  919.07  5364.0  920.67  5369.1  920.01
  5386.1  927.09  5416.6  935.70  5491.4  941.96  5535.1  944.22  5644.6  944.70
#Mann=14,-1,0
  3553.4   0.035       0  3613.1    0.07       0  3711.7   0.035       0
  3810.3    0.07       0  3908.9    0.12       0  4106.1   0.035       0
  4565.9    0.07       0  4599.1   0.035       0  4697.7    0.07       0
  4796.3   0.033       0  4977.9   0.033       0  4981.9   0.033       0
  5360.2    0.07       0  5491.4   0.035       0
Bank Sta=4977.9,4981.9
Exp/Cntr=0.3,0.1

Type RM Length L Ch R = 1,7028,675,675,675
BEGIN DESCRIPTION:
Stream0198_DS 7.0
END DESCRIPTION:
XS GIS Cut Line= 3
      2190830.86     13880333.70      2190375.00     13879475.00
      2190114.78     13879075.59
#Sta/Elev= 30
  4027.8  977.02  4128.2  972.85  4187.8  967.84  4245.0  960.45  4281.4  958.61
  4305.3  956.42  4311.0  958.50  4320.7  956.01  4327.3  951.43  4332.9  953.29
  4349.3  946.52  4513.2  930.31  4539.6  924.08  4592.4  913.05  4623.8  909.42
  4751.0  909.15  5020.7  908.57  5020.9  908.07  5024.7  908.57  5035.8  908.91
  5043.8  912.82  5064.9  915.65  5080.0  922.31  5101.1  923.56  5116.2  929.89
  5122.2  928.96  5137.3  934.52  5140.6  933.79  5209.8  940.21  5476.7  944.91
#Mann=8,-1,0
  4027.8   0.035       0  4187.8    0.12       0  4281.4   0.035       0
  4539.6    0.07       0  4751.0   0.033       0  5020.7   0.033       0
  5024.7   0.033       0  5140.6    0.07       0
Bank Sta=5020.7,5024.7
Exp/Cntr=0.3,0.1

Type RM Length L Ch R = 1,6353,1914,1914,1914
BEGIN DESCRIPTION:
Stream0198_DS 6.0
END DESCRIPTION:
XS GIS Cut Line= 3
      2191603.64     13879580.97      2190925.00     13879175.00
      2190289.19     13879041.85
#Sta/Elev= 30
  4209.2  932.19  4286.2  930.81  4323.1  929.33  4329.0  928.32  4381.2  926.99
  4424.3  922.74  4430.1  921.51  4439.8  920.62  4461.2  915.39  4467.1  912.61
  4482.6  909.87  4488.5  909.28  4522.5  909.26  4968.8  908.69  4969.1  908.19
  4972.6  908.19  4972.8  908.69  5051.1  908.89  5112.4  914.63  5140.0  919.66
  5163.5  922.84  5183.9  926.75  5204.3  928.75  5235.0  929.70  5264.4  932.00
  5337.2  934.55  5364.3  937.33  5414.2  940.51  5500.6  942.85  5649.6  944.04
#Mann=6,-1,0
  4209.2   0.035       0  4381.2    0.07       0  4522.5   0.033       0
  4968.8   0.033       0  4972.8   0.033       0  5140.0    0.07       0
Bank Sta=4968.8,4972.8
Exp/Cntr=0.3,0.1

Type RM Length L Ch R = 1,4439,807,807,807
BEGIN DESCRIPTION:
Stream0198_DS 5.0
END DESCRIPTION:
XS GIS Cut Line= 3
      2192135.01     13878515.24      2191625.00     13878575.00
      2189242.04     13878829.36
#Sta/Elev= 30
  4486.5  909.35  5742.2  908.84  5742.5  908.34  5746.2  908.84  6025.8  909.90
  6234.1  909.07  6236.2  909.05  6357.7  909.93  6435.0  912.43  6456.8  912.68
  6461.8  914.52  6488.4  916.11  6548.7  917.50  6559.2  919.91  6646.6  925.58
  6651.6  928.04  6659.4  929.11  6709.7  933.42  6749.9  935.91  6814.0  937.54
  6841.3  939.75  6928.7  941.05  7016.0  947.21  7031.5  948.70  7118.4  950.96
  7123.5  952.45  7203.6  961.25  7215.8  962.93  7329.9  968.78  7396.5  974.57
#Mann=10,-1,0
  4486.5   0.033       0  5742.2   0.033       0  5746.2   0.033       0
  6234.1   0.035       0  6236.2    0.07       0  6435.0   0.035       0
  6814.0    0.07       0  7016.0   0.035       0  7203.6    0.07       0
  7329.9   0.035       0
Bank Sta=5742.2,5746.2
Exp/Cntr=0.3,0.1

Type RM Length L Ch R = 1,3632,900,900,900
BEGIN DESCRIPTION:
Stream0198_DS 4.0
END DESCRIPTION:
XS GIS Cut Line= 3
      2191881.74     13877716.73      2191125.00     13877975.00
      2190625.34     13878016.73
#Sta/Elev= 30
  4200.4  909.11  5002.5  909.20  5018.1  908.80  5018.3  908.30  5021.8  908.30
  5022.1  908.80  5040.1  909.64  5062.7  909.59  5090.3  910.30  5116.5  910.13
  5130.5  909.29  5150.5  909.66  5160.6  914.36  5170.6  919.57  5177.9  924.20
  5182.9  926.14  5190.7  930.93  5200.7  932.52  5210.7  932.73  5215.6  933.66
  5260.9  944.41  5270.9  948.38  5281.0  951.87  5291.0  955.05  5298.2  956.37
  5311.1  957.46  5341.2  958.58  5361.3  959.16  5405.0  959.48  5501.4  958.65
#Mann=6,-1,0
  4200.4   0.033       0  5018.1   0.033       0  5022.1   0.033       0
  5116.5    0.07       0  5215.6   0.035       0  5405.0    0.07       0
Bank Sta=5018.1,5022.1
Exp/Cntr=0.3,0.1

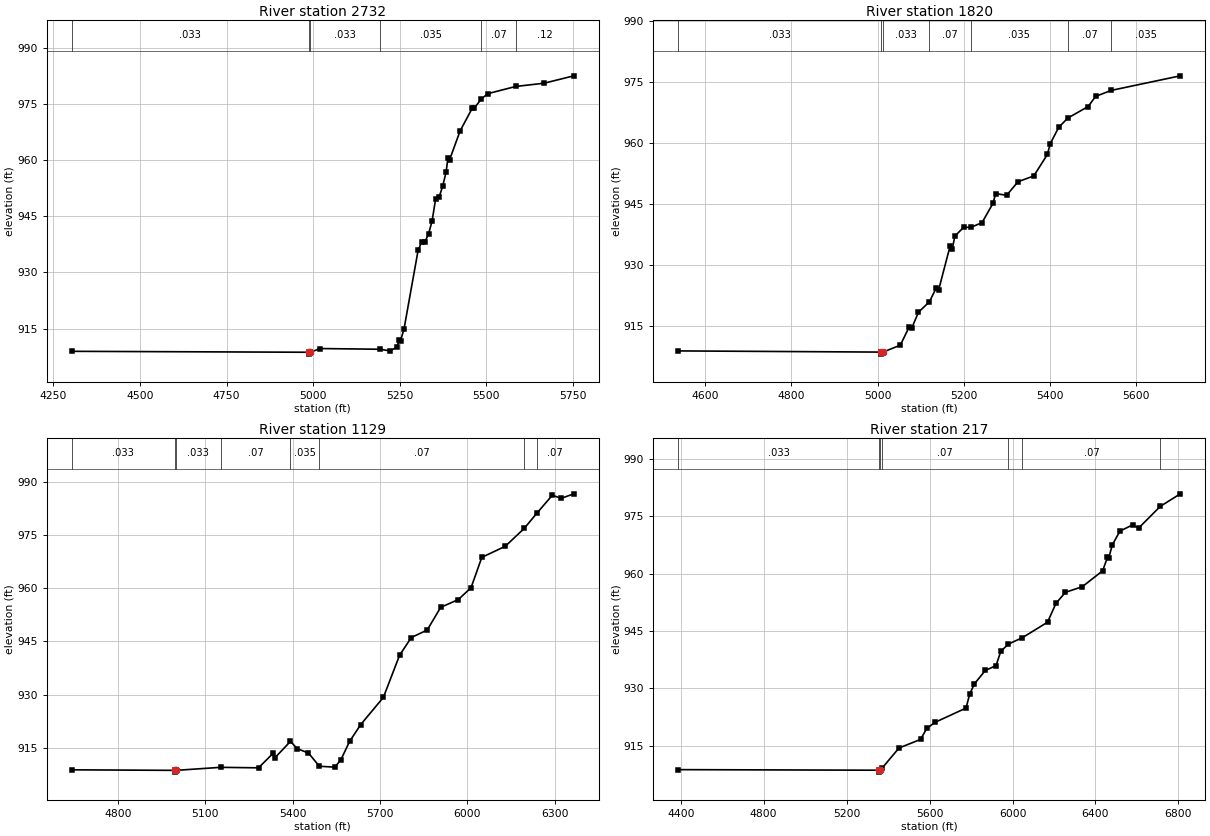
Type RM Length L Ch R = 1,2732,912,912,912
BEGIN DESCRIPTION:
Stream0198_DS 3.0
END DESCRIPTION:
XS GIS Cut Line= 3
      2191821.92     13877085.45      2191125.00     13877075.00
      2190379.96     13876968.62
#Sta/Elev= 30
  4303.0  908.94  4988.0  908.69  4988.2  908.19  4992.0  908.69  5020.2  909.68
  5194.1  909.49  5222.2  909.04  5242.4  910.12  5247.5  911.88  5252.6  911.80
  5262.6  915.01  5303.0  935.87  5313.1  938.09  5323.3  938.24  5333.3  940.32
  5343.4  943.71  5353.5  949.56  5363.7  950.12  5373.8  952.96  5383.9  956.80
  5389.0  960.44  5394.0  960.09  5424.3  967.77  5459.7  973.89  5464.8  973.79
  5485.6  976.33  5505.1  977.74  5584.7  979.64  5666.7  980.51  5752.6  982.48
#Mann=6,-1,0
  4303.0   0.033       0  4988.0   0.033       0  4992.0   0.033       0
  5194.1   0.035       0  5485.6    0.07       0  5584.7    0.12       0
Bank Sta=4988,4992
Exp/Cntr=0.3,0.1

Type RM Length L Ch R = 1,1820,691,691,691
BEGIN DESCRIPTION:
Stream0198_DS 2.0
END DESCRIPTION:
XS GIS Cut Line= 3
      2191638.15     13876217.90      2191175.00     13876225.00
      2190508.48     13876448.53
#Sta/Elev= 30
  4536.8  908.87  5008.5  908.58  5008.7  908.08  5012.5  908.58  5052.7  910.27
  5073.6  914.79  5078.9  914.38  5094.9  918.36  5120.3  920.94  5136.7  924.43
  5142.0  923.93  5168.2  934.57  5173.5  933.86  5179.3  937.05  5199.8  939.24
  5216.7  939.22  5242.6  940.40  5268.1  945.15  5274.2  947.52  5299.7  947.11
  5326.0  950.43  5362.8  951.87  5394.3  957.13  5400.8  959.75  5420.6  963.79
  5441.6  966.07  5489.0  968.92  5506.3  971.40  5542.2  972.87  5703.0  976.46
#Mann=7,-1,0
  4536.8   0.033       0  5008.5   0.033       0  5012.5   0.033       0
  5120.3    0.07       0  5216.7   0.035       0  5441.6    0.07       0
  5542.2   0.035       0
Bank Sta=5008.5,5012.5
Exp/Cntr=0.3,0.1

Type RM Length L Ch R = 1,1129,912,912,912
BEGIN DESCRIPTION:
Stream0198_DS 1.0
END DESCRIPTION:
XS GIS Cut Line= 3
      2191612.59     13875697.72      2191275.00     13875575.00
      2189921.83     13875392.63
#Sta/Elev= 30
  4640.8  908.78  4995.3  908.63  4995.6  908.13  4999.3  908.63  5152.5  909.48
  5282.5  909.34  5332.4  913.41  5337.5  912.06  5392.3  916.80  5415.3  914.75
  5454.1  913.51  5491.3  909.79  5544.9  909.53  5565.8  911.68  5595.3  916.78
  5633.5  921.53  5711.3  929.19  5766.9  941.05  5807.2  946.06  5861.9  948.18
  5908.1  954.57  5968.7  956.76  6012.4  960.11  6049.4  968.65  6130.1  971.79
  6195.3  976.84  6237.7  981.03  6291.6  986.17  6321.8  985.28  6365.4  986.56
#Mann=8,-1,0
  4640.8   0.033       0  4995.3   0.033       0  4999.3   0.033       0
  5152.5    0.07       0  5392.3   0.035       0  5491.3    0.07       0
  6195.3   0.035       0  6237.7    0.07       0
Bank Sta=4995.3,4999.3
Exp/Cntr=0.3,0.1

Type RM Length L Ch R = 1,217,0,0,0
BEGIN DESCRIPTION:
Stream0198_DS 0.1
END DESCRIPTION:
XS GIS Cut Line= 4
      2191654.85     13875531.45      2191642.48     13875163.88
      2191551.29     13874755.33      2190059.37     13874086.40
#Sta/Elev= 30
  4387.6  908.75  5357.8  908.60  5358.1  908.10  5362.0  908.60  5371.2  909.15
  5452.6  914.41  5556.3  916.64  5586.4  919.51  5625.8  921.10  5775.9  924.85
  5793.6  928.54  5816.5  931.19  5868.6  934.67  5920.4  935.93  5943.6  939.70
  5980.0  941.57  6047.8  943.25  6168.7  947.29  6209.6  952.22  6254.9  955.10
  6336.4  956.57  6434.6  960.73  6457.8  964.26  6463.3  963.95  6481.0  967.49
  6517.9  971.10  6579.2  972.74  6607.9  971.89  6712.7  977.58  6809.0  980.85
#Mann=7,-1,0
  4387.6   0.033       0  5357.8   0.033       0  5362.0   0.033       0
  5371.2    0.07       0  5980.0   0.035       0  6047.8    0.07       0
  6712.7   0.035       0
Bank Sta=5357.8,5362
Exp/Cntr=0.3,0.1

Chan Stop Cuts=-1