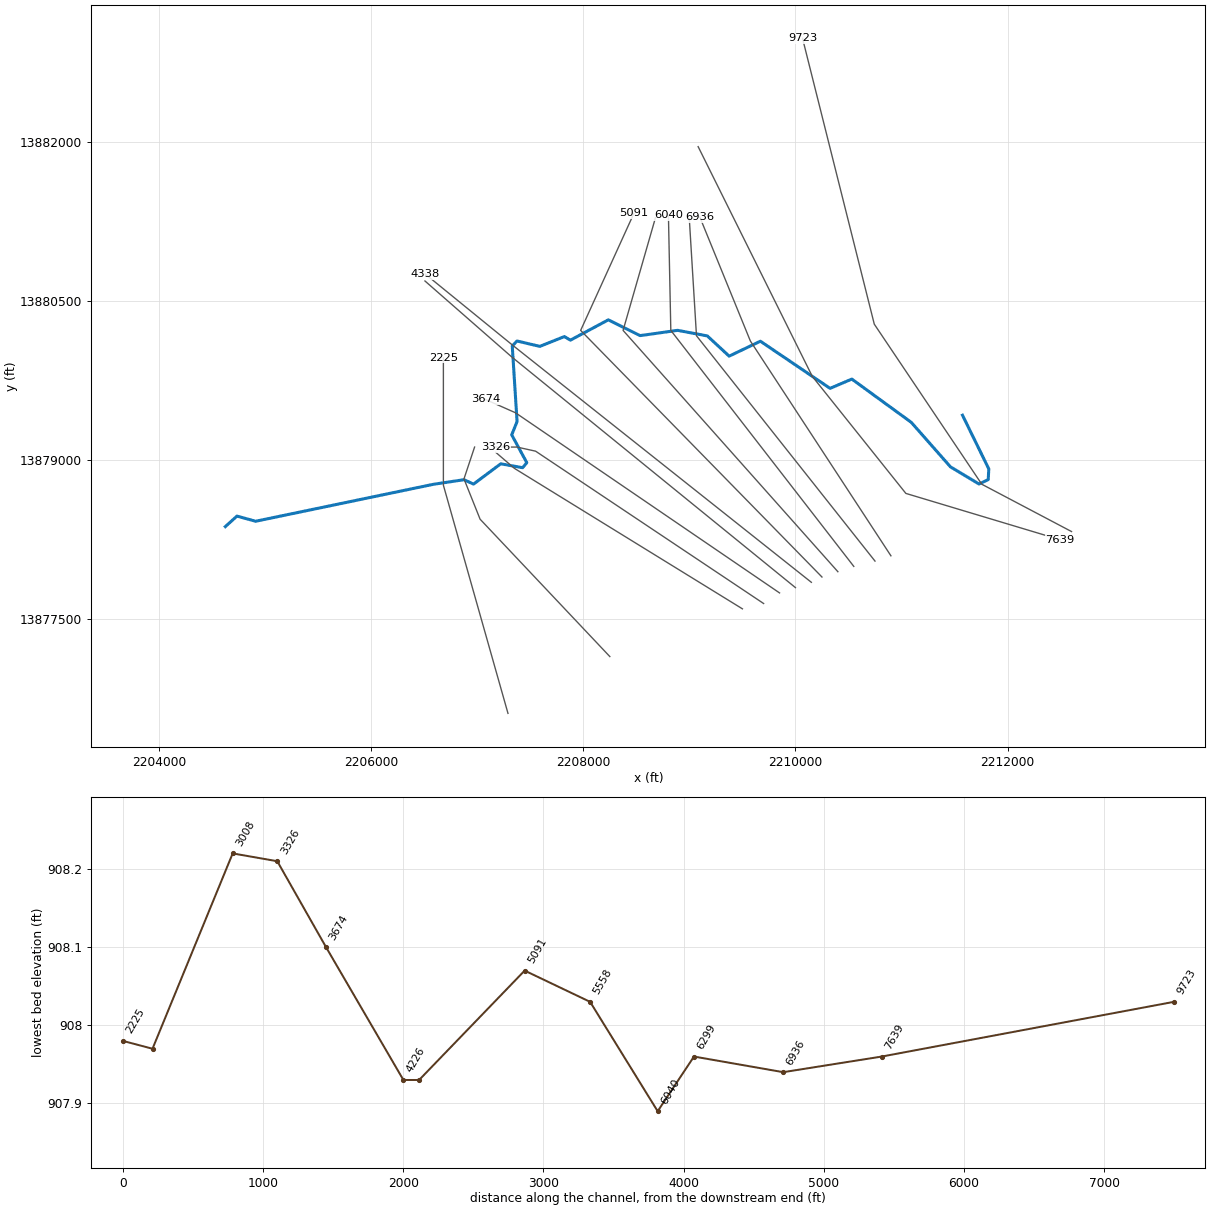
--- Stream0199_DS.prj (project) ---

Proj Title=Stream0199_DS Base Level Engineering
Current Plan=p01
Default Exp/Contr=0.3,0.1
English Units
Geom File=g01
Flow File=f01
Plan File=p01
BEGIN DESCRIPTION:
Stream0199_DS
END DESCRIPTION:

--- Stream0199_DS.p01 (plan) ---

Plan Title=Multiple Run
Short Identifier=Multiple
Geom File=g01
Flow File=f01
Subcritical Flow
K Sum by GR= 0
Std Step Tol= 0.01
Critical Tol= 0.01
Num of Std Step Trials= 20
Max Error Tol= 0.3
Flow Tol Ratio= 0.001
Split Flow NTrial= 30
Split Flow Tol= 0.02
Split Flow Ratio= 0.02
Log Output Level= 0
Friction Slope Method= 1
Unsteady Friction Slope Method= 2
Unsteady Bridges Friction Slope Method= 1
Parabolic Critical Depth
Global Vel Dist=  1 , 1 , 1
Global Log Level= 0
CheckData=True
Encroach Param= -1, 0, 0, 0
BEGIN DESCRIPTION:
Multiple Run
END DESCRIPTION:

--- Stream0199_DS.f01 (steady flow) ---

Flow Title=Multiple
Number of Profiles=7
Profile Names=10-year,25-year,50-year,1pct_min,100-year,1pct_plu,500-year
River Rch & RM= Stream0199_DS,Reach-1,9723
    1400    2373    3298    2216    4422    8823    7868
River Rch & RM= Stream0199_DS,Reach-1,4338
    2263    3920    5524    3759    7500   14964   13685
Boundary for River Rch & Prof#=Stream0199_DS,Reach-1,1
Up Type=0
Dn Type=3
Dn Slope=0.005
Boundary for River Rch & Prof#=Stream0199_DS,Reach-1,2
Up Type=0
Dn Type=3
Dn Slope=0.005
Boundary for River Rch & Prof#=Stream0199_DS,Reach-1,3
Up Type=0
Dn Type=3
Dn Slope=0.005
Boundary for River Rch & Prof#=Stream0199_DS,Reach-1,4
Up Type=0
Dn Type=3
Dn Slope=0.005
Boundary for River Rch & Prof#=Stream0199_DS,Reach-1,5
Up Type=0
Dn Type=3
Dn Slope=0.005
Boundary for River Rch & Prof#=Stream0199_DS,Reach-1,6
Up Type=0
Dn Type=3
Dn Slope=0.005
Boundary for River Rch & Prof#=Stream0199_DS,Reach-1,7
Up Type=0
Dn Type=3
Dn Slope=0.005

--- Stream0199_DS.g01 (geometry) ---

Geom Title=Existing Conditions

River Reach=Stream0199_DS,Reach-1
Reach XY= 30
      2211575.00     13879425.00      2211822.86     13878919.03
      2211817.36     13878818.45      2211730.68     13878776.69
      2211461.43     13878938.47      2211091.67     13879358.35
      2210531.66     13879766.02      2210326.50     13879678.47
      2209669.51     13880122.92      2209374.91     13879982.28
      2209169.15     13880172.94      2208888.82     13880225.44
      2208535.69     13880175.77      2208235.70     13880324.30
      2207878.33     13880133.01      2207821.78     13880166.71
      2207590.06     13880074.29      2207375.00     13880125.00
      2207330.14     13880077.59      2207375.45     13879365.72
      2207325.08     13879240.39      2207467.25     13878978.02
      2207428.01     13878930.45      2207221.58     13878967.21
      2206965.14     13878775.95      2206875.01     13878817.41
      2206585.50     13878773.78      2204911.03     13878425.55
      2204734.77     13878474.30      2204625.00     13878375.00

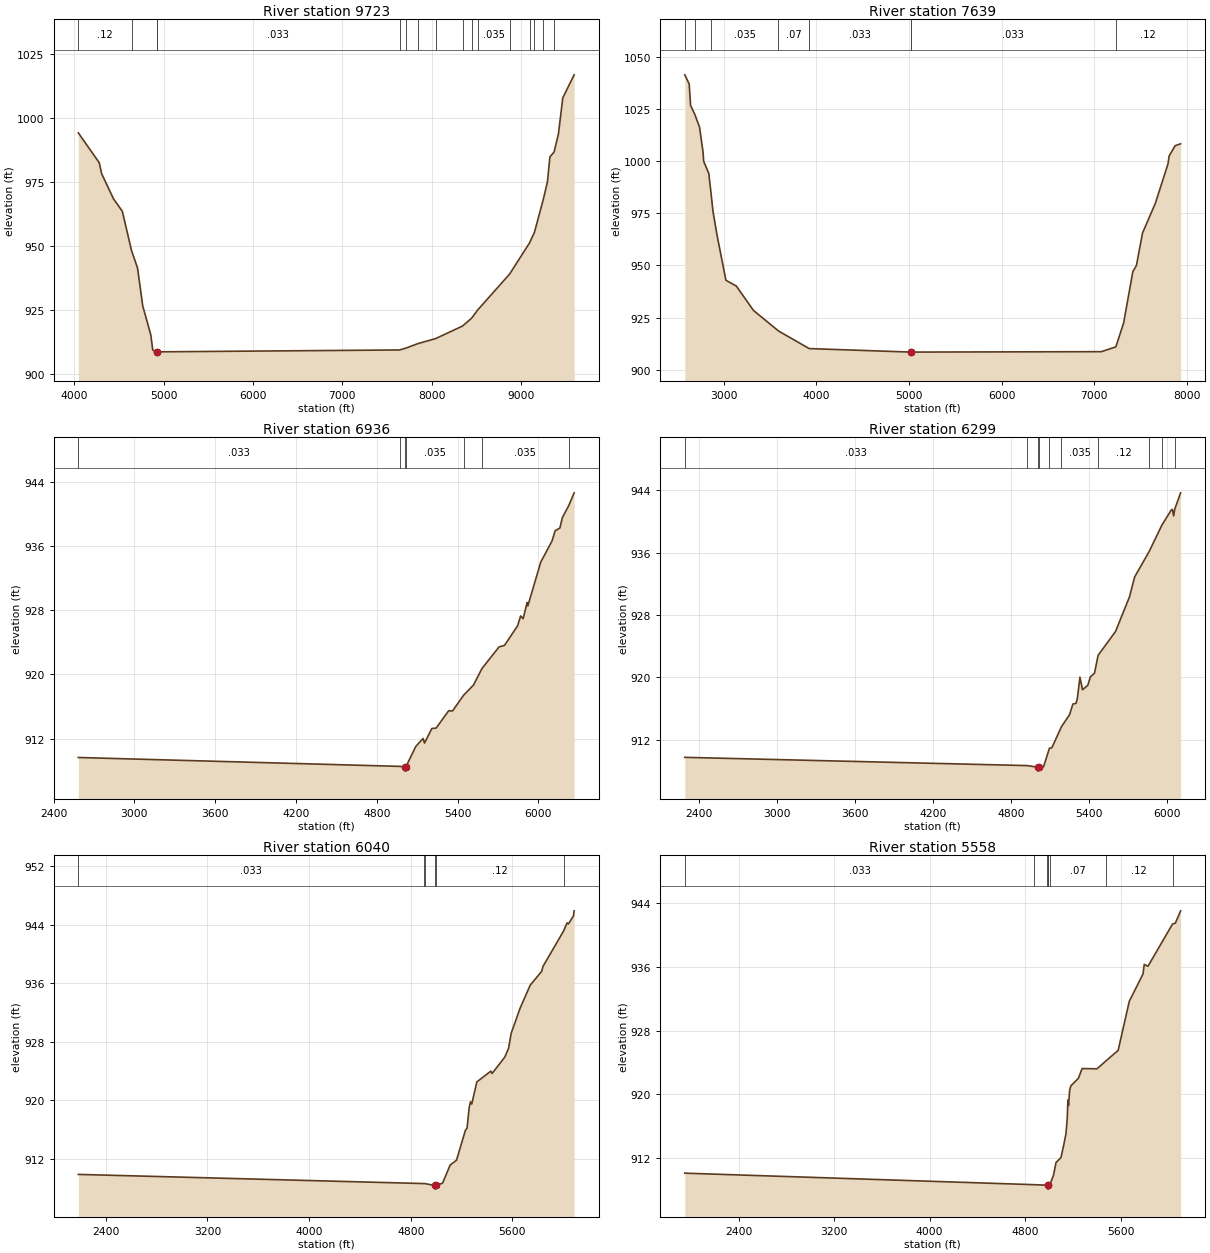
Type RM Length L Ch R = 1,9723,2084,2084,2084
BEGIN DESCRIPTION:
Stream0199_DS 14.0
END DESCRIPTION:
XS GIS Cut Line= 4
      2212602.66     13878328.60      2211756.72     13878774.58
      2210743.24     13880283.62      2210066.70     13882978.41
#Sta/Elev= 30
  4043.7  994.18  4277.7  982.53  4305.4  978.19  4437.5  968.39  4536.3  963.53
  4639.3  948.18  4706.9  941.32  4764.5  926.58  4855.0  915.21  4877.5  909.20
  4919.4  908.53  4919.7  908.03  4923.7  908.53  7641.8  909.27  7716.5  910.05
  7843.2  911.71  8044.5  913.71  8346.5  918.63  8447.2  921.68  8515.1  924.87
  8874.0  938.99  9096.2  951.12  9151.8  955.33  9252.5  968.44  9297.0  975.05
  9324.6  984.79  9371.7  986.72  9420.5  993.85  9469.0 1007.90  9596.2 1016.90
#Mann=16,-1,0
  4043.7    0.12       0  4639.3   0.033       0  4919.4   0.033       0
  4923.7   0.033       0  7641.8    0.12       0  7716.5    0.07       0
  7843.2    0.12       0  8044.5    0.07       0  8346.5   0.035       0
  8447.2    0.07       0  8515.1   0.035       0  8874.0    0.12       0
  9096.2    0.07       0  9151.8    0.12       0  9252.5   0.035       0
  9371.7    0.07       0
Bank Sta=4919.4,4923.7
Exp/Cntr=0.3,0.1

Type RM Length L Ch R = 1,7639,703,703,703
BEGIN DESCRIPTION:
Stream0199_DS 13.0
END DESCRIPTION:
XS GIS Cut Line= 4
      2209082.62     13881957.27      2210158.48     13879792.03
      2211040.91     13878688.14      2212493.69     13878251.91
#Sta/Elev= 30
  2582.2 1041.41  2629.4 1037.03  2644.9 1026.72  2689.4 1022.50  2741.1 1016.39
  2779.4 1004.23  2785.7  999.95  2841.0  994.15  2866.2  984.26  2885.8  976.10
  2930.6  964.37  3025.8  942.89  3137.8  940.14  3322.6  928.45  3592.5  918.60
  3923.8  910.14  5017.4  908.46  5017.7  907.96  5021.8  908.46  7075.3  908.66
  7231.8  910.97  7315.8  922.49  7414.9  947.09  7453.2  949.95  7519.3  965.58
  7656.7  979.71  7794.1  998.74  7806.2 1002.48  7870.6 1007.41  7930.1 1008.35
#Mann=8,-1,0
  2582.2   0.035       0  2689.4   0.063       0  2866.2   0.035       0
  3592.5    0.07       0  3923.8   0.033       0  5017.4   0.033       0
  5021.8   0.033       0  7231.8    0.12       0
Bank Sta=5017.4,5021.8
Exp/Cntr=0.3,0.1

Type RM Length L Ch R = 1,6936,637,637,637
BEGIN DESCRIPTION:
Stream0199_DS 12.0
END DESCRIPTION:
XS GIS Cut Line= 3
      2210900.01     13878099.98      2209575.00     13880125.00
      2209098.26     13881294.04
#Sta/Elev= 30
  2583.9  909.64  4975.2  908.53  5010.8  908.44  5011.2  907.94  5015.3  907.94
  5015.6  908.44  5090.3  911.02  5144.2  912.01  5155.1  911.44  5209.1  913.25
  5241.5  913.31  5334.1  915.46  5363.5  915.45  5444.7  917.39  5518.6  918.67
  5581.9  920.74  5708.5  923.43  5749.1  923.62  5846.3  926.06  5868.9  927.29
  5887.5  926.95  5917.0  928.96  5922.4  928.54  6018.5  934.01  6101.5  936.62
  6125.5  937.92  6160.4  938.25  6179.0  939.56  6225.8  941.03  6266.4  942.64
#Mann=7,-1,0
  2583.9   0.033       0  4975.2   0.035       0  5010.8   0.035       0
  5015.6   0.035       0  5444.7    0.07       0  5581.9   0.035       0
  6225.8   0.063       0
Bank Sta=5010.8,5015.6
Exp/Cntr=0.3,0.1

Type RM Length L Ch R = 1,6299,259,259,259
BEGIN DESCRIPTION:
Stream0199_DS 11.0
END DESCRIPTION:
XS GIS Cut Line= 3
      2210749.97     13878050.04      2209066.99     13880174.28
      2208999.28     13881278.48
#Sta/Elev= 30
  2289.2  909.73  4925.6  908.67  5007.7  908.46  5008.0  907.96  5012.1  907.96
  5012.5  908.46  5050.1  908.50  5096.1  910.91  5114.4  910.95  5188.6  913.67
  5250.5  915.20  5276.3  916.57  5300.6  916.66  5310.6  917.29  5330.7  920.02
  5350.7  918.41  5390.8  918.97  5410.8  920.05  5443.1  920.55  5470.1  922.82
  5605.0  925.90  5711.4  930.31  5751.5  932.88  5863.6  936.16  5962.0  939.56
  6032.0  941.45  6042.0  941.57  6052.0  940.73  6060.4  941.60  6105.6  943.69
#Mann=10,-1,0
  2289.2   0.033       0  4925.6   0.035       0  5007.7   0.035       0
  5012.5   0.035       0  5096.1    0.12       0  5188.6   0.035       0
  5470.1    0.12       0  5863.6   0.035       0  5962.0   0.063       0
  6060.4   0.035       0
Bank Sta=5007.7,5012.5
Exp/Cntr=0.3,0.1

Type RM Length L Ch R = 1,6040,482,482,482
BEGIN DESCRIPTION:
Stream0199_DS 10.0
END DESCRIPTION:
XS GIS Cut Line= 3
      2210549.97     13878000.04      2208825.00     13880225.00
      2208802.51     13881310.55
#Sta/Elev= 30
  2184.6  909.90  4900.9  908.65  4909.2  908.65  4990.3  908.39  4990.6  907.89
  4994.7  907.89  4995.1  908.39  5049.9  908.69  5109.9  911.17  5159.9  911.83
  5230.0  915.91  5243.1  916.23  5260.0  919.05  5270.0  919.80  5280.0  919.50
  5320.0  922.52  5430.0  923.99  5440.0  923.67  5540.0  925.91  5570.0  927.13
  5590.0  929.15  5660.1  932.57  5740.1  935.73  5830.1  937.61  5840.1  938.27
  6002.5  943.12  6030.1  944.23  6040.1  944.07  6080.1  945.17  6085.7  945.87
#Mann=6,-1,0
  2184.6   0.033       0  4900.9   0.035       0  4909.2    0.12       0
  4990.3    0.05       0  4995.1    0.12       0  6002.5   0.063       0
Bank Sta=4990.3,4995.1
Exp/Cntr=0.3,0.1

Type RM Length L Ch R = 1,5558,467,467,467
BEGIN DESCRIPTION:
Stream0199_DS 9.0
END DESCRIPTION:
XS GIS Cut Line= 3
      2210400.02     13877949.98      2208375.00     13880225.00
      2208680.48     13881287.74
#Sta/Elev= 30
  1950.3  910.04  4875.3  908.59  4981.5  908.53  4990.1  908.53  4990.5  908.03
  4994.9  908.03  4995.3  908.53  5005.5  908.53  5037.6  909.79  5058.5  911.38
  5100.1  912.01  5124.4  913.69  5141.7  914.99  5152.1  916.82  5158.1  919.26
  5163.3  918.56  5172.9  920.52  5183.3  921.04  5245.7  921.98  5277.0  923.21
  5401.8  923.18  5477.1  924.18  5578.7  925.50  5672.3  931.69  5786.8  935.12
  5797.2  936.32  5828.4  936.09  6034.6  941.42  6057.3  941.51  6101.8  943.07
#Mann=8,-1,0
  1950.3   0.033       0  4875.3    0.12       0  4981.5   0.033       0
  4990.1   0.033       0  4995.3   0.033       0  5005.5    0.07       0
  5477.1    0.12       0  6034.6   0.063       0
Bank Sta=4990.1,4995.3
Exp/Cntr=0.3,0.1

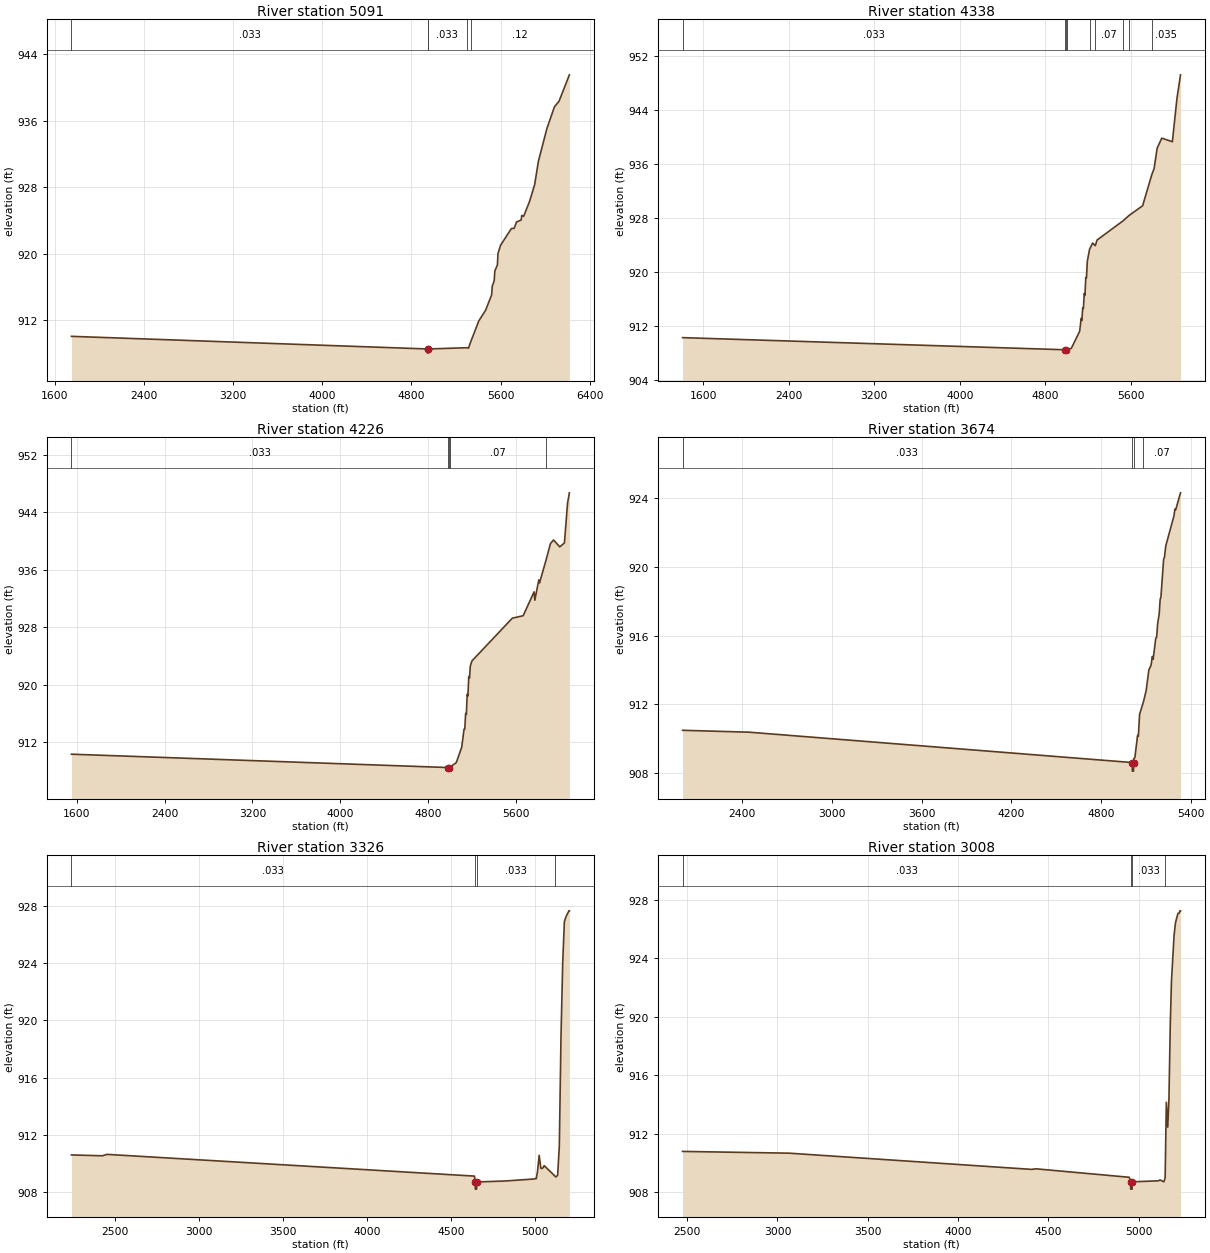
Type RM Length L Ch R = 1,5091,753,753,753
BEGIN DESCRIPTION:
Stream0199_DS 8.0
END DESCRIPTION:
XS GIS Cut Line= 3
      2210249.98     13877900.02      2207975.00     13880225.00
      2208476.99     13881328.53
#Sta/Elev= 30
  1751.5  910.09  4945.2  908.57  4945.6  908.07  4950.1  908.07  4950.5  908.57
  5294.5  908.72  5312.0  908.67  5331.5  909.42  5404.1  911.94  5465.8  913.24
  5519.4  915.08  5524.9  916.11  5542.5  916.78  5548.0  917.95  5571.0  918.68
  5576.5  920.06  5599.6  921.05  5697.3  923.07  5720.4  923.07  5743.4  923.86
  5784.1  924.08  5789.6  924.63  5806.3  924.53  5858.7  926.29  5904.9  928.33
  5938.9  931.16  6015.1  935.09  6082.8  937.71  6123.4  938.36  6216.7  941.55
#Mann=5,-1,0
  1751.5   0.033       0  4945.2   0.033       0  4950.5   0.033       0
  5294.5    0.07       0  5331.5    0.12       0
Bank Sta=4945.2,4950.5
Exp/Cntr=0.3,0.1

Type RM Length L Ch R = 1,4338,112,112,112
BEGIN DESCRIPTION:
Stream0199_DS 7.0
END DESCRIPTION:
XS GIS Cut Line= 3
      2210150.01     13877849.99      2207339.56     13880080.53
      2206509.22     13880756.93
#Sta/Elev= 30
  1405.7  910.23  4982.2  908.43  4982.7  907.93  4991.0  908.43  4999.9  908.46
  5042.6  908.63  5120.8  911.16  5135.2  913.08  5141.7  912.78  5149.6  914.67
  5156.0  914.55  5163.9  916.78  5170.4  916.50  5178.3  919.15  5184.8  919.11
  5192.7  921.57  5213.7  923.34  5242.2  924.28  5267.5  923.88  5283.9  924.72
  5529.4  927.60  5580.2  928.33  5710.4  929.82  5797.0  934.48  5817.4  935.31
  5846.2  938.36  5889.3  939.85  5988.4  939.32  6031.4  945.74  6064.7  949.25
#Mann=9,-1,0
  1405.7   0.033       0  4982.2    0.05       0  4991.0   0.033       0
  4999.9    0.07       0  5213.7    0.12       0  5267.5    0.07       0
  5529.4    0.12       0  5580.2    0.07       0  5797.0   0.035       0
Bank Sta=4982.2,4991
Exp/Cntr=0.3,0.1

Type RM Length L Ch R = 1,4226,552,552,552
BEGIN DESCRIPTION:
Stream0199_DS 6.0
END DESCRIPTION:
XS GIS Cut Line= 3
      2209999.96     13877800.03      2207325.00     13879975.00
      2206507.21     13880690.79
#Sta/Elev= 30
  1552.3  910.29  4981.9  908.43  4982.4  907.93  4990.7  908.43  4995.2  908.45
  5056.4  909.11  5106.2  911.27  5127.6  913.80  5134.2  913.77  5141.8  915.96
  5148.4  915.83  5156.0  918.64  5162.7  918.40  5170.3  921.11  5176.9  920.90
  5184.5  922.57  5198.7  923.28  5567.0  929.25  5665.7  929.59  5765.3  932.92
  5772.0  931.76  5808.1  934.58  5814.7  934.16  5873.5  937.32  5914.4  939.65
  5942.8  940.15  5998.8  939.19  6041.5  939.74  6070.0  945.30  6086.7  946.72
#Mann=5,-1,0
  1552.3   0.033       0  4981.9    0.05       0  4990.7   0.033       0
  4995.2    0.07       0  5873.5   0.035       0
Bank Sta=4981.9,4990.7
Exp/Cntr=0.3,0.1

Type RM Length L Ch R = 1,3674,348,348,348
BEGIN DESCRIPTION:
Stream0199_DS 5.0
END DESCRIPTION:
XS GIS Cut Line= 3
      2209850.04     13877749.97      2207360.40     13879448.59
      2207075.04     13879574.98
#Sta/Elev= 30
  2004.0  910.48  2447.6  910.37  5007.7  908.60  5008.2  908.10  5016.0  908.10
  5016.5  908.60  5017.9  908.83  5025.3  908.89  5043.1  910.18  5048.6  910.13
  5056.6  911.41  5082.5  912.14  5100.7  912.80  5118.5  914.00  5133.2  914.27
  5141.7  914.78  5147.2  914.62  5165.0  915.86  5170.5  915.89  5176.9  916.67
  5187.9  917.28  5193.8  918.09  5199.3  918.26  5217.1  920.44  5222.5  920.55
  5231.6  921.23  5286.3  922.98  5292.4  923.37  5297.9  923.33  5330.0  924.32
#Mann=4,-1,0
  2004.0   0.033       0  5007.7   0.033       0  5016.5   0.033       0
  5082.5    0.07       0
Bank Sta=5007.7,5016.5
Exp/Cntr=0.3,0.1

Type RM Length L Ch R = 1,3326,318,318,318
BEGIN DESCRIPTION:
Stream0199_DS 4.0
END DESCRIPTION:
XS GIS Cut Line= 4
      2209699.96     13877650.03      2207550.21     13879086.32
      2207375.00     13879125.00      2207175.04     13879125.00
#Sta/Elev= 30
  2240.9  910.60  2427.3  910.54  2436.1  910.59  2442.1  910.59  2451.1  910.64
  4640.6  909.12  4645.1  908.71  4645.6  908.21  4653.5  908.21  4654.0  908.71
  4826.3  908.78  4995.5  908.92  5003.2  908.94  5005.7  908.94  5008.2  908.94
  5015.7  909.42  5025.7  910.57  5035.7  909.67  5045.7  909.66  5055.7  909.85
  5119.2  909.13  5125.7  909.06  5135.7  909.18  5145.7  911.22  5155.7  918.85
  5165.7  923.96  5175.7  926.90  5185.7  927.26  5203.2  927.66  5205.7  927.66
#Mann=4,-1,0
  2240.9   0.033       0  4645.1   0.033       0  4654.0   0.033       0
  5119.2    0.07       0
Bank Sta=4645.1,4654
Exp/Cntr=0.3,0.1

Type RM Length L Ch R = 1,3008,572,572,572
BEGIN DESCRIPTION:
Stream0199_DS 3.0
END DESCRIPTION:
XS GIS Cut Line= 3
      2209500.03     13877599.98      2207350.02     13878924.60
      2207174.97     13879075.02
#Sta/Elev= 26
  2474.7  910.80  3063.9  910.68  4406.9  909.57  4430.4  909.61  4947.2  909.03
  4954.5  908.72  4955.0  908.22  4962.9  908.22  4963.4  908.72  5110.6  908.79
  5117.2  908.85  5138.5  908.72  5145.7  908.99  5146.4  909.54  5152.3  914.16
  5160.0  912.46  5166.6  914.31  5174.2  919.52  5180.8  922.48  5195.1  925.57
  5202.8  926.42  5209.4  926.76  5217.0  927.09  5223.6  927.10  5227.5  927.26
  5230.8  927.26
#Mann=4,-1,0
  2474.7   0.033       0  4954.5   0.033       0  4963.4   0.033       0
  5146.4    0.07       0
Bank Sta=4954.5,4963.4
Exp/Cntr=0.3,0.1

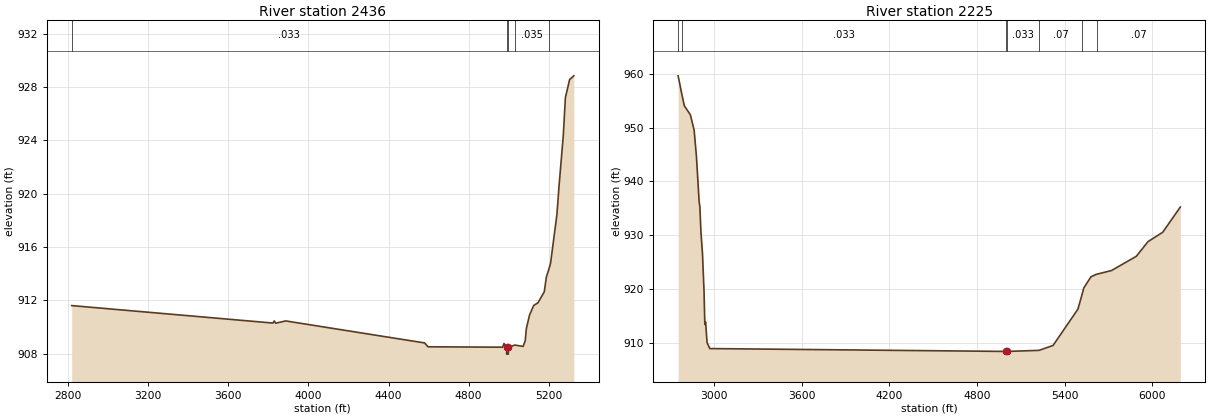
Type RM Length L Ch R = 1,2436,211,211,211
BEGIN DESCRIPTION:
Stream0199_DS 2.0
END DESCRIPTION:
XS GIS Cut Line= 4
      2208250.03     13877149.97      2207026.99     13878445.04
      2206875.00     13878825.00      2206975.01     13879125.04
#Sta/Elev= 30
  2818.2  911.61  3822.8  910.30  3829.6  910.46  3836.9  910.29  3886.3  910.46
  4579.7  908.81  4597.3  908.52  4969.7  908.49  4976.4  908.77  4989.3  908.47
  4989.8  907.97  4998.0  907.97  4998.5  908.47  5029.7  908.65  5072.0  908.55
  5082.5  908.98  5087.8  909.87  5103.6  910.89  5124.7  911.62  5145.8  911.82
  5177.4  912.64  5187.9  913.75  5200.6  914.35  5209.0  914.80  5240.6  918.45
  5251.2  920.59  5272.3  924.35  5282.8  927.20  5303.9  928.56  5325.0  928.84
#Mann=5,-1,0
  2818.2   0.033       0  4989.3   0.033       0  4998.5   0.033       0
  5029.7   0.035       0  5200.6    0.07       0
Bank Sta=4989.3,4998.5
Exp/Cntr=0.3,0.1

Type RM Length L Ch R = 1,2225,0,0,0
BEGIN DESCRIPTION:
Stream0199_DS 1.0
END DESCRIPTION:
XS GIS Cut Line= 3
      2207289.89     13876614.40      2206680.88     13878765.55
      2206680.89     13879965.55
#Sta/Elev= 30
  2754.8  959.59  2780.1  956.22  2797.0  954.05  2838.6  952.37  2864.5  949.49
  2880.1  944.68  2898.5  936.32  2903.7  935.30  2911.3  930.47  2921.7  926.55
  2932.1  919.66  2937.6  913.47  2942.8  913.92  2952.9  910.11  2971.6  909.01
  4995.3  908.48  4995.8  907.98  5004.6  908.48  5224.3  908.68  5319.9  909.59
  5489.9  916.31  5519.5  919.15  5529.9  920.24  5579.9  922.34  5617.8  922.79
  5719.9  923.48  5889.9  926.13  5969.9  928.85  6069.9  930.57  6190.5  935.25
#Mann=7,-1,0
  2754.8    0.12       0  2780.1   0.033       0  4995.3   0.033       0
  5004.6   0.033       0  5224.3    0.07       0  5519.5   0.035       0
  5617.8    0.07       0
Bank Sta=4995.3,5004.6
Exp/Cntr=0.3,0.1

Chan Stop Cuts=-1