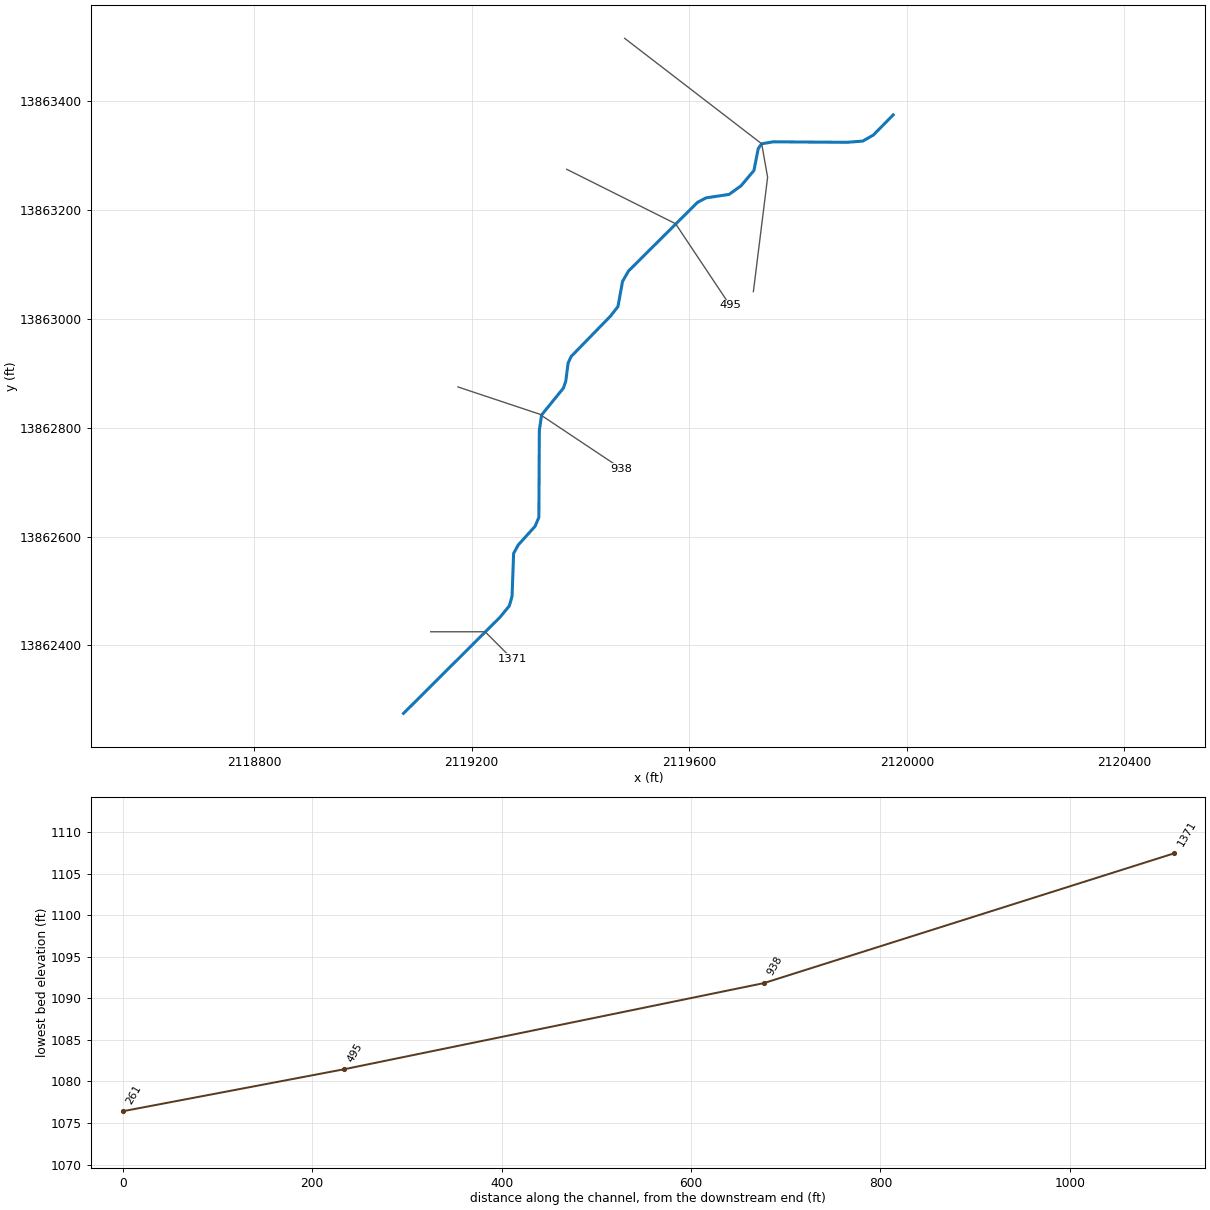
--- Stream0205_DS.prj (project) ---

Proj Title=Stream0205_DS Base Level Engineering
Current Plan=p01
Default Exp/Contr=0.3,0.1
English Units
Geom File=g01
Flow File=f01
Plan File=p01
BEGIN DESCRIPTION:
Stream0205_DS
END DESCRIPTION:

--- Stream0205_DS.p01 (plan) ---

Plan Title=Multiple Run
Short Identifier=Multiple
Geom File=g01
Flow File=f01
Subcritical Flow
K Sum by GR= 0
Std Step Tol= 0.01
Critical Tol= 0.01
Num of Std Step Trials= 20
Max Error Tol= 0.3
Flow Tol Ratio= 0.001
Split Flow NTrial= 30
Split Flow Tol= 0.02
Split Flow Ratio= 0.02
Log Output Level= 0
Friction Slope Method= 1
Unsteady Friction Slope Method= 2
Unsteady Bridges Friction Slope Method= 1
Parabolic Critical Depth
Global Vel Dist=  1 , 1 , 1
Global Log Level= 0
CheckData=True
Encroach Param= -1, 0, 0, 0
BEGIN DESCRIPTION:
Multiple Run
END DESCRIPTION:

--- Stream0205_DS.f01 (steady flow) ---

Flow Title=Multiple
Number of Profiles=7
Profile Names=10-year,25-year,50-year,1pct_min,100-year,1pct_plu,500-year
River Rch & RM= Stream0205_DS,Reach-1,1371
     200     302     389     245     489     977     760
Boundary for River Rch & Prof#=Stream0205_DS,Reach-1,1
Up Type=0
Dn Type=3
Dn Slope=0.005
Boundary for River Rch & Prof#=Stream0205_DS,Reach-1,2
Up Type=0
Dn Type=3
Dn Slope=0.005
Boundary for River Rch & Prof#=Stream0205_DS,Reach-1,3
Up Type=0
Dn Type=3
Dn Slope=0.005
Boundary for River Rch & Prof#=Stream0205_DS,Reach-1,4
Up Type=0
Dn Type=3
Dn Slope=0.005
Boundary for River Rch & Prof#=Stream0205_DS,Reach-1,5
Up Type=0
Dn Type=3
Dn Slope=0.005
Boundary for River Rch & Prof#=Stream0205_DS,Reach-1,6
Up Type=0
Dn Type=3
Dn Slope=0.005
Boundary for River Rch & Prof#=Stream0205_DS,Reach-1,7
Up Type=0
Dn Type=3
Dn Slope=0.005

--- Stream0205_DS.g01 (geometry) ---

Geom Title=Existing Conditions

River Reach=Stream0205_DS,Reach-1
Reach XY= 30
      2119075.00     13862275.00      2119252.12     13862451.48
      2119269.48     13862472.57      2119274.48     13862490.22
      2119277.36     13862569.02      2119285.90     13862584.63
      2119316.86     13862618.94      2119323.78     13862635.50
      2119324.64     13862795.15      2119328.75     13862823.45
      2119368.86     13862872.83      2119373.28     13862885.71
      2119377.50     13862918.96      2119383.16     13862931.05
      2119455.17     13863004.93      2119469.13     13863022.72
      2119477.53     13863068.95      2119488.63     13863088.21
      2119615.34     13863214.22      2119631.08     13863222.45
      2119673.55     13863228.92      2119695.43     13863244.74
      2119719.08     13863272.86      2119727.00     13863313.27
      2119733.31     13863321.91      2119754.57     13863325.53
      2119890.16     13863324.60      2119919.21     13863326.89
      2119938.50     13863337.92      2119975.00     13863375.00

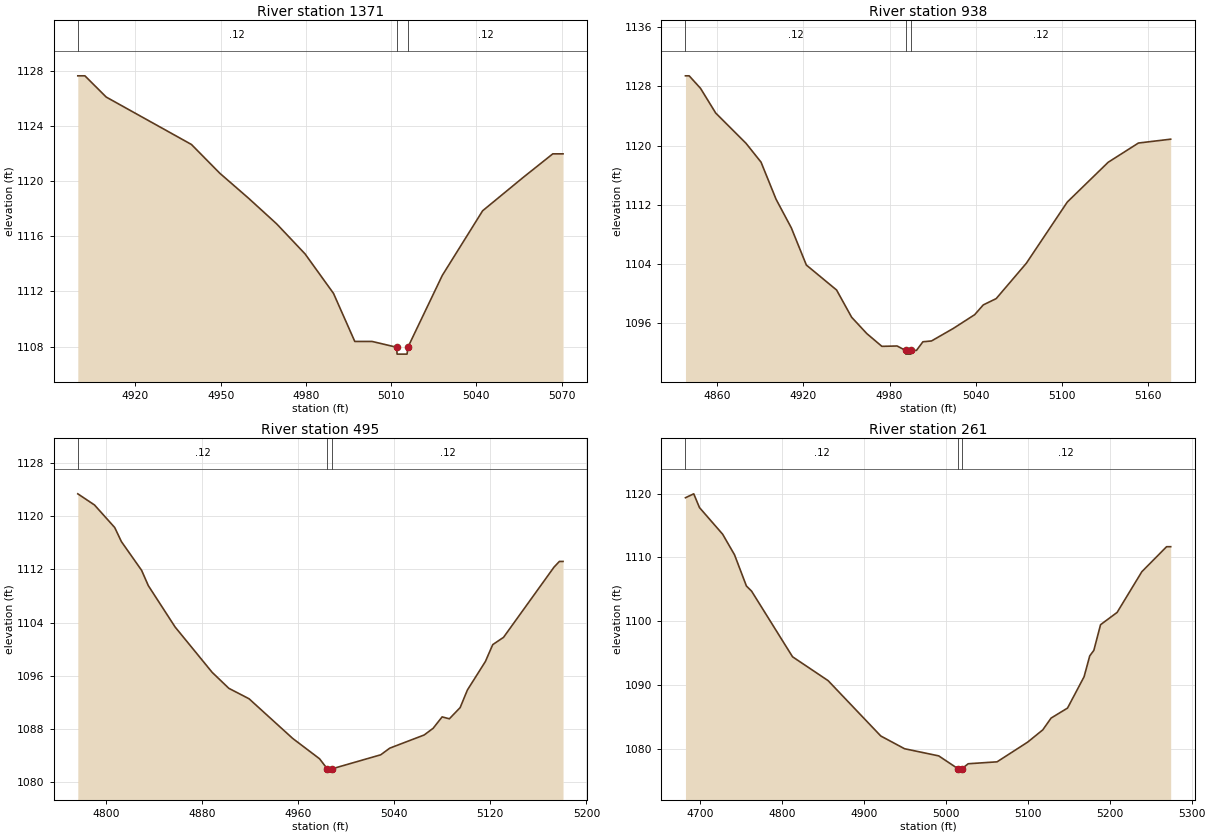
Type RM Length L Ch R = 1,1371,433,433,433
BEGIN DESCRIPTION:
Stream0205_DS 3.0
END DESCRIPTION:
XS GIS Cut Line= 3
      2119124.95     13862425.00      2119225.00     13862425.00
      2119275.03     13862374.97
#Sta/Elev= 21
  4899.7 1127.64  4902.2 1127.64  4909.7 1126.10  4939.7 1122.66  4949.7 1120.57
  4959.7 1118.78  4969.7 1116.90  4979.7 1114.72  4989.7 1111.86  4997.2 1108.37
  4999.7 1108.37  5003.3 1108.37  5011.9 1107.95  5012.1 1107.45  5015.6 1107.45
  5015.9 1107.95  5028.0 1113.16  5042.2 1117.85  5056.3 1120.24  5066.9 1121.98
  5070.5 1121.98
#Mann=3,-1,0
  4899.7    0.12       0  5011.9    0.05       0  5015.9    0.12       0
Bank Sta=5011.9,5015.9
Exp/Cntr=0.3,0.1

Type RM Length L Ch R = 1,938,443,443,443
BEGIN DESCRIPTION:
Stream0205_DS 2.0
END DESCRIPTION:
XS GIS Cut Line= 3
      2119175.00     13862875.00      2119325.00     13862825.00
      2119475.01     13862724.99
#Sta/Elev= 30
  4837.7 1129.44  4840.3 1129.44  4848.2 1127.75  4858.8 1124.41  4879.9 1120.33
  4890.4 1117.78  4900.9 1112.76  4911.5 1108.91  4922.0 1103.88  4943.1 1100.50
  4953.6 1096.82  4964.2 1094.61  4974.7 1092.89  4985.3 1092.94  4991.2 1092.34
  4991.4 1091.84  4994.9 1091.84  4995.2 1092.34  4998.8 1092.34  5003.3 1093.51
  5009.3 1093.62  5024.4 1095.30  5039.4 1097.17  5045.4 1098.49  5054.4 1099.34
  5075.4 1104.11  5104.0 1112.39  5132.5 1117.76  5153.6 1120.36  5176.1 1120.88
#Mann=3,-1,0
  4837.7    0.12       0  4991.2    0.05       0  4995.2    0.12       0
Bank Sta=4991.2,4995.2
Exp/Cntr=0.3,0.1

Type RM Length L Ch R = 1,495,234,234,234
BEGIN DESCRIPTION:
Stream0205_DS 1.0
END DESCRIPTION:
XS GIS Cut Line= 3
      2119375.03     13863274.98      2119575.00     13863175.00
      2119674.97     13863025.04
#Sta/Elev= 30
  4776.7 1123.39  4790.6 1121.71  4807.4 1118.32  4813.0 1116.19  4829.8 1111.87
  4835.4 1109.56  4857.7 1103.33  4888.5 1096.51  4902.4 1094.10  4919.2 1092.53
  4955.5 1086.56  4977.9 1083.49  4984.3 1081.98  4984.5 1081.48  4988.0 1081.48
  4988.3 1081.98  5028.8 1084.09  5036.3 1085.09  5064.9 1087.07  5072.4 1088.08
  5079.9 1089.80  5085.9 1089.51  5094.9 1091.20  5100.9 1093.84  5115.9 1098.14
  5122.0 1100.68  5131.0 1101.78  5173.0 1112.35  5177.5 1113.21  5180.5 1113.21
#Mann=3,-1,0
  4776.7    0.12       0  4984.3    0.05       0  4988.3    0.12       0
Bank Sta=4984.3,4988.3
Exp/Cntr=0.3,0.1

Type RM Length L Ch R = 1,261,0,0,0
BEGIN DESCRIPTION:
Stream0205_DS 0.0
END DESCRIPTION:
XS GIS Cut Line= 4
      2119481.45     13863515.71      2119733.31     13863321.91
      2119744.20     13863260.34      2119718.02     13863050.08
#Sta/Elev= 30
  4682.2 1119.34  4692.3 1119.95  4699.3 1117.80  4727.6 1113.63  4742.1 1110.41
  4756.6 1105.53  4762.9 1104.73  4812.9 1094.46  4856.3 1090.73  4920.6 1082.07
  4949.6 1080.08  4991.3 1078.96  5015.2 1076.92  5015.4 1076.42  5018.9 1076.42
  5019.2 1076.92  5027.3 1077.73  5062.5 1078.03  5099.8 1081.11  5118.3 1083.03
  5128.4 1084.87  5148.5 1086.44  5168.7 1091.34  5175.6 1094.60  5180.6 1095.46
  5188.8 1099.48  5209.0 1101.40  5239.2 1107.77  5269.4 1111.68  5274.4 1111.68
#Mann=3,-1,0
  4682.2    0.12       0  5015.2    0.05       0  5019.2    0.12       0
Bank Sta=5015.2,5019.2
Exp/Cntr=0.3,0.1

Chan Stop Cuts=-1