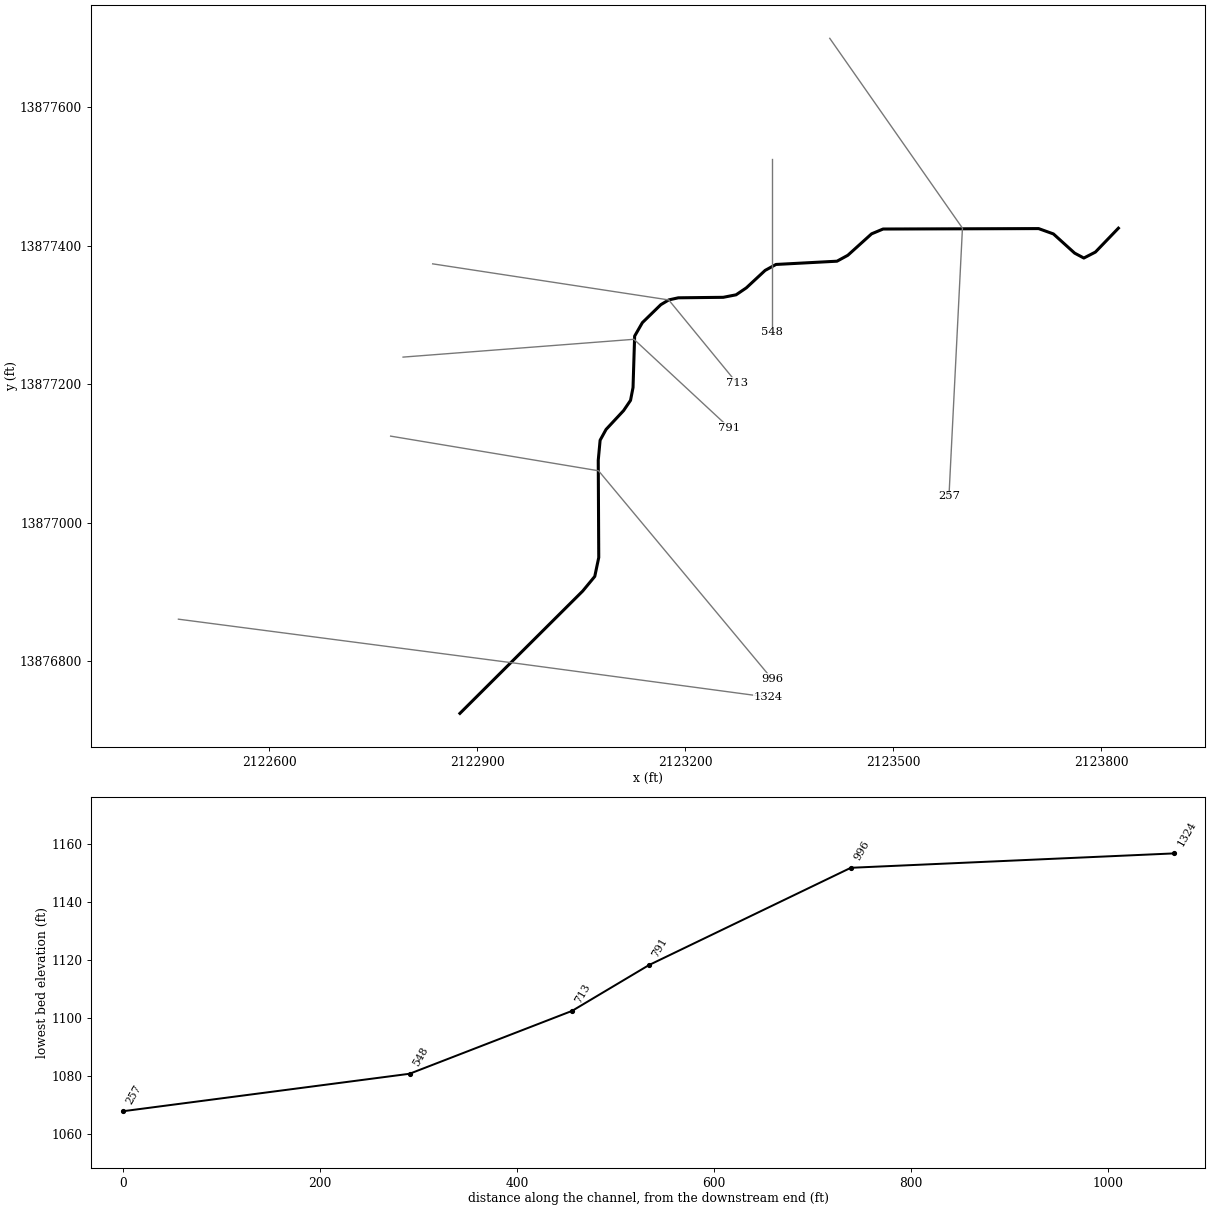
--- Stream0210_DS.prj (project) ---

Proj Title=Stream0210_DS Base Level Engineering
Current Plan=p01
Default Exp/Contr=0.3,0.1
English Units
Geom File=g01
Flow File=f01
Plan File=p01
BEGIN DESCRIPTION:
Stream0210_DS
END DESCRIPTION:

--- Stream0210_DS.p01 (plan) ---

Plan Title=Multiple Run
Short Identifier=Multiple
Geom File=g01
Flow File=f01
Subcritical Flow
K Sum by GR= 0
Std Step Tol= 0.01
Critical Tol= 0.01
Num of Std Step Trials= 20
Max Error Tol= 0.3
Flow Tol Ratio= 0.001
Split Flow NTrial= 30
Split Flow Tol= 0.02
Split Flow Ratio= 0.02
Log Output Level= 0
Friction Slope Method= 1
Unsteady Friction Slope Method= 2
Unsteady Bridges Friction Slope Method= 1
Parabolic Critical Depth
Global Vel Dist=  1 , 1 , 1
Global Log Level= 0
CheckData=True
Encroach Param= -1, 0, 0, 0
BEGIN DESCRIPTION:
Multiple Run
END DESCRIPTION:

--- Stream0210_DS.f01 (steady flow) ---

Flow Title=Multiple
Number of Profiles=7
Profile Names=10-year,25-year,50-year,1pct_min,100-year,1pct_plu,500-year
River Rch & RM= Stream0210_DS,Reach-1,1324
     570     933    1268     838    1673    3338    2872
Boundary for River Rch & Prof#=Stream0210_DS,Reach-1,1
Up Type=0
Dn Type=3
Dn Slope=0.005
Boundary for River Rch & Prof#=Stream0210_DS,Reach-1,2
Up Type=0
Dn Type=3
Dn Slope=0.005
Boundary for River Rch & Prof#=Stream0210_DS,Reach-1,3
Up Type=0
Dn Type=3
Dn Slope=0.005
Boundary for River Rch & Prof#=Stream0210_DS,Reach-1,4
Up Type=0
Dn Type=3
Dn Slope=0.005
Boundary for River Rch & Prof#=Stream0210_DS,Reach-1,5
Up Type=0
Dn Type=3
Dn Slope=0.005
Boundary for River Rch & Prof#=Stream0210_DS,Reach-1,6
Up Type=0
Dn Type=3
Dn Slope=0.005
Boundary for River Rch & Prof#=Stream0210_DS,Reach-1,7
Up Type=0
Dn Type=3
Dn Slope=0.005

--- Stream0210_DS.g01 (geometry) ---

Geom Title=Existing Conditions

River Reach=Stream0210_DS,Reach-1
Reach XY= 30
      2122875.00     13876725.00      2123052.14     13876901.47
      2123069.54     13876922.55      2123075.29     13876949.88
      2123074.57     13877090.18      2123077.26     13877119.06
      2123085.85     13877134.65      2123111.17     13877161.87
      2123121.14     13877176.60      2123124.75     13877195.11
      2123127.07     13877269.31      2123138.23     13877288.72
      2123164.84     13877314.64      2123176.25     13877321.49
      2123190.08     13877324.54      2123254.89     13877325.25
      2123273.40     13877328.86      2123288.13     13877338.82
      2123315.37     13877364.11      2123330.97     13877372.65
      2123419.02     13877377.36      2123434.63     13877385.89
      2123468.94     13877416.86      2123485.50     13877423.78
      2123709.85     13877424.40      2123731.22     13877416.71
      2123761.89     13877388.97      2123775.14     13877381.91
      2123791.84     13877390.54      2123825.00     13877425.00

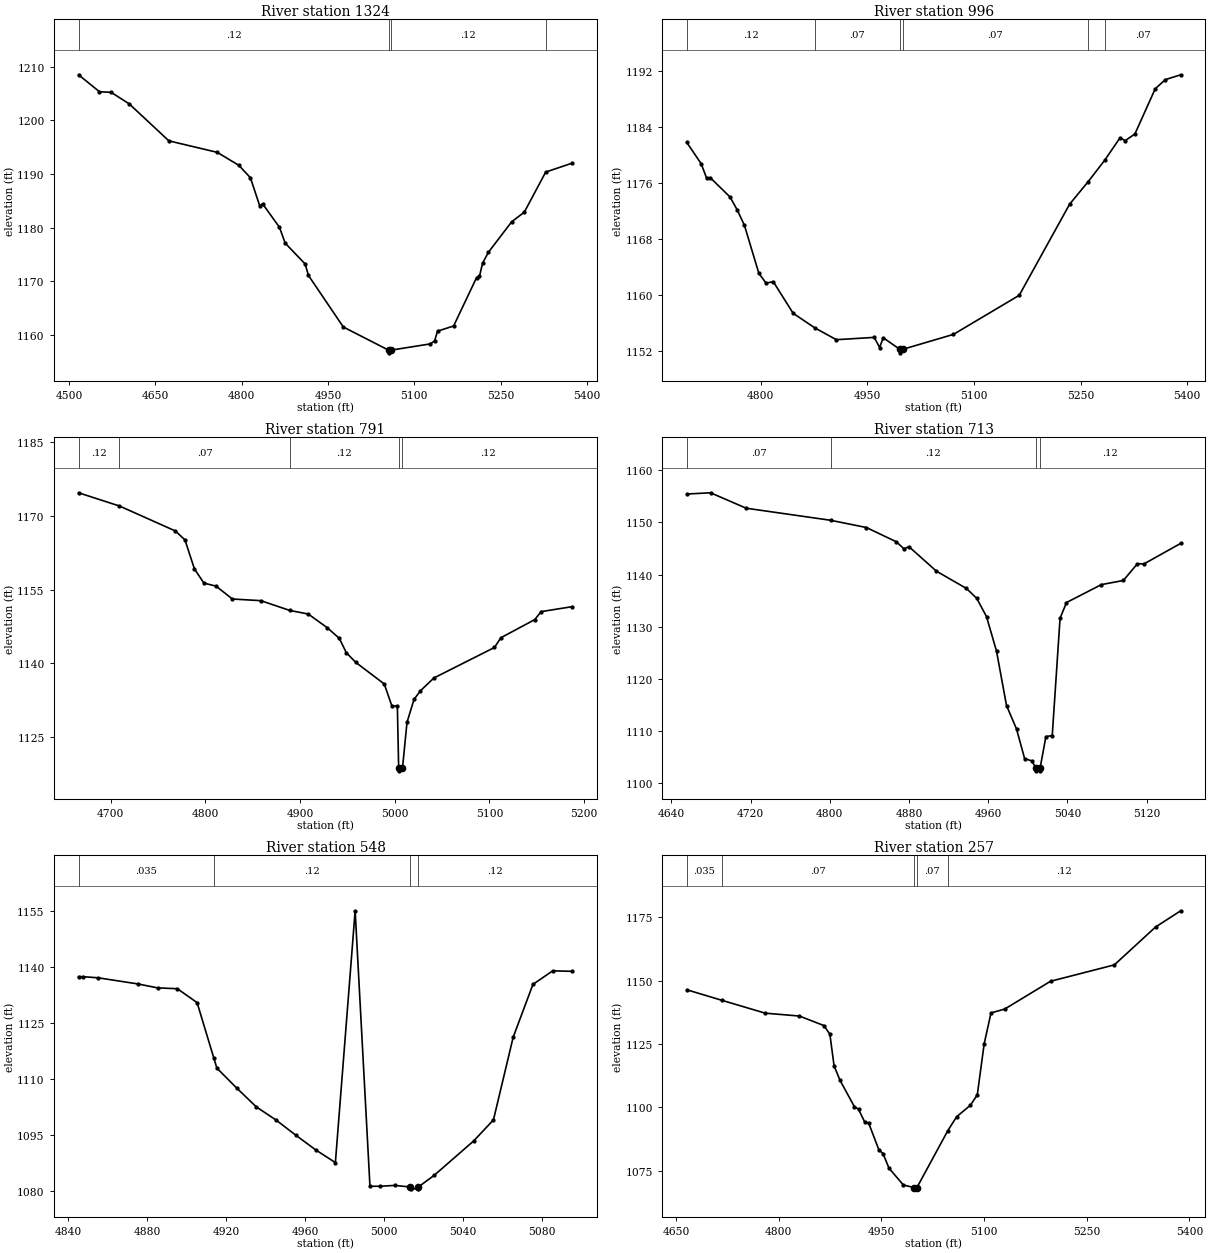
Type RM Length L Ch R = 1,1324,328,328,328
BEGIN DESCRIPTION:
Stream0210_DS 6.0
END DESCRIPTION:
XS GIS Cut Line= 3
      2122468.89     13876860.90      2122957.14     13876797.12
      2123319.68     13876748.40
#Sta/Elev= 30
  4516.5 1208.51  4552.9 1205.34  4573.1 1205.24  4604.5 1203.09  4673.4 1196.19
  4757.4 1194.05  4795.0 1191.63  4815.1 1189.31  4831.3 1184.07  4836.3 1184.45
  4865.6 1180.07  4875.6 1177.11  4910.2 1173.23  4916.0 1171.09  4976.5 1161.48
  5055.2 1157.16  5055.4 1156.66  5059.2 1157.16  5127.8 1158.33  5135.2 1158.89
  5140.2 1160.70  5168.2 1161.67  5208.0 1170.67  5213.1 1170.92  5218.6 1173.40
  5228.7 1175.42  5269.1 1181.10  5291.0 1182.89  5328.2 1190.37  5374.7 1192.05
#Mann=4,-1,0
  4516.5    0.12       0  5055.2    0.05       0  5059.2    0.12       0
  5328.2    0.07       0
Bank Sta=5055.2,5059.2
Exp/Cntr=0.3,0.1

Type RM Length L Ch R = 1,996,205,205,205
BEGIN DESCRIPTION:
Stream0210_DS 5.0
END DESCRIPTION:
XS GIS Cut Line= 3
      2122775.03     13877124.99      2123075.00     13877075.00
      2123324.99     13876775.01
#Sta/Elev= 30
  4696.3 1181.79  4716.5 1178.75  4724.1 1176.70  4729.2 1176.76  4757.1 1173.99
  4767.2 1172.14  4777.4 1169.92  4797.6 1163.08  4807.8 1161.67  4817.9 1161.88
  4845.8 1157.36  4876.3 1155.27  4906.6 1153.58  4959.9 1153.91  4967.5 1152.46
  4972.5 1153.86  4995.9 1152.20  4996.1 1151.70  4999.9 1152.20  5071.3 1154.34
  5163.8 1159.93  5234.7 1172.97  5260.5 1176.15  5284.1 1179.26  5305.7 1182.48
  5312.8 1182.04  5326.5 1183.01  5355.1 1189.48  5369.4 1190.78  5390.9 1191.47
#Mann=6,-1,0
  4696.3    0.12       0  4876.3    0.07       0  4995.9    0.05       0
  4999.9    0.07       0  5260.5    0.12       0  5284.1    0.07       0
Bank Sta=4995.9,4999.9
Exp/Cntr=0.3,0.1

Type RM Length L Ch R = 1,791,78,78,78
BEGIN DESCRIPTION:
Stream0210_DS 4.0
END DESCRIPTION:
XS GIS Cut Line= 3
      2122792.98     13877238.99      2123126.09     13877264.69
      2123263.65     13877136.98
#Sta/Elev= 30
  4665.9 1174.72  4709.1 1172.03  4768.2 1166.95  4778.3 1165.14  4788.3 1159.24
  4798.3 1156.35  4811.2 1155.72  4828.4 1153.11  4858.5 1152.77  4888.9 1150.79
  4908.6 1150.05  4928.7 1147.26  4941.4 1145.10  4948.8 1142.18  4958.8 1140.21
  4988.9 1135.82  4996.9 1131.35  5002.7 1131.35  5004.1 1118.65  5004.4 1118.15
  5008.1 1118.65  5012.9 1128.02  5020.3 1132.68  5027.1 1134.44  5041.3 1137.04
  5105.3 1143.25  5112.1 1145.23  5147.8 1148.91  5154.6 1150.54  5187.7 1151.56
#Mann=5,-1,0
  4665.9    0.12       0  4709.1    0.07       0  4888.9    0.12       0
  5004.1    0.05       0  5008.1    0.12       0
Bank Sta=5004.1,5008.1
Exp/Cntr=0.3,0.1

Type RM Length L Ch R = 1,713,165,165,165
BEGIN DESCRIPTION:
Stream0210_DS 3.0
END DESCRIPTION:
XS GIS Cut Line= 3
      2122835.71     13877373.53      2123176.25     13877321.49
      2123274.22     13877202.02
#Sta/Elev= 30
  4655.5 1155.45  4679.5 1155.69  4715.5 1152.73  4800.7 1150.42  4836.9 1149.03
  4867.2 1146.29  4874.9 1144.94  4879.9 1145.36  4907.7 1140.66  4938.0 1137.34
  4948.4 1135.45  4958.3 1131.94  4968.4 1125.32  4978.5 1114.89  4988.6 1110.40
  4996.8 1104.71  5003.9 1104.29  5008.4 1102.87  5008.6 1102.37  5012.1 1102.37
  5012.4 1102.87  5018.3 1108.93  5024.7 1109.14  5032.6 1131.64  5039.1 1134.64
  5074.3 1138.08  5096.5 1138.87  5110.8 1142.09  5117.3 1142.04  5154.5 1145.99
#Mann=4,-1,0
  4655.5    0.07       0  4800.7    0.12       0  5008.4    0.05       0
  5012.4    0.12       0
Bank Sta=5008.4,5012.4
Exp/Cntr=0.3,0.1

Type RM Length L Ch R = 1,548,291,291,291
BEGIN DESCRIPTION:
Stream0210_DS 2.0
END DESCRIPTION:
XS GIS Cut Line= 3
      2123325.00     13877525.05      2123325.00     13877375.00
      2123325.00     13877275.05
#Sta/Elev= 30
  4845.3 1137.42  4847.8 1137.42  4855.3 1137.12  4875.3 1135.49  4885.3 1134.43
  4895.3 1134.21  4905.3 1130.50  4913.7 1115.79  4915.3 1112.99  4925.3 1107.67
  4935.3 1102.60  4945.3 1099.08  4955.3 1095.02  4965.3 1091.12  4975.3 1087.71
  4985.3 1155.05  4992.8 1081.38  4997.8 1081.38  5005.3 1081.60  5013.3 1081.19
  5013.6 1080.69  5017.1 1080.69  5017.3 1081.19  5025.3 1084.30  5045.3 1093.50
  5055.3 1099.12  5065.3 1121.25  5075.3 1135.37  5085.3 1138.99  5095.3 1138.86
#Mann=4,-1,0
  4845.3   0.035       0  4913.7    0.12       0  5013.3    0.05       0
  5017.3    0.12       0
Bank Sta=5013.3,5017.3
Exp/Cntr=0.3,0.1

Type RM Length L Ch R = 1,257,0,0,0
BEGIN DESCRIPTION:
Stream0210_DS 1.0
END DESCRIPTION:
XS GIS Cut Line= 3
      2123408.58     13877698.88      2123600.00     13877425.05
      2123580.55     13877038.24
#Sta/Elev= 30
  4665.9 1146.34  4717.2 1142.18  4780.4 1137.11  4830.4 1135.97  4866.2 1132.21
  4874.9 1128.76  4881.0 1116.30  4889.7 1110.60  4910.6 1100.23  4916.7 1099.18
  4925.5 1094.26  4931.6 1093.66  4946.4 1083.19  4952.5 1081.68  4961.2 1075.93
  4982.2 1069.28  4998.0 1068.27  4998.2 1067.77  5002.0 1068.27  5047.2 1090.77
  5060.1 1096.25  5080.2 1100.79  5090.2 1104.88  5100.2 1124.99  5110.2 1137.20
  5130.2 1138.73  5197.2 1149.70  5290.4 1156.17  5350.5 1171.10  5387.3 1177.52
#Mann=5,-1,0
  4665.9   0.035       0  4717.2    0.07       0  4998.0    0.05       0
  5002.0    0.07       0  5047.2    0.12       0
Bank Sta=4998,5002
Exp/Cntr=0.3,0.1

Chan Stop Cuts=-1