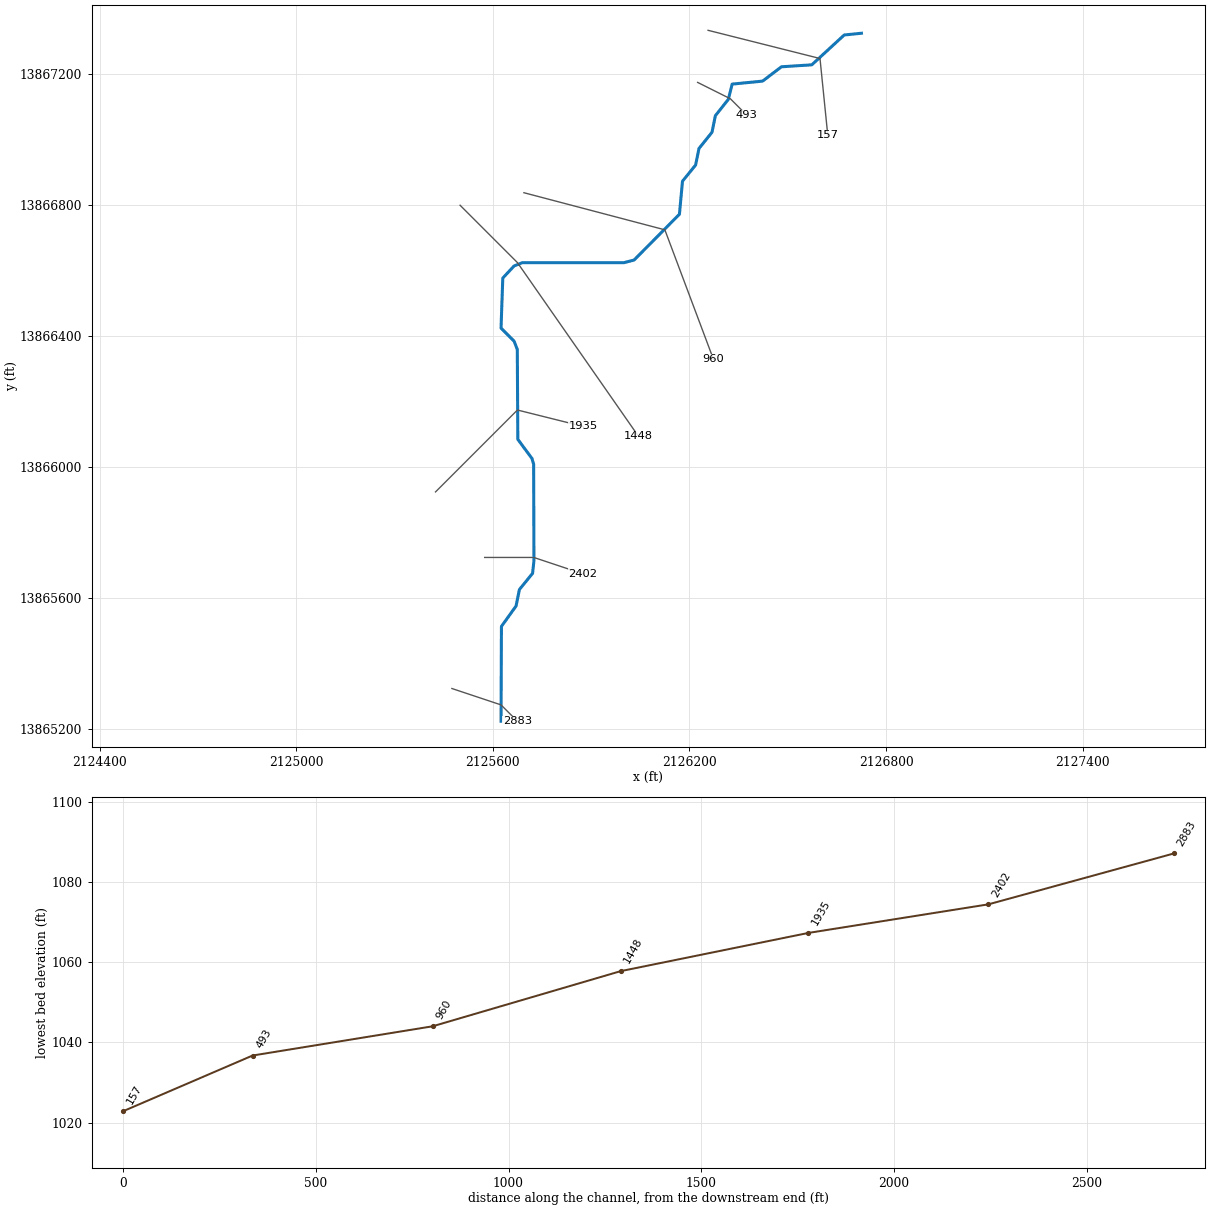
--- Stream0212_DS.prj (project) ---

Proj Title=Stream0212_DS Base Level Engineering
Current Plan=p01
Default Exp/Contr=0.3,0.1
English Units
Geom File=g01
Flow File=f01
Plan File=p01
BEGIN DESCRIPTION:
Stream0212_DS
END DESCRIPTION:

--- Stream0212_DS.p01 (plan) ---

Plan Title=Multiple Run
Short Identifier=Multiple
Geom File=g01
Flow File=f01
Subcritical Flow
K Sum by GR= 0
Std Step Tol= 0.01
Critical Tol= 0.01
Num of Std Step Trials= 20
Max Error Tol= 0.3
Flow Tol Ratio= 0.001
Split Flow NTrial= 30
Split Flow Tol= 0.02
Split Flow Ratio= 0.02
Log Output Level= 0
Friction Slope Method= 1
Unsteady Friction Slope Method= 2
Unsteady Bridges Friction Slope Method= 1
Parabolic Critical Depth
Global Vel Dist=  1 , 1 , 1
Global Log Level= 0
CheckData=True
Encroach Param= -1, 0, 0, 0
BEGIN DESCRIPTION:
Multiple Run
END DESCRIPTION:

--- Stream0212_DS.f01 (steady flow) ---

Flow Title=Multiple
Number of Profiles=7
Profile Names=10-year,25-year,50-year,1pct_min,100-year,1pct_plu,500-year
River Rch & RM= Stream0212_DS,Reach-1,2883
     569     928    1257     828    1653    3298    2819
River Rch & RM= Stream0212_DS,Reach-1,1448
     763    1269    1743    1162    2319    4628    4056
Boundary for River Rch & Prof#=Stream0212_DS,Reach-1,1
Up Type=0
Dn Type=3
Dn Slope=0.005
Boundary for River Rch & Prof#=Stream0212_DS,Reach-1,2
Up Type=0
Dn Type=3
Dn Slope=0.005
Boundary for River Rch & Prof#=Stream0212_DS,Reach-1,3
Up Type=0
Dn Type=3
Dn Slope=0.005
Boundary for River Rch & Prof#=Stream0212_DS,Reach-1,4
Up Type=0
Dn Type=3
Dn Slope=0.005
Boundary for River Rch & Prof#=Stream0212_DS,Reach-1,5
Up Type=0
Dn Type=3
Dn Slope=0.005
Boundary for River Rch & Prof#=Stream0212_DS,Reach-1,6
Up Type=0
Dn Type=3
Dn Slope=0.005
Boundary for River Rch & Prof#=Stream0212_DS,Reach-1,7
Up Type=0
Dn Type=3
Dn Slope=0.005

--- Stream0212_DS.g01 (geometry) ---

Geom Title=Existing Conditions

River Reach=Stream0212_DS,Reach-1
Reach XY= 30
      2125625.00     13865225.00      2125626.20     13865514.50
      2125670.81     13865576.74      2125681.12     13865627.18
      2125721.25     13865676.55      2125725.46     13865714.81
      2125724.48     13866009.78      2125719.25     13866027.33
      2125676.22     13866085.50      2125674.64     13866359.85
      2125664.95     13866384.98      2125625.00     13866425.00
      2125630.31     13866577.76      2125664.82     13866614.68
      2125690.02     13866624.68      2126000.12     13866624.70
      2126031.19     13866632.81      2126169.48     13866772.57
      2126178.83     13866873.41      2126218.88     13866922.82
      2126229.16     13866973.28      2126268.92     13867022.81
      2126279.15     13867073.31      2126318.73     13867123.20
      2126330.44     13867169.75      2126423.33     13867178.89
      2126480.97     13867222.64      2126573.50     13867228.61
      2126672.49     13867319.67      2126725.00     13867325.00

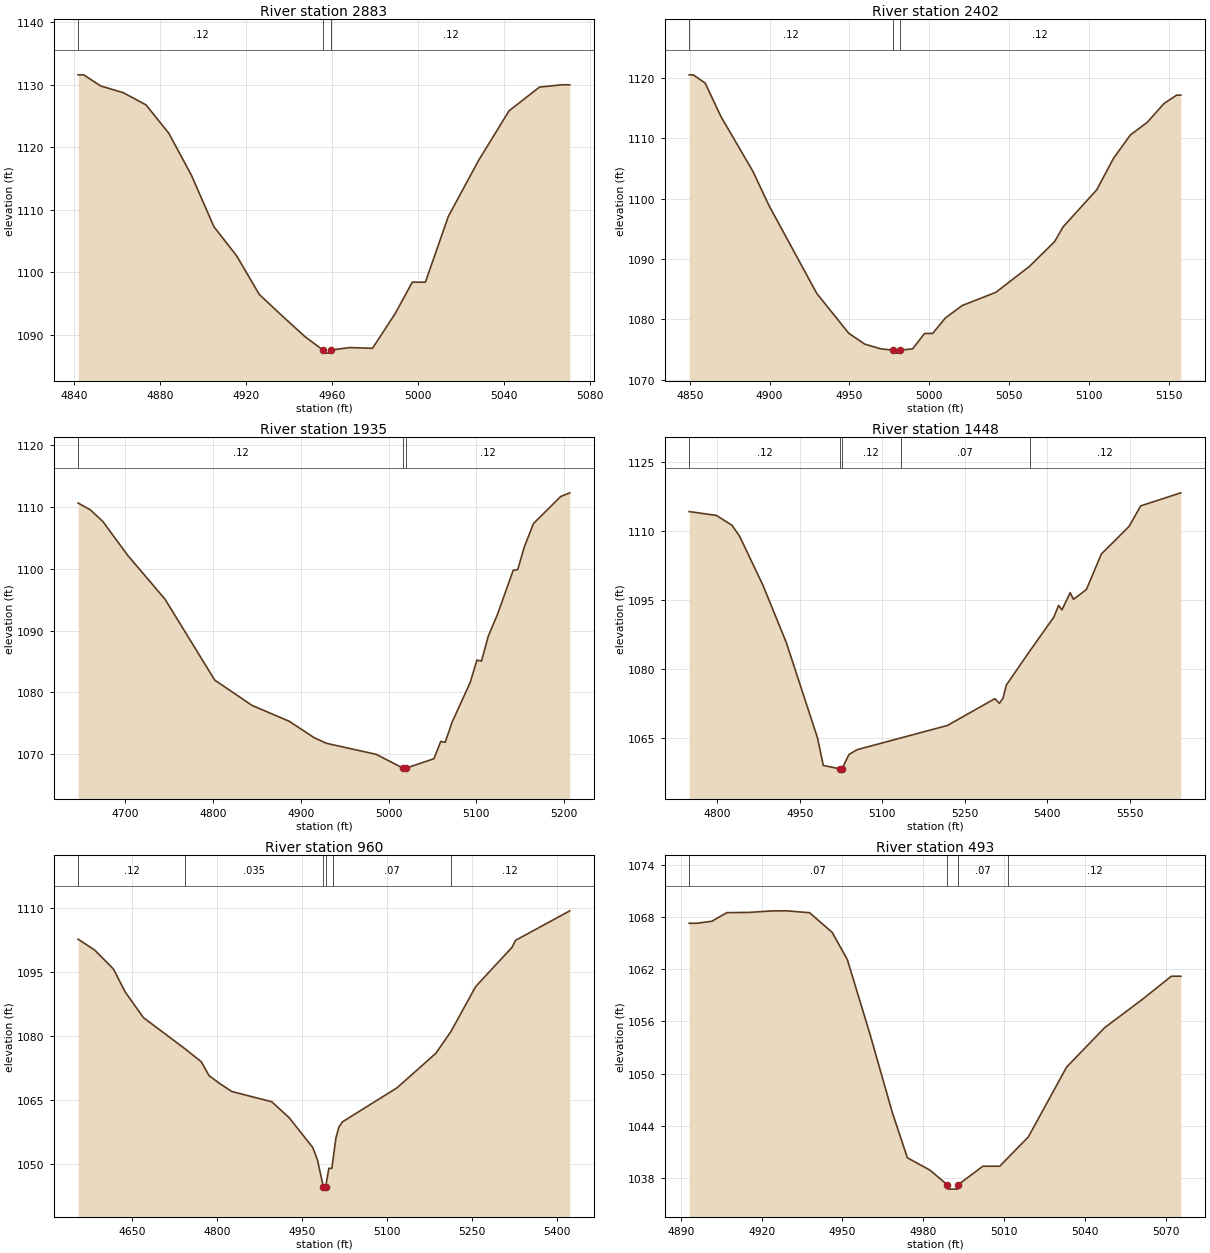
Type RM Length L Ch R = 1,2883,481,481,481
BEGIN DESCRIPTION:
Stream0212_DS 6.0
END DESCRIPTION:
XS GIS Cut Line= 3
      2125475.00     13865325.00      2125625.00     13865275.00
      2125674.98     13865225.02
#Sta/Elev= 28
  4841.9 1131.59  4844.5 1131.59  4852.4 1129.81  4863.0 1128.72  4873.5 1126.78
  4884.1 1122.25  4894.6 1115.55  4905.1 1107.29  4915.7 1102.62  4926.2 1096.46
  4936.8 1093.05  4947.3 1089.76  4955.8 1087.57  4956.1 1087.07  4959.6 1087.07
  4959.8 1087.57  4968.4 1087.96  4978.9 1087.84  4989.5 1093.43  4997.4 1098.42
  5000.0 1098.42  5003.5 1098.42  5014.2 1108.95  5028.3 1117.92  5042.4 1125.82
  5056.6 1129.63  5067.2 1130.00  5070.7 1130.00
#Mann=3,-1,0
  4841.9    0.12       0  4955.8    0.05       0  4959.8    0.12       0
Bank Sta=4955.8,4959.8
Exp/Cntr=0.3,0.1

Type RM Length L Ch R = 1,2402,467,467,467
BEGIN DESCRIPTION:
Stream0212_DS 5.0
END DESCRIPTION:
XS GIS Cut Line= 3
      2125575.01     13865725.00      2125725.00     13865725.00
      2125875.00     13865675.00
#Sta/Elev= 30
  4849.6 1120.48  4852.1 1120.48  4859.6 1119.13  4869.6 1113.53  4889.6 1104.47
  4899.6 1098.85  4929.6 1084.27  4949.6 1077.69  4959.6 1075.90  4969.6 1075.11
  4977.6 1074.90  4977.8 1074.40  4981.3 1074.40  4981.6 1074.90  4989.6 1075.10
  4997.1 1077.66  5002.2 1077.66  5010.1 1080.21  5020.7 1082.28  5041.8 1084.47
  5062.8 1088.75  5078.6 1092.86  5083.9 1095.30  5105.0 1101.44  5115.5 1106.65
  5126.1 1110.53  5136.6 1112.60  5147.2 1115.74  5155.1 1117.12  5157.7 1117.12
#Mann=3,-1,0
  4849.6    0.12       0  4977.6    0.05       0  4981.6    0.12       0
Bank Sta=4977.6,4981.6
Exp/Cntr=0.3,0.1

Type RM Length L Ch R = 1,1935,487,487,487
BEGIN DESCRIPTION:
Stream0212_DS 4.0
END DESCRIPTION:
XS GIS Cut Line= 3
      2125425.02     13865925.02      2125675.00     13866175.00
      2125875.02     13866124.99
#Sta/Elev= 30
  4646.6 1110.65  4660.7 1109.53  4674.9 1107.64  4703.1 1102.18  4745.6 1095.08
  4802.1 1082.01  4844.6 1077.91  4887.0 1075.34  4915.3 1072.69  4929.4 1071.78
  4986.0 1069.99  5016.2 1067.78  5016.4 1067.28  5019.9 1067.28  5020.2 1067.78
  5051.7 1069.29  5059.4 1072.08  5064.5 1071.95  5072.3 1075.20  5092.9 1081.61
  5100.6 1085.24  5105.8 1085.08  5113.5 1089.11  5123.8 1092.57  5141.9 1099.77
  5147.0 1099.88  5154.7 1103.61  5165.0 1107.34  5196.0 1111.71  5206.3 1112.30
#Mann=3,-1,0
  4646.6    0.12       0  5016.2    0.05       0  5020.2    0.12       0
Bank Sta=5016.2,5020.2
Exp/Cntr=0.3,0.1

Type RM Length L Ch R = 1,1448,488,488,488
BEGIN DESCRIPTION:
Stream0212_DS 3.0
END DESCRIPTION:
XS GIS Cut Line= 3
      2125499.99     13866800.01      2125675.00     13866625.00
      2126044.78     13866094.33
#Sta/Elev= 30
  4748.7 1114.14  4798.2 1113.30  4826.5 1111.18  4840.6 1108.75  4883.1 1098.09
  4925.5 1085.65  4982.1 1065.00  4992.7 1058.99  5022.6 1058.26  5022.8 1057.76
  5026.6 1058.26  5039.4 1061.38  5054.2 1062.42  5133.4 1064.96  5218.3 1067.67
  5304.7 1073.50  5313.1 1072.48  5319.5 1073.60  5325.6 1076.46  5368.3 1083.85
  5412.0 1091.22  5420.7 1093.76  5426.8 1092.79  5441.7 1096.53  5447.7 1095.07
  5471.3 1097.23  5498.4 1104.91  5549.0 1110.94  5569.9 1115.37  5643.0 1118.21
#Mann=5,-1,0
  4748.7    0.12       0  5022.6    0.05       0  5026.6    0.12       0
  5133.4    0.07       0  5368.3    0.12       0
Bank Sta=5022.6,5026.6
Exp/Cntr=0.3,0.1

Type RM Length L Ch R = 1,960,467,467,467
BEGIN DESCRIPTION:
Stream0212_DS 2.0
END DESCRIPTION:
XS GIS Cut Line= 3
      2125694.85     13866838.26      2126125.00     13866725.00
      2126273.37     13866329.63
#Sta/Elev= 30
  4554.9 1102.76  4584.1 1100.21  4617.1 1095.77  4637.8 1090.39  4669.9 1084.35
  4743.3 1077.01  4772.2 1073.95  4785.7 1070.71  4803.2 1068.97  4826.0 1066.96
  4896.3 1064.56  4927.3 1060.78  4968.7 1053.80  4977.0 1050.91  4987.4 1044.52
  4987.6 1044.02  4991.4 1044.52  4997.1 1048.92  5002.4 1048.92  5004.4 1050.92
  5009.5 1056.01  5014.8 1058.59  5021.1 1059.84  5117.2 1067.82  5185.7 1075.93
  5212.2 1081.02  5256.1 1091.64  5320.1 1100.85  5326.3 1102.49  5422.0 1109.43
#Mann=6,-1,0
  4554.9    0.12       0  4743.3   0.035       0  4987.4    0.05       0
  4991.4   0.035       0  5004.4    0.07       0  5212.2    0.12       0
Bank Sta=4987.4,4991.4
Exp/Cntr=0.3,0.1

Type RM Length L Ch R = 1,493,336,336,336
BEGIN DESCRIPTION:
Stream0212_DS 1.0
END DESCRIPTION:
XS GIS Cut Line= 3
      2126225.02     13867174.99      2126325.00     13867125.00
      2126375.01     13867074.99
#Sta/Elev= 29
  4893.1 1067.28  4895.9 1067.28  4901.5 1067.51  4907.1 1068.50  4915.4 1068.53
  4923.8 1068.70  4929.4 1068.71  4937.8 1068.49  4946.2 1066.23  4951.8 1063.12
  4960.2 1054.56  4968.5 1045.55  4974.1 1040.34  4982.5 1038.92  4988.9 1037.24
  4989.2 1036.74  4992.7 1036.74  4992.9 1037.24  4996.5 1038.07  5002.1 1039.37
  5004.9 1039.37  5008.4 1039.37  5011.5 1040.36  5019.0 1042.74  5033.2 1050.76
  5047.3 1055.28  5061.4 1058.56  5072.1 1061.20  5075.6 1061.20
#Mann=4,-1,0
  4893.1    0.07       0  4988.9    0.05       0  4992.9    0.07       0
  5011.5    0.12       0
Bank Sta=4988.9,4992.9
Exp/Cntr=0.3,0.1

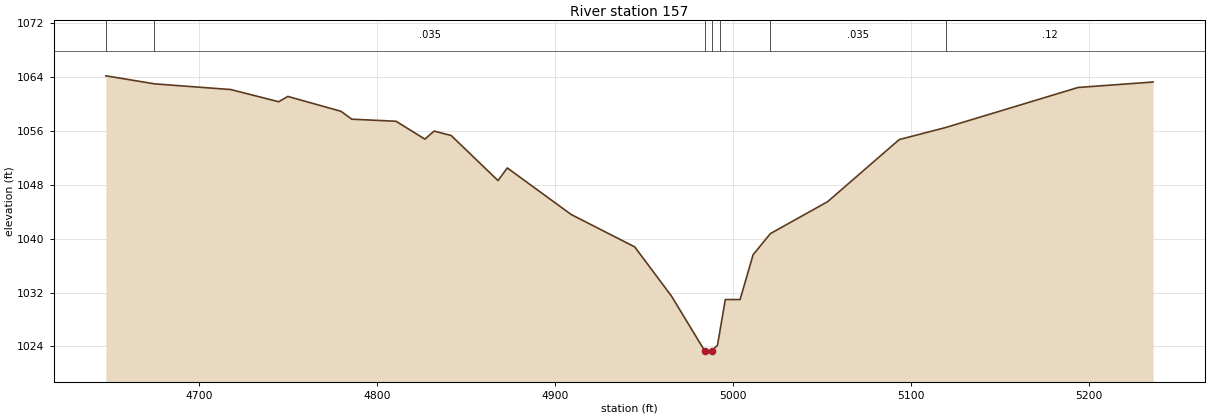
Type RM Length L Ch R = 1,157,0,0,0
BEGIN DESCRIPTION:
Stream0212_DS 0.0
END DESCRIPTION:
XS GIS Cut Line= 3
      2126256.89     13867333.97      2126598.52     13867247.89
      2126622.30     13867013.09
#Sta/Elev= 30
  4647.7 1064.20  4675.0 1063.01  4717.9 1062.16  4744.8 1060.35  4749.9 1061.14
  4779.8 1058.93  4785.8 1057.76  4810.7 1057.45  4826.9 1054.80  4832.1 1055.99
  4841.7 1055.33  4868.0 1048.64  4873.2 1050.52  4909.1 1043.60  4944.8 1038.79
  4965.4 1031.50  4984.1 1023.36  4984.3 1022.86  4988.1 1023.36  4991.3 1024.18
  4992.7 1026.34  4995.7 1030.97  5004.0 1030.97  5011.3 1037.62  5021.0 1040.76
  5053.2 1045.51  5093.4 1054.73  5119.6 1056.53  5193.9 1062.47  5236.0 1063.28
#Mann=7,-1,0
  4647.7    0.07       0  4675.0   0.035       0  4984.1    0.05       0
  4988.1   0.035       0  4992.7    0.12       0  5021.0   0.035       0
  5119.6    0.12       0
Bank Sta=4984.1,4988.1
Exp/Cntr=0.3,0.1

Chan Stop Cuts=-1