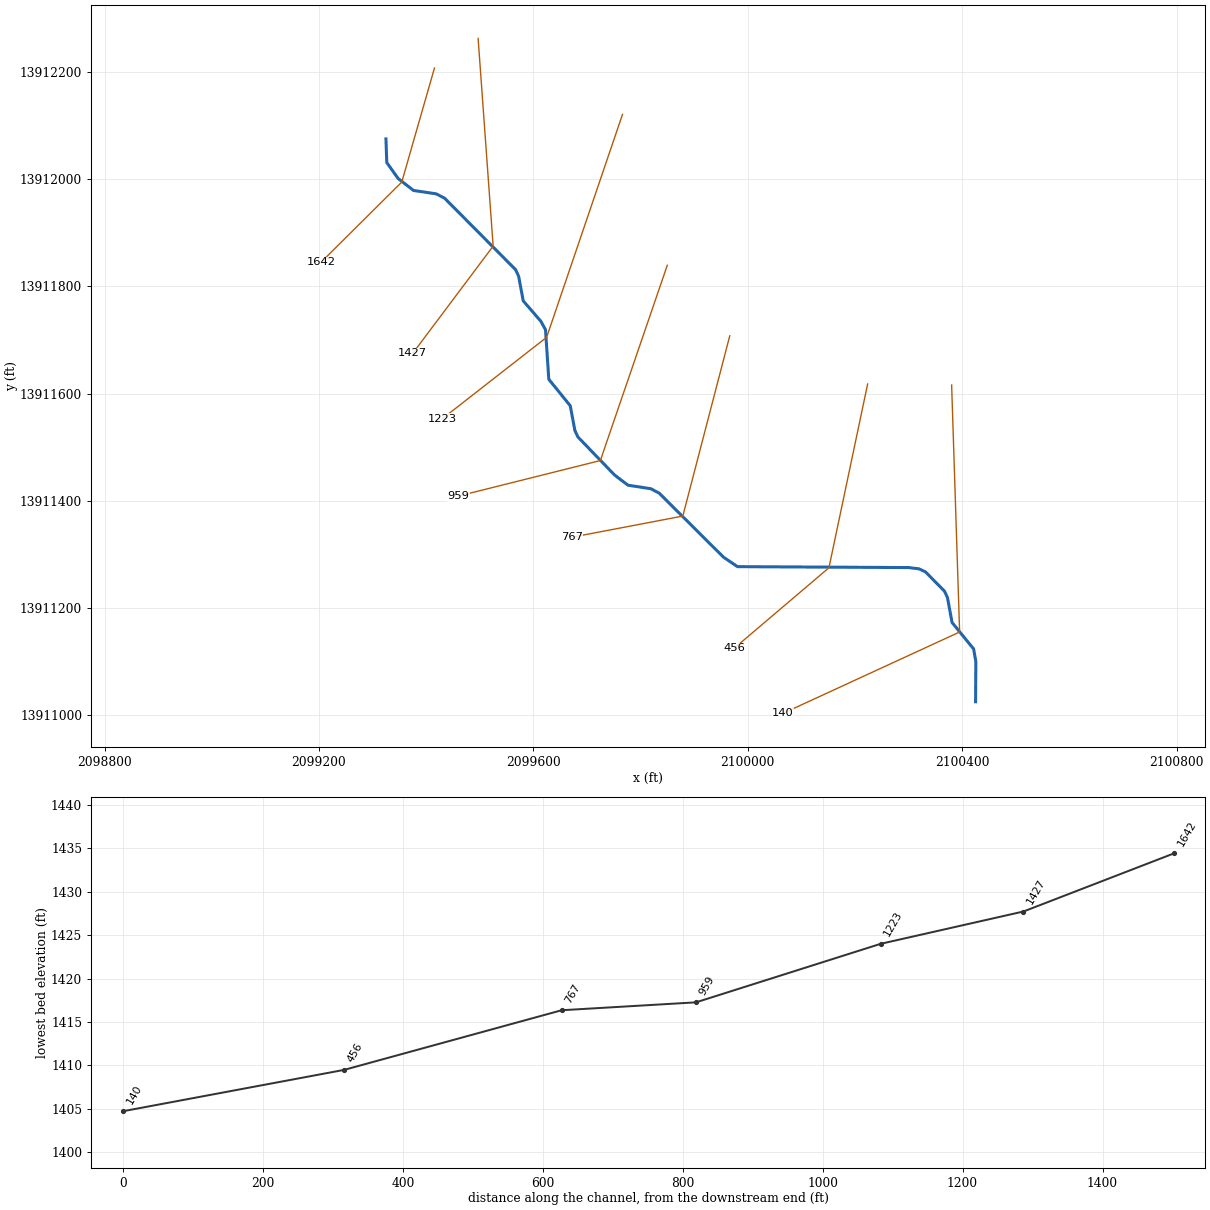
--- Stream0214_DS.prj (project) ---

Proj Title=Stream0214_DS Base Level Engineering
Current Plan=p01
Default Exp/Contr=0.3,0.1
English Units
Geom File=g01
Flow File=f01
Plan File=p01
Y Axis Title=Elevation
X Axis Title(PF)=Main Channel Distance
X Axis Title(XS)=Station
BEGIN DESCRIPTION:
Stream0214_DS
END DESCRIPTION:
DSS Export Rating Curves= 0
DSS Export Rating Curve Sorted= 0
DSS Export Volume Flow Curves= 0
DXF OffsetX= 0
DXF OffsetY= 0
DXF ScaleX= 1
DXF ScaleY= 10

--- Stream0214_DS.p01 (plan) ---

Plan Title=Multiple Run
Short Identifier=Multiple
Geom File=g01
Flow File=f01
Subcritical Flow
K Sum by GR= 0
Std Step Tol= 0.01
Critical Tol= 0.01
Num of Std Step Trials= 20
Max Error Tol= 0.3
Flow Tol Ratio= 0.001
Split Flow NTrial= 30
Split Flow Tol= 0.02
Split Flow Ratio= 0.02
Log Output Level= 0
Friction Slope Method= 1
Unsteady Friction Slope Method= 2
Unsteady Bridges Friction Slope Method= 1
Parabolic Critical Depth
Global Vel Dist=  1 , 1 , 1
Global Log Level= 0
CheckData=True
Encroach Param= -1, 0, 0, 0
BEGIN DESCRIPTION:
Multiple Run
END DESCRIPTION:

--- Stream0214_DS.f01 (steady flow) ---

Flow Title=Multiple
Number of Profiles=7
Profile Names=10-year,25-year,50-year,1pct_min,100-year,1pct_plu,500-year
River Rch & RM= Stream0214_DS,Reach-1,1642
     648    1079    1485     995    1985    3960    3507
Boundary for River Rch & Prof#=Stream0214_DS,Reach-1,1
Up Type=0
Dn Type=3
Dn Slope=0.005
Boundary for River Rch & Prof#=Stream0214_DS,Reach-1,2
Up Type=0
Dn Type=3
Dn Slope=0.005
Boundary for River Rch & Prof#=Stream0214_DS,Reach-1,3
Up Type=0
Dn Type=3
Dn Slope=0.005
Boundary for River Rch & Prof#=Stream0214_DS,Reach-1,4
Up Type=0
Dn Type=3
Dn Slope=0.005
Boundary for River Rch & Prof#=Stream0214_DS,Reach-1,5
Up Type=0
Dn Type=3
Dn Slope=0.005
Boundary for River Rch & Prof#=Stream0214_DS,Reach-1,6
Up Type=0
Dn Type=3
Dn Slope=0.005
Boundary for River Rch & Prof#=Stream0214_DS,Reach-1,7
Up Type=0
Dn Type=3
Dn Slope=0.005

--- Stream0214_DS.g01 (geometry) ---

Geom Title=Existing Conditions
Program Version=4.10

River Reach=Stream0214_DS   ,Reach-1
Reach XY= 30
        2099325.       13912075.      2099326.56     13912030.87
      2099347.82     13912001.02      2099376.46     13911978.86
      2099418.94     13911972.49      2099434.67     13911964.23
      2099566.86     13911831.06       2099572.5     13911818.97
      2099581.14     13911772.83      2099614.16     13911734.65
      2099622.67     13911719.03      2099628.83     13911626.58
      2099668.86     13911577.17      2099677.49     13911531.02
      2099683.13     13911518.93      2099751.49     13911447.99
      2099776.64     13911428.97      2099818.95     13911422.46
      2099834.68     13911414.22      2099954.84     13911294.61
      2099980.85     13911277.06      2100300.21     13911275.33
      2100319.33     13911273.02      2100331.48     13911267.31
        2100367.     13911231.39      2100372.59     13911219.17
      2100381.12     13911172.84      2100421.37      13911123.5
      2100425.48      13911100.2        2100425.       13911025.

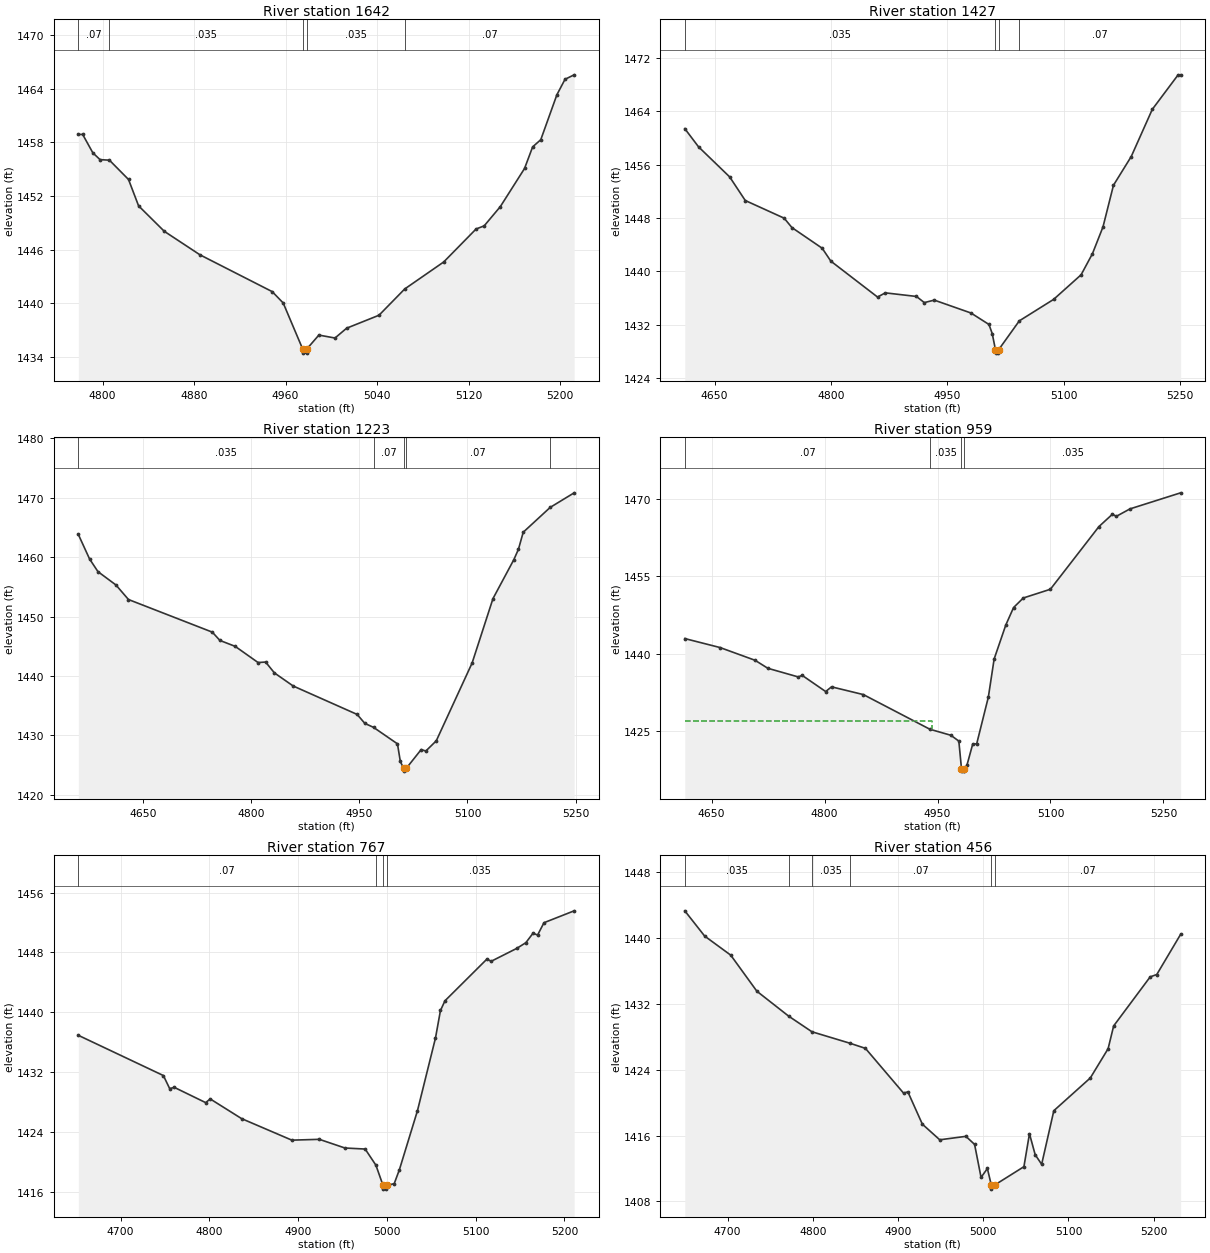
Type RM Length L Ch R = 1 ,1642    ,215,215,215
BEGIN DESCRIPTION:
Stream0214_DS 7.0
END DESCRIPTION:
XS GIS Cut Line= 3
       2099415.5     13912207.24      2099354.53     13911994.51
      2099203.84     13911844.82
#Sta/Elev= 30
  4778.7 1458.88  4782.5 1458.88  4791.4 1456.82  4797.7 1456.06  4805.9    1456
  4822.6 1453.84  4831.4 1450.89  4853.9 1448.04  4885.1 1445.41  4948.3 1441.29
  4957.9 1440.02  4974.8 1434.91  4975.1 1434.41  4978.6 1434.41  4978.8 1434.91
  4989.1 1436.43  5003.2  1436.1  5013.4  1437.2  5041.7 1438.65  5064.2 1441.59
  5098.3 1444.61  5126.6  1448.3  5133.7 1448.65  5147.8  1450.8    5169 1455.07
  5176.1 1457.49  5183.2 1458.29  5197.3 1463.32  5204.4 1465.05  5212.4 1465.55
#Mann= 5 ,-1 , 0
  4778.7     .07       0  4805.9    .035       0  4974.8    .035       0
  4978.8    .035       0  5064.2     .07       0
Bank Sta=4974.8,4978.8
XS Rating Curve= 0 ,0
Exp/Cntr=0.3,0.1

Type RM Length L Ch R = 1 ,1427    ,204,204,204
BEGIN DESCRIPTION:
Stream0214_DS 6.0
END DESCRIPTION:
XS GIS Cut Line= 3
      2099496.95     13912262.66        2099525.       13911875.
      2099374.98     13911674.98
#Sta/Elev= 30
  4611.7 1461.39  4629.4 1458.66  4669.5 1454.15  4689.6 1450.61  4739.7 1447.96
  4749.7 1446.55  4788.7 1443.45  4799.8 1441.52    4860 1436.13    4870 1436.76
  4910.1 1436.22  4920.2  1435.3  4933.1 1435.67  4980.3 1433.74  5003.5 1432.02
  5007.7 1430.66  5011.9 1428.22  5012.2 1427.72  5015.7 1427.72  5015.9 1428.22
  5042.6 1432.56  5086.8 1435.78  5122.2 1439.47  5136.8 1442.63  5150.4 1446.65
  5163.9  1452.9  5186.8 1457.21  5213.9 1464.28  5247.2 1469.46  5250.4 1469.46
#Mann= 4 ,-1 , 0
  4611.7    .035       0  5011.9    .035       0  5015.9    .035       0
  5042.6     .07       0
Bank Sta=5011.9,5015.9
XS Rating Curve= 0 ,0
Exp/Cntr=0.3,0.1

Type RM Length L Ch R = 1 ,1223    ,264,264,264
BEGIN DESCRIPTION:
Stream0214_DS 5.0
END DESCRIPTION:
XS GIS Cut Line= 3
      2099766.32     13912120.78      2099624.77     13911704.91
      2099429.36     13911552.37
#Sta/Elev= 30
  4560.7 1463.82  4576.2 1459.71  4587.9 1457.56  4612.8 1455.32  4630.2 1452.87
  4746.4 1447.38  4756.9 1445.99  4778.1 1444.99  4809.8 1442.27  4820.3 1442.35
  4832.4 1440.53  4858.5 1438.32  4947.1 1433.54  4957.8 1432.03  4969.9 1431.36
    5003 1428.59    5007 1425.62  5011.4  1424.5  5011.6    1424  5015.4  1424.5
  5035.9 1427.63  5042.3 1427.38  5056.8  1429.1  5106.5  1442.2  5135.4 1453.03
  5164.4  1459.6  5170.7 1461.33  5177.3 1464.19  5214.7 1468.37  5247.9 1470.82
#Mann= 5 ,-1 , 0
  4560.7    .035       0  4969.9     .07       0  5011.4     .05       0
  5015.4     .07       0  5214.7    .035       0
Bank Sta=5011.4,5015.4
XS Rating Curve= 0 ,0
Exp/Cntr=0.3,0.1

Type RM Length L Ch R = 1 ,959     ,192,192,192
BEGIN DESCRIPTION:
Stream0214_DS 4.0
END DESCRIPTION:
XS GIS Cut Line= 3
      2099849.88     13911839.35        2099725.       13911475.
      2099459.74     13911408.61
#Sta/Elev= 30
  4614.3 1442.91  4661.2 1441.17  4707.6 1438.71  4724.6 1437.16  4764.9 1435.49
  4770.2 1435.79  4801.4 1432.66  4809.2 1433.57  4851.5 1432.07  4939.9 1425.36
  4967.7  1424.2  4978.3 1423.07  4981.8 1417.76  4982.1 1417.26  4985.6 1417.26
  4985.8 1417.76  4989.1 1418.42  4996.8 1422.53    5002 1422.53  5017.5 1431.58
  5025.2 1438.96  5040.7 1445.54    5051 1448.91  5063.9 1450.76  5099.9 1452.45
  5164.4 1464.58  5182.3 1466.97  5187.5 1466.56  5205.6    1468  5272.9 1471.11
#Mann= 4 ,-1 , 0
  4614.3     .07       0  4939.9    .035       0  4981.8    .035       0
  4985.8    .035       0
#XS Ineff= 2 , 0
       0  4942.8  1426.9               0
Permanent Ineff=
       F       F
Bank Sta=4981.8,4985.8
XS Rating Curve= 0 ,0
Exp/Cntr=0.3,0.1

Type RM Length L Ch R = 1 ,767     ,311,311,311
BEGIN DESCRIPTION:
Stream0214_DS 3.0
END DESCRIPTION:
XS GIS Cut Line= 3
      2099966.43      13911707.7      2099878.84     13911371.41
      2099671.58      13911331.9
#Sta/Elev= 30
  4652.5 1436.92  4748.3 1431.54  4755.4 1429.79  4760.6 1429.96  4795.9 1427.92
  4801.1 1428.41  4836.4 1425.78    4893  1422.9    4924 1423.01  4952.8 1421.85
  4975.6 1421.71  4987.7 1419.55  4995.7 1416.85    4996 1416.35  4999.5 1416.35
  4999.7 1416.85  5008.3 1417.08  5014.1 1418.93  5034.5 1426.84  5054.8 1436.56
  5060.4 1440.24  5065.5 1441.54  5112.6  1447.1  5117.7 1446.83  5146.4 1448.55
  5156.6 1449.31  5164.7 1450.58  5169.8 1450.33    5177 1451.98    5211 1453.57
#Mann= 4 ,-1 , 0
  4652.5     .07       0  4987.7    .035       0  4995.7    .035       0
  4999.7    .035       0
Bank Sta=4995.7,4999.7
XS Rating Curve= 0 ,0
Exp/Cntr=0.3,0.1

Type RM Length L Ch R = 1 ,456     ,316,316,316
BEGIN DESCRIPTION:
Stream0214_DS 2.0
END DESCRIPTION:
XS GIS Cut Line= 3
      2100223.63     13911617.79      2100151.43     13911275.01
      2099974.99     13911124.99
#Sta/Elev= 30
  4649.7 1443.33    4673 1440.26  4703.6 1437.94  4734.3 1433.55  4771.6 1430.52
  4798.9 1428.62  4843.7 1427.22  4861.7  1426.6  4906.4 1421.16  4911.5 1421.31
  4928.5 1417.38  4948.9 1415.48  4979.6  1415.9  4989.8 1414.92  4997.4  1410.9
  5004.8 1411.99  5009.4 1409.98  5009.6 1409.48  5013.4 1409.98  5047.7 1412.21
  5054.2 1416.22  5060.9 1413.67  5068.5  1412.5  5082.8 1419.02  5125.6    1423
  5146.5 1426.56    5153 1429.33  5195.9  1435.3  5203.6 1435.58  5231.6 1440.47
#Mann= 6 ,-1 , 0
  4649.7    .035       0  4771.6     .07       0  4798.9    .035       0
  4843.7     .07       0  5009.4     .05       0  5013.4     .07       0
Bank Sta=5009.4,5013.4
XS Rating Curve= 0 ,0
Exp/Cntr=0.3,0.1

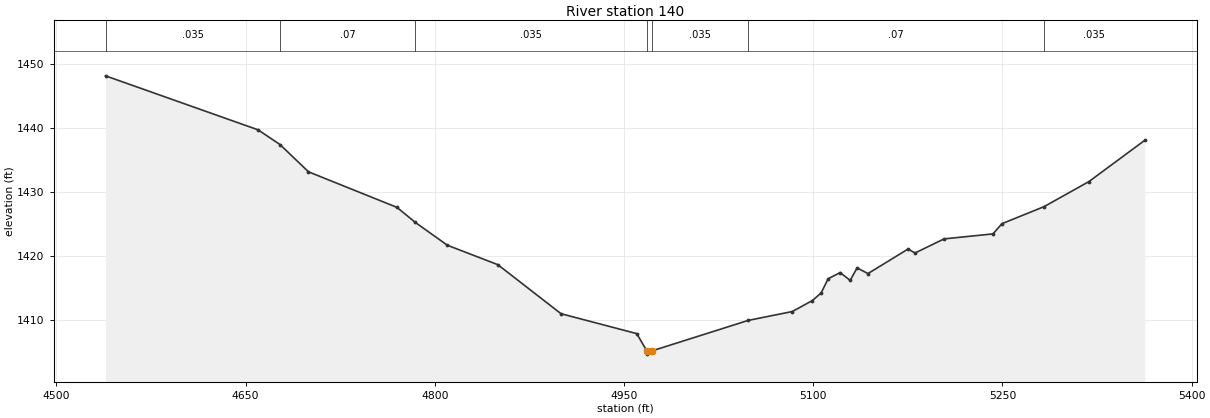
Type RM Length L Ch R = 1 ,140     ,0,0,0
BEGIN DESCRIPTION:
Stream0214_DS 1.0
END DESCRIPTION:
XS GIS Cut Line= 3
      2100380.34     13911615.86      2100395.23      13911155.1
      2100065.71     13911003.32
#Sta/Elev= 30
    4539 1448.12  4659.9  1439.7  4677.3 1437.41  4699.9 1433.15    4770 1427.61
  4784.6 1425.26    4810  1421.7    4850 1418.67  4900.1 1411.02  4960.1 1407.92
  4968.1 1405.22  4968.3 1404.72  4972.1 1405.22  5048.5 1409.98  5083.4 1411.36
  5099.3 1413.07  5106.3 1414.26  5111.8 1416.47  5121.4 1417.44  5129.3 1416.22
  5134.8 1418.17  5143.4 1417.28  5175.2 1421.11  5180.7 1420.49  5203.7 1422.69
  5242.5 1423.47  5249.6 1425.06    5283 1427.72  5318.5 1431.62  5362.8 1438.06
#Mann= 7 ,-1 , 0
    4539    .035       0  4677.3     .07       0  4784.6    .035       0
  4968.1    .035       0  4972.1    .035       0  5048.5     .07       0
    5283    .035       0
Bank Sta=4968.1,4972.1
XS Rating Curve= 0 ,0
Exp/Cntr=0.3,0.1

Chan Stop Cuts=-1
Use User Specified Reach Order=0
Composite Channel Slope=5