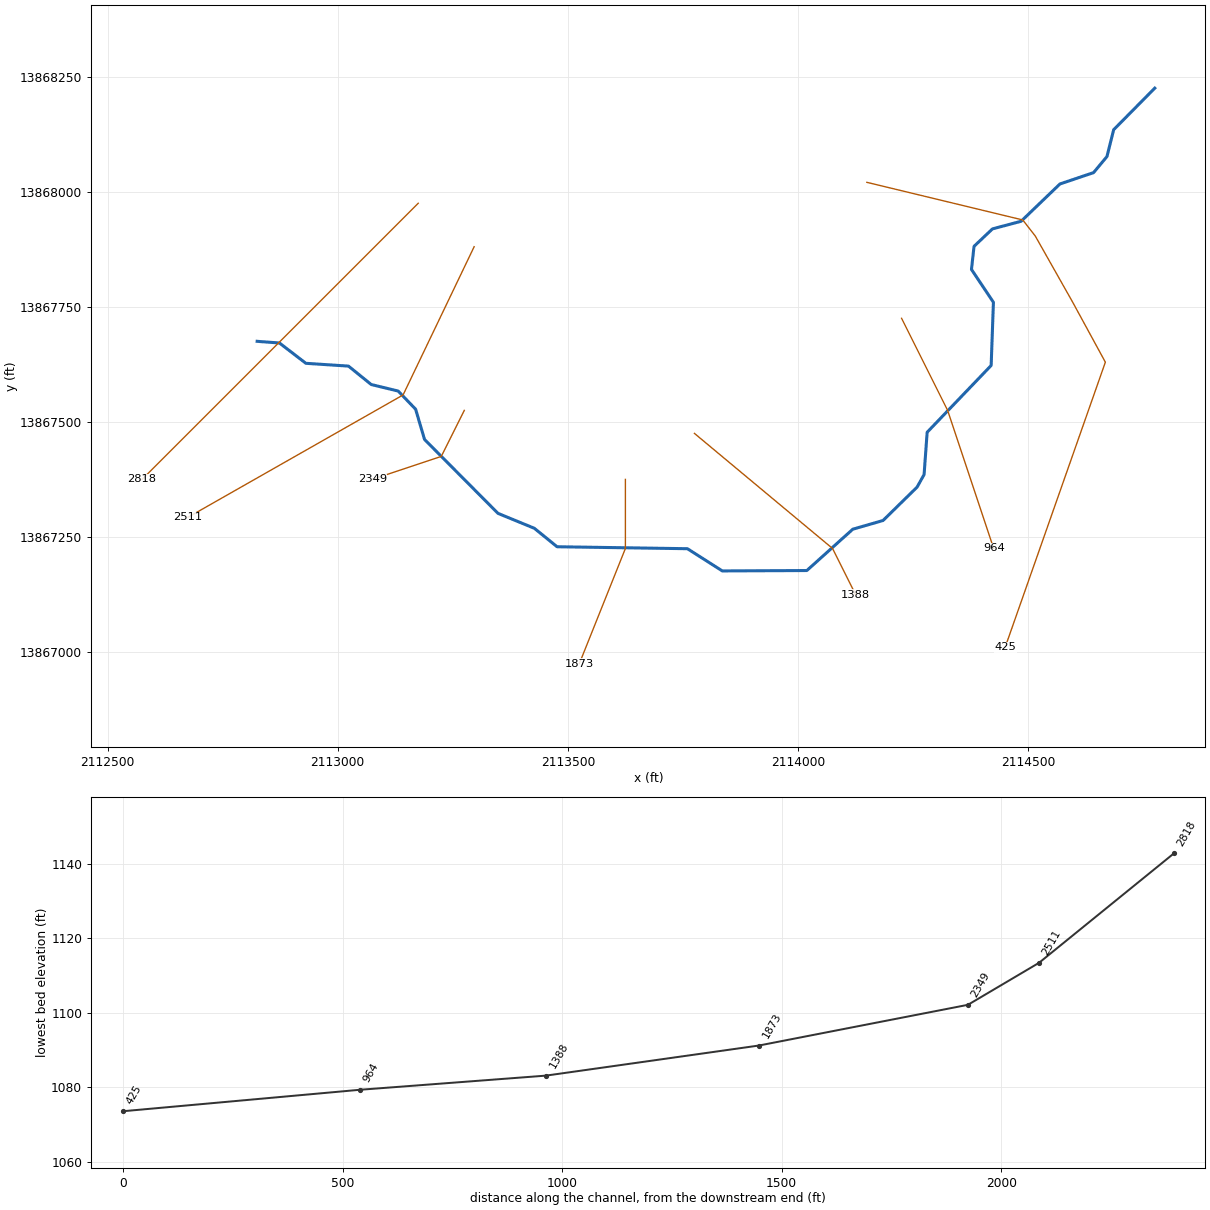
--- Stream0216_DS.prj (project) ---

Proj Title=Stream0216_DS Base Level Engineering
Current Plan=p01
Default Exp/Contr=0.3,0.1
English Units
Geom File=g01
Flow File=f01
Plan File=p01
BEGIN DESCRIPTION:
Stream0216_DS
END DESCRIPTION:

--- Stream0216_DS.p01 (plan) ---

Plan Title=Multiple Run
Short Identifier=Multiple
Geom File=g01
Flow File=f01
Subcritical Flow
K Sum by GR= 0
Std Step Tol= 0.01
Critical Tol= 0.01
Num of Std Step Trials= 20
Max Error Tol= 0.3
Flow Tol Ratio= 0.001
Split Flow NTrial= 30
Split Flow Tol= 0.02
Split Flow Ratio= 0.02
Log Output Level= 0
Friction Slope Method= 1
Unsteady Friction Slope Method= 2
Unsteady Bridges Friction Slope Method= 1
Parabolic Critical Depth
Global Vel Dist=  1 , 1 , 1
Global Log Level= 0
CheckData=True
Encroach Param= -1, 0, 0, 0
BEGIN DESCRIPTION:
Multiple Run
END DESCRIPTION:

--- Stream0216_DS.f01 (steady flow) ---

Flow Title=Multiple
Number of Profiles=7
Profile Names=10-year,25-year,50-year,1pct_min,100-year,1pct_plu,500-year
River Rch & RM= Stream0216_DS,Reach-1,2818
     261     400     520     330     658    1313    1036
River Rch & RM= Stream0216_DS,Reach-1,2511
     509     824    1110     727    1452    2896    2449
Boundary for River Rch & Prof#=Stream0216_DS,Reach-1,1
Up Type=0
Dn Type=3
Dn Slope=0.005
Boundary for River Rch & Prof#=Stream0216_DS,Reach-1,2
Up Type=0
Dn Type=3
Dn Slope=0.005
Boundary for River Rch & Prof#=Stream0216_DS,Reach-1,3
Up Type=0
Dn Type=3
Dn Slope=0.005
Boundary for River Rch & Prof#=Stream0216_DS,Reach-1,4
Up Type=0
Dn Type=3
Dn Slope=0.005
Boundary for River Rch & Prof#=Stream0216_DS,Reach-1,5
Up Type=0
Dn Type=3
Dn Slope=0.005
Boundary for River Rch & Prof#=Stream0216_DS,Reach-1,6
Up Type=0
Dn Type=3
Dn Slope=0.005
Boundary for River Rch & Prof#=Stream0216_DS,Reach-1,7
Up Type=0
Dn Type=3
Dn Slope=0.005

--- Stream0216_DS.g01 (geometry) ---

Geom Title=Existing Conditions

River Reach=Stream0216_DS,Reach-1
Reach XY= 30
      2112825.00     13867675.00      2112873.49     13867671.36
      2112930.92     13867627.23      2113023.42     13867621.18
      2113072.85     13867581.15      2113131.34     13867566.98
      2113169.25     13867527.54      2113188.64     13867461.80
      2113348.18     13867301.29      2113427.17     13867268.86
      2113476.55     13867228.75      2113759.78     13867224.48
      2113835.51     13867176.22      2114019.14     13867177.06
      2114118.96     13867266.82      2114184.70     13867285.77
      2114258.56     13867358.21      2114273.84     13867385.48
      2114280.52     13867477.43      2114419.55     13867622.55
      2114424.48     13867759.78      2114376.77     13867831.17
      2114382.36     13867881.34      2114422.39     13867919.25
      2114484.65     13867935.81      2114568.98     13868016.82
      2114642.05     13868041.49      2114671.13     13868076.43
      2114685.72     13868134.69      2114775.00     13868225.00

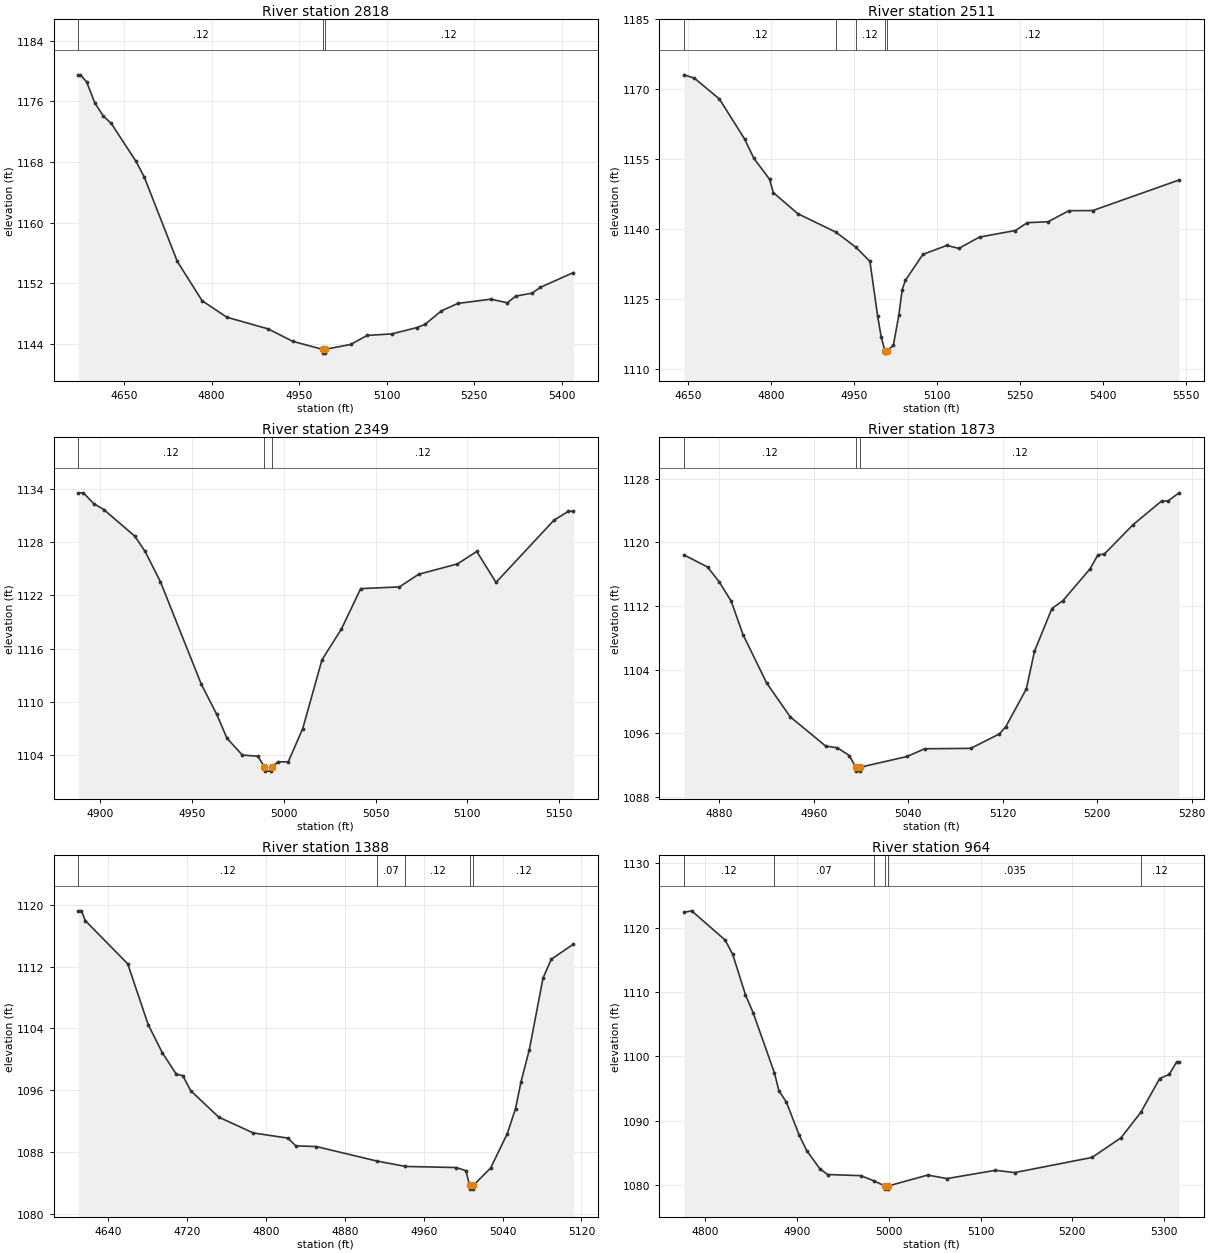
Type RM Length L Ch R = 1,2818,307,307,307
BEGIN DESCRIPTION:
Stream0216_DS 5.0
END DESCRIPTION:
XS GIS Cut Line= 3
      2113174.97     13867974.97      2112875.00     13867675.00
      2112574.99     13867374.99
#Sta/Elev= 30
  4571.4 1179.50  4574.9 1179.50  4585.5 1178.59  4599.6 1175.82  4613.8 1174.10
  4627.9 1173.09  4670.4 1168.07  4684.5 1166.00  4741.1 1154.88  4783.5 1149.70
  4825.9 1147.52  4896.6 1145.98  4939.1 1144.33  4990.1 1143.28  4990.3 1142.78
  4993.8 1142.78  4994.1 1143.28  5038.1 1143.92  5066.3 1145.11  5108.8 1145.32
  5151.2 1146.14  5165.3 1146.56  5193.6 1148.35  5221.9 1149.34  5278.5 1149.90
  5306.8 1149.42  5320.9 1150.30  5349.2 1150.70  5363.3 1151.46  5419.9 1153.41
#Mann=3,-1,0
  4571.4    0.12       0  4990.1    0.05       0  4994.1    0.12       0
Bank Sta=4990.1,4994.1
Exp/Cntr=0.3,0.1

Type RM Length L Ch R = 1,2511,162,162,162
BEGIN DESCRIPTION:
Stream0216_DS 4.5
END DESCRIPTION:
XS GIS Cut Line= 3
      2113296.42     13867880.53      2113142.05     13867558.51
      2112674.85     13867292.75
#Sta/Elev= 30
  4642.9 1173.11  4661.7 1172.40  4707.0 1167.92  4752.3 1159.39  4769.4 1155.18
  4797.6 1150.71  4804.3 1147.86  4848.6 1143.34  4917.6 1139.37  4953.1 1136.18
  4978.9 1133.13  4992.8 1121.43  4999.2 1116.95  5006.1 1113.94  5006.4 1113.44
  5010.1 1113.94  5021.3 1115.14  5031.1 1121.53  5037.2 1127.05  5042.9 1129.02
  5074.6 1134.61  5117.9 1136.53  5139.5 1135.90  5177.0 1138.33  5241.8 1139.73
  5263.4 1141.41  5300.9 1141.61  5338.4 1143.98  5381.6 1144.01  5537.5 1150.56
#Mann=5,-1,0
  4642.9    0.12       0  4917.6    0.07       0  4953.1    0.12       0
  5006.1    0.05       0  5010.1    0.12       0
Bank Sta=5006.1,5010.1
Exp/Cntr=0.3,0.1

Type RM Length L Ch R = 1,2349,476,476,476
BEGIN DESCRIPTION:
Stream0216_DS 4.0
END DESCRIPTION:
XS GIS Cut Line= 3
      2113275.02     13867525.04      2113225.00     13867425.00
      2113074.97     13867374.99
#Sta/Elev= 30
  4887.9 1133.58  4890.7 1133.58  4896.3 1132.36  4901.9 1131.68  4918.7 1128.69
  4924.3 1126.98  4932.7 1123.54  4955.0 1111.97  4963.4 1108.58  4969.0 1105.87
  4977.4 1103.98  4985.8 1103.85  4989.4 1102.67  4989.6 1102.17  4993.1 1102.17
  4993.4 1102.67  4997.0 1103.22  5002.4 1103.22  5010.3 1106.97  5020.8 1114.74
  5031.4 1118.21  5041.9 1122.77  5063.0 1122.96  5073.5 1124.39  5094.6 1125.55
  5105.2 1126.96  5115.7 1123.47  5147.3 1130.49  5155.2 1131.50  5157.9 1131.50
#Mann=3,-1,0
  4887.9    0.12       0  4989.4    0.05       0  4993.4    0.12       0
Bank Sta=4989.4,4993.4
Exp/Cntr=0.3,0.1

Type RM Length L Ch R = 1,1873,485,485,485
BEGIN DESCRIPTION:
Stream0216_DS 3.0
END DESCRIPTION:
XS GIS Cut Line= 3
      2113625.00     13867375.00      2113625.00     13867225.00
      2113524.99     13866974.97
#Sta/Elev= 30
  4850.0 1118.41  4870.0 1116.89  4880.0 1114.99  4890.0 1112.60  4900.0 1108.41
  4920.0 1102.33  4940.0 1098.07  4970.0 1094.40  4980.0 1094.18  4990.0 1093.21
  4995.5 1091.75  4995.8 1091.25  4999.3 1091.25  4999.5 1091.75  5039.0 1093.09
  5053.9 1094.06  5092.9 1094.11  5117.1 1095.92  5122.5 1096.81  5140.0 1101.59
  5146.8 1106.28  5161.6 1111.67  5171.0 1112.68  5193.9 1116.65  5200.6 1118.43
  5206.0 1118.51  5230.2 1122.19  5254.5 1125.18  5259.8 1125.17  5269.3 1126.21
#Mann=3,-1,0
  4850.0    0.12       0  4995.5    0.05       0  4999.5    0.12       0
Bank Sta=4995.5,4999.5
Exp/Cntr=0.3,0.1

Type RM Length L Ch R = 1,1388,424,424,424
BEGIN DESCRIPTION:
Stream0216_DS 2.0
END DESCRIPTION:
XS GIS Cut Line= 3
      2113775.03     13867474.97      2114075.00     13867225.00
      2114125.01     13867124.97
#Sta/Elev= 30
  4609.5 1119.25  4612.7 1119.25  4616.6 1117.98  4659.6 1112.39  4680.4 1104.51
  4694.7 1100.87  4709.0 1098.06  4715.5 1097.89  4723.4 1095.96  4752.0 1092.51
  4787.1 1090.46  4822.3 1089.79  4830.1 1088.79  4850.9 1088.70  4912.1 1086.83
  4941.4 1086.12  4992.8 1085.98  5002.8 1085.57  5006.4 1083.68  5006.6 1083.18
  5010.1 1083.18  5010.4 1083.68  5027.9 1085.93  5044.7 1090.36  5053.1 1093.62
  5058.7 1097.11  5067.1 1101.26  5081.0 1110.54  5089.4 1112.98  5111.8 1114.93
#Mann=5,-1,0
  4609.5    0.12       0  4912.1    0.07       0  4941.4    0.12       0
  5006.4    0.05       0  5010.4    0.12       0
Bank Sta=5006.4,5010.4
Exp/Cntr=0.3,0.1

Type RM Length L Ch R = 1,964,539,539,539
BEGIN DESCRIPTION:
Stream0216_DS 1.0
END DESCRIPTION:
XS GIS Cut Line= 3
      2114224.98     13867725.04      2114325.00     13867525.00
      2114425.01     13867224.98
#Sta/Elev= 30
  4776.6 1122.36  4785.0 1122.59  4821.4 1118.07  4829.7 1115.86  4843.7 1109.53
  4852.1 1106.75  4875.2 1097.45  4880.1 1094.68  4888.4 1092.85  4902.4 1087.71
  4910.8 1085.28  4924.8 1082.54  4933.2 1081.65  4969.5 1081.47  4983.6 1080.67
  4995.5 1079.88  4995.7 1079.38  4999.2 1079.38  4999.5 1079.88  5042.4 1081.56
  5063.5 1081.02  5116.2 1082.30  5137.3 1081.95  5221.6 1084.30  5253.2 1087.35
  5274.7 1091.29  5295.4 1096.55  5305.9 1097.21  5313.8 1099.12  5316.5 1099.12
#Mann=6,-1,0
  4776.6    0.12       0  4875.2    0.07       0  4983.6   0.035       0
  4995.5   0.035       0  4999.5   0.035       0  5274.7    0.12       0
Bank Sta=4995.5,4999.5
Exp/Cntr=0.3,0.1

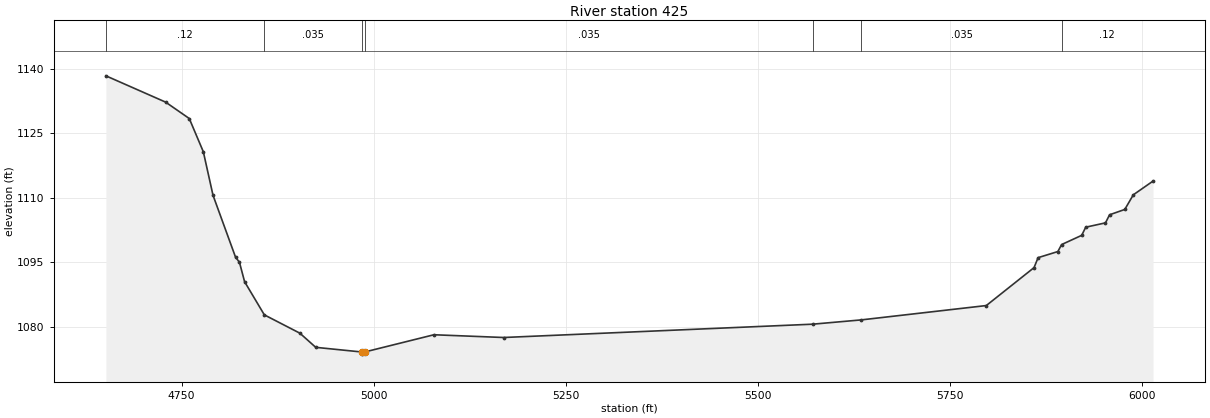
Type RM Length L Ch R = 1,425,0,0,0
BEGIN DESCRIPTION:
Stream0216_DS 0.0
END DESCRIPTION:
XS GIS Cut Line= 6
      2114149.51     13868020.41      2114488.18     13867938.66
      2114515.50     13867903.60      2114596.76     13867759.82
      2114667.67     13867629.72      2114449.93     13867010.25
#Sta/Elev= 30
  4651.6 1138.42  4729.3 1132.30  4760.1 1128.48  4778.4 1120.74  4791.0 1110.61
  4820.3 1096.21  4825.4 1095.02  4832.1 1090.49  4857.8 1082.77  4904.0 1078.51
  4924.7 1075.21  4984.4 1074.13  4984.7 1073.63  4988.4 1074.13  5078.5 1078.14
  5169.2 1077.50  5571.3 1080.60  5634.7 1081.60  5797.4 1084.94  5859.5 1093.77
  5864.8 1096.09  5890.5 1097.51  5895.4 1099.14  5921.5 1101.28  5926.8 1103.18
  5952.5 1104.19  5957.8 1106.07  5977.6 1107.31  5988.7 1110.72  6014.4 1113.92
#Mann=7,-1,0
  4651.6    0.12       0  4857.8   0.035       0  4984.4   0.035       0
  4988.4   0.035       0  5571.3    0.07       0  5634.7   0.035       0
  5895.4    0.12       0
Bank Sta=4984.4,4988.4
Exp/Cntr=0.3,0.1

Chan Stop Cuts=-1