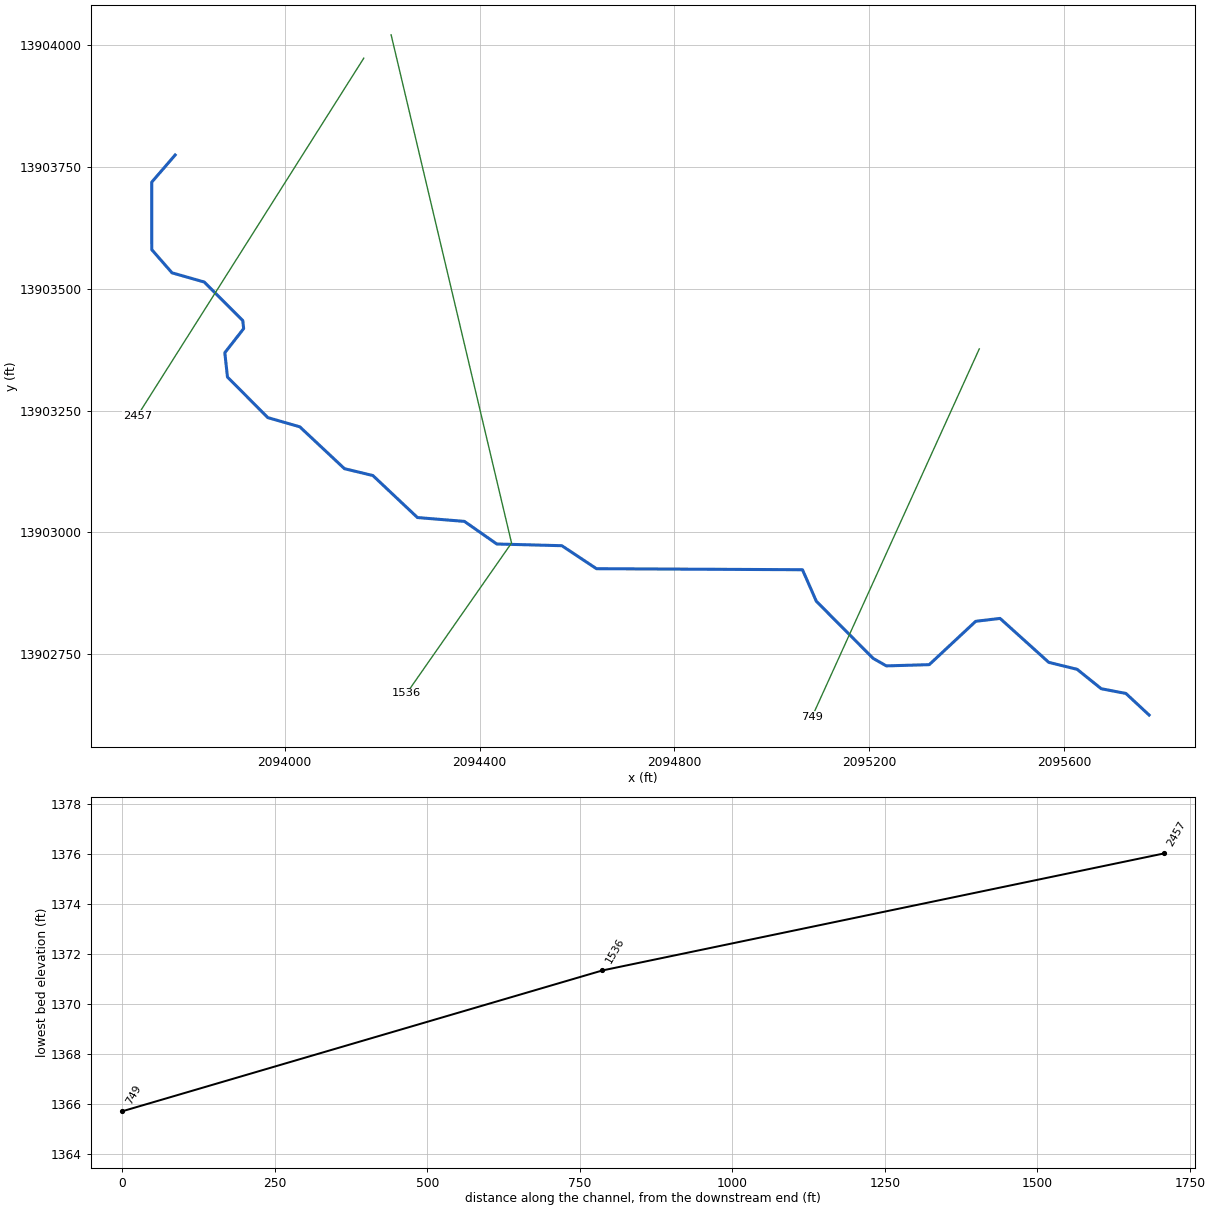
--- Stream0222_DS.prj (project) ---

Proj Title=Stream0222_DS Base Level Engineering
Current Plan=p01
Default Exp/Contr=0.3,0.1
English Units
Geom File=g01
Flow File=f01
Plan File=p01
BEGIN DESCRIPTION:
Stream0222_DS
END DESCRIPTION:

--- Stream0222_DS.p01 (plan) ---

Plan Title=Multiple Run
Short Identifier=Multiple
Geom File=g01
Flow File=f01
Subcritical Flow
K Sum by GR= 0
Std Step Tol= 0.01
Critical Tol= 0.01
Num of Std Step Trials= 20
Max Error Tol= 0.3
Flow Tol Ratio= 0.001
Split Flow NTrial= 30
Split Flow Tol= 0.02
Split Flow Ratio= 0.02
Log Output Level= 0
Friction Slope Method= 1
Unsteady Friction Slope Method= 2
Unsteady Bridges Friction Slope Method= 1
Parabolic Critical Depth
Global Vel Dist=  1 , 1 , 1
Global Log Level= 0
CheckData=True
Encroach Param= -1, 0, 0, 0
BEGIN DESCRIPTION:
Multiple Run
END DESCRIPTION:

--- Stream0222_DS.f01 (steady flow) ---

Flow Title=Multiple
Number of Profiles=7
Profile Names=10-year,25-year,50-year,1pct_min,100-year,1pct_plu,500-year
River Rch & RM= Stream0222_DS,Reach-1,2457
     736    1210    1649    1091    2177    4344    3746
Boundary for River Rch & Prof#=Stream0222_DS,Reach-1,1
Up Type=0
Dn Type=3
Dn Slope=0.005
Boundary for River Rch & Prof#=Stream0222_DS,Reach-1,2
Up Type=0
Dn Type=3
Dn Slope=0.005
Boundary for River Rch & Prof#=Stream0222_DS,Reach-1,3
Up Type=0
Dn Type=3
Dn Slope=0.005
Boundary for River Rch & Prof#=Stream0222_DS,Reach-1,4
Up Type=0
Dn Type=3
Dn Slope=0.005
Boundary for River Rch & Prof#=Stream0222_DS,Reach-1,5
Up Type=0
Dn Type=3
Dn Slope=0.005
Boundary for River Rch & Prof#=Stream0222_DS,Reach-1,6
Up Type=0
Dn Type=3
Dn Slope=0.005
Boundary for River Rch & Prof#=Stream0222_DS,Reach-1,7
Up Type=0
Dn Type=3
Dn Slope=0.005

--- Stream0222_DS.g01 (geometry) ---

Geom Title=Existing Conditions

River Reach=Stream0222_DS,Reach-1
Reach XY= 30
      2093775.00     13903775.00      2093726.88     13903719.21
      2093726.97     13903580.67      2093768.62     13903533.02
      2093834.71     13903514.21      2093913.89     13903435.08
      2093915.67     13903418.46      2093876.99     13903368.95
      2093882.49     13903318.93      2093965.30     13903235.77
      2094031.04     13903216.82      2094122.72     13903130.87
      2094181.04     13903116.82      2094272.58     13903030.54
      2094369.02     13903022.64      2094435.51     13902976.23
      2094569.06     13902972.73      2094640.22     13902925.52
      2095063.17     13902923.38      2095091.74     13902858.55
      2095208.25     13902741.40      2095235.48     13902725.93
      2095323.50     13902728.47      2095418.96     13902817.52
      2095468.95     13902823.41      2095568.95     13902733.16
      2095627.19     13902718.91      2095676.67     13902679.04
      2095727.36     13902669.33      2095775.00     13902625.00

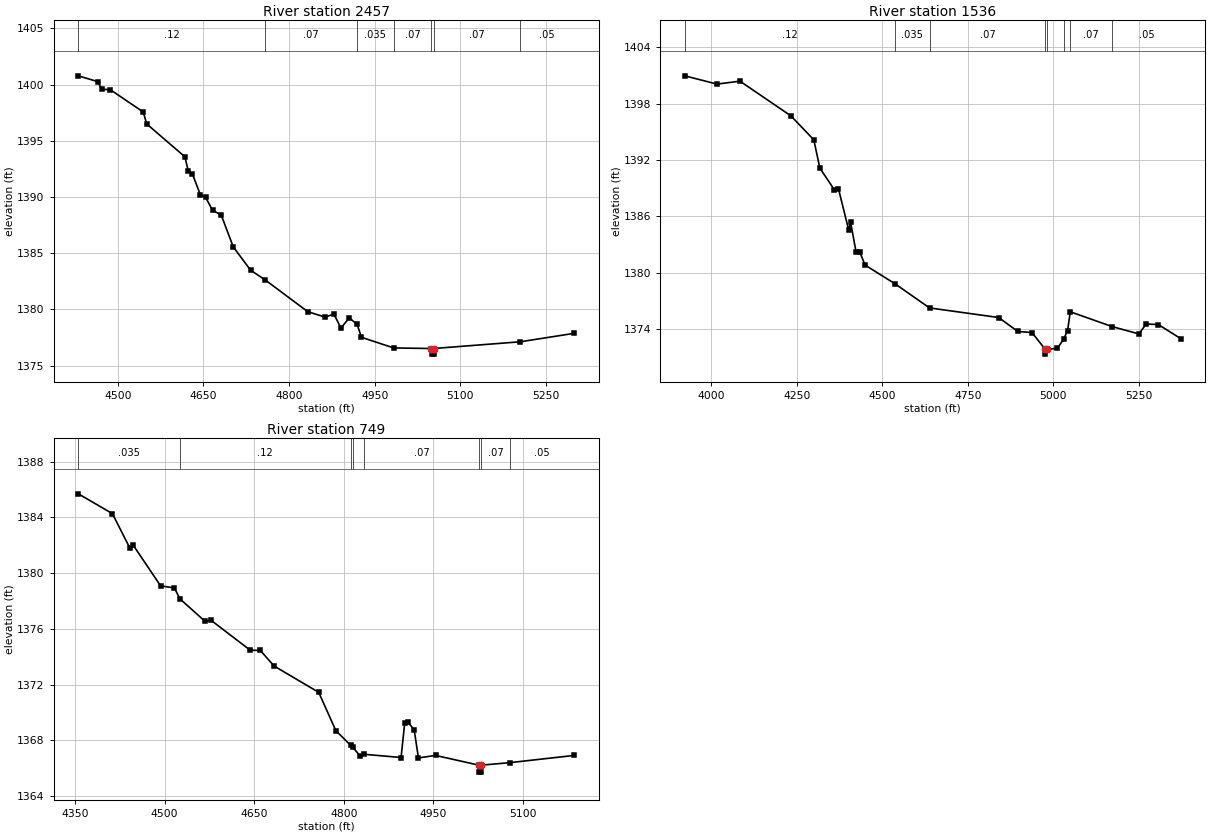
Type RM Length L Ch R = 1,2457,921,921,921
BEGIN DESCRIPTION:
Stream0222_DS 3.0
END DESCRIPTION:
XS GIS Cut Line= 2
      2094162.36     13903973.86      2093697.68     13903239.65
#Sta/Elev= 30
  4430.7 1400.78  4464.9 1400.26  4471.6 1399.59  4486.9 1399.54  4544.5 1397.56
  4550.5 1396.50  4617.4 1393.58  4623.4 1392.30  4630.5 1392.07  4644.5 1390.20
  4653.9 1389.96  4666.0 1388.80  4681.0 1388.41  4702.2 1385.56  4732.7 1383.48
  4757.4 1382.65  4832.7 1379.80  4863.2 1379.31  4878.5 1379.59  4890.9 1378.34
  4905.6 1379.25  4919.3 1378.66  4926.8 1377.52  4983.3 1376.57  5049.4 1376.52
  5049.7 1376.02  5053.2 1376.02  5053.4 1376.52  5205.4 1377.12  5299.6 1377.87
#Mann=7,-1,0
  4430.7    0.12       0  4757.4    0.07       0  4919.3   0.035       0
  4983.3    0.07       0  5049.4    0.05       0  5053.4    0.07       0
  5205.4    0.05       0
Bank Sta=5049.4,5053.4
Exp/Cntr=0.3,0.1

Type RM Length L Ch R = 1,1536,787,787,787
BEGIN DESCRIPTION:
Stream0222_DS 2.0
END DESCRIPTION:
XS GIS Cut Line= 3
      2094218.49     13904021.82      2094465.79     13902978.27
      2094250.56     13902669.79
#Sta/Elev= 30
  3923.1 1400.98  4016.9 1400.10  4084.3 1400.41  4233.3 1396.71  4300.1 1394.16
  4317.7 1391.15  4360.0 1388.85  4372.0 1388.96  4402.2 1384.52  4407.3 1385.43
  4423.4 1382.24  4433.7 1382.27  4449.6 1380.83  4537.8 1378.82  4638.1 1376.26
  4840.0 1375.24  4896.1 1373.75  4937.3 1373.64  4976.4 1371.84  4976.6 1371.34
  4980.4 1371.84  5011.8 1371.96  5029.7 1372.93  5041.4 1373.84  5049.3 1375.85
  5171.9 1374.27  5249.9 1373.49  5270.9 1374.55  5306.6 1374.49  5371.7 1373.00
#Mann=8,-1,0
  3923.1    0.12       0  4537.8   0.035       0  4638.1    0.07       0
  4976.4    0.05       0  4980.4    0.07       0  5029.7    0.12       0
  5049.3    0.07       0  5171.9    0.05       0
Bank Sta=4976.4,4980.4
Exp/Cntr=0.3,0.1

Type RM Length L Ch R = 1,749,0,0,0
BEGIN DESCRIPTION:
Stream0222_DS 1.0
END DESCRIPTION:
XS GIS Cut Line= 2
      2095426.28     13903376.90      2095082.82     13902621.19
#Sta/Elev= 30
  4355.5 1385.70  4412.5 1384.28  4441.6 1381.82  4447.1 1382.03  4493.2 1379.09
  4516.3 1378.94  4525.7 1378.15  4567.9 1376.53  4577.3 1376.63  4643.2 1374.47
  4660.2 1374.45  4683.3 1373.33  4758.0 1371.44  4786.5 1368.70  4811.5 1367.63
  4814.7 1367.51  4827.2 1366.87  4834.5 1366.99  4895.8 1366.76  4901.9 1369.22
  4907.3 1369.31  4917.8 1368.74  4924.9 1366.73  4953.5 1366.91  5026.2 1366.21
  5026.4 1365.71  5029.9 1365.71  5030.2 1366.21  5077.8 1366.39  5185.6 1366.91
#Mann=8,-1,0
  4355.5   0.035       0  4525.7    0.12       0  4811.5    0.07       0
  4814.7   0.035       0  4834.5    0.07       0  5026.2    0.05       0
  5030.2    0.07       0  5077.8    0.05       0
Bank Sta=5026.2,5030.2
Exp/Cntr=0.3,0.1

Chan Stop Cuts=-1