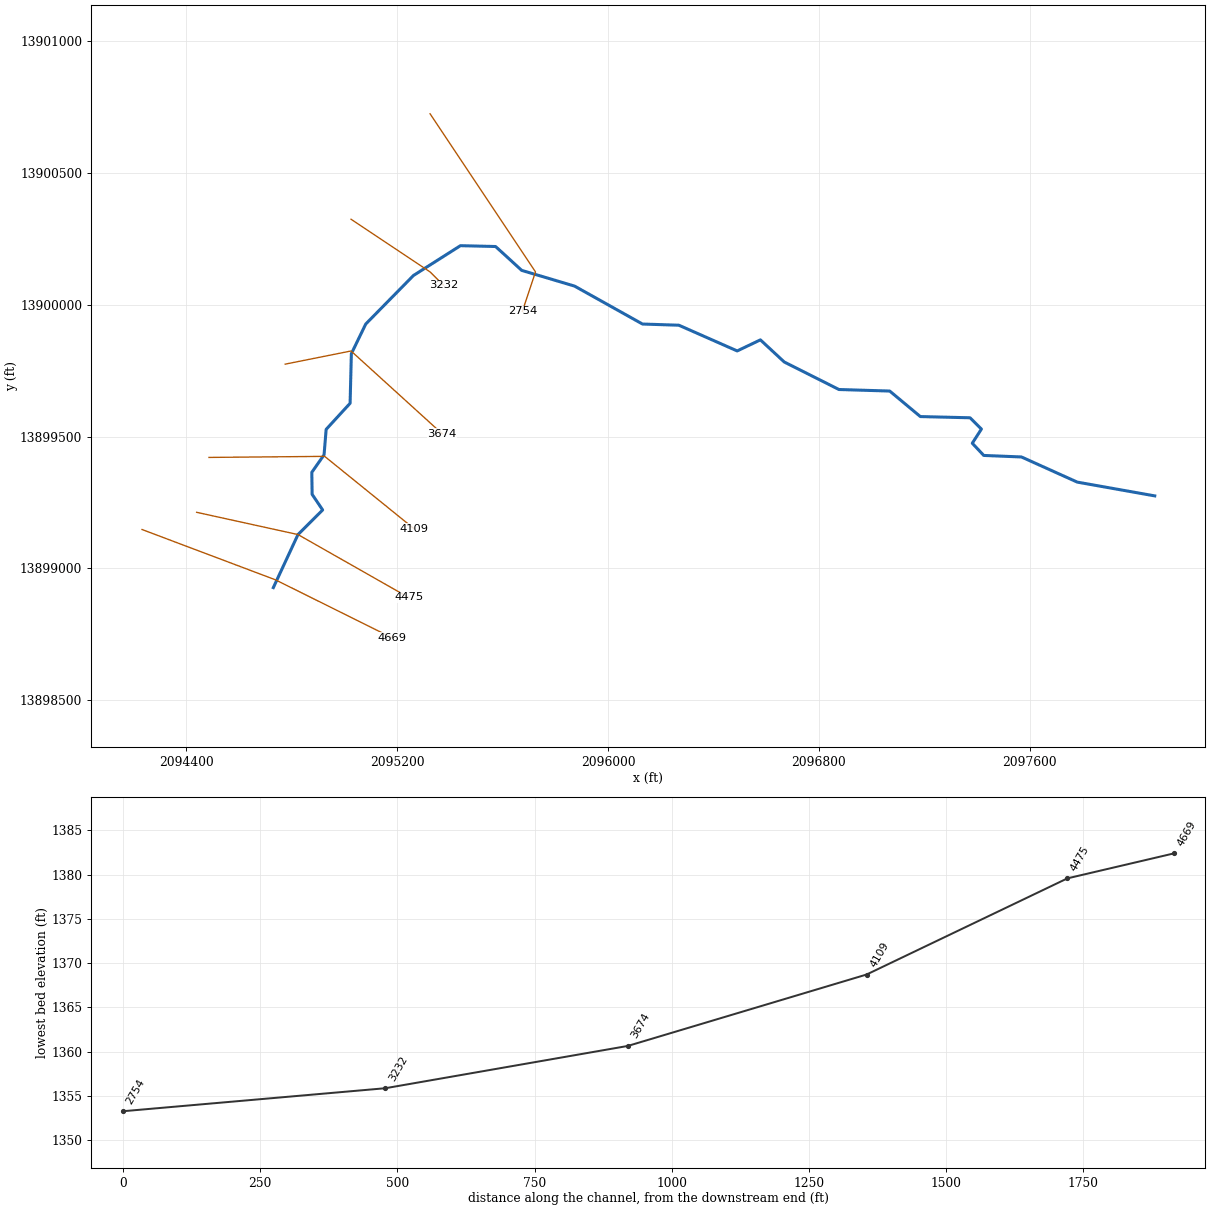
--- Stream0226_DS.prj (project) ---

Proj Title=Stream0226_DS Base Level Engineering
Current Plan=p01
Default Exp/Contr=0.3,0.1
English Units
Geom File=g01
Flow File=f01
Plan File=p01
BEGIN DESCRIPTION:
Stream0226_DS
END DESCRIPTION:

--- Stream0226_DS.p01 (plan) ---

Plan Title=Multiple Run
Short Identifier=Multiple
Geom File=g01
Flow File=f01
Subcritical Flow
K Sum by GR= 0
Std Step Tol= 0.01
Critical Tol= 0.01
Num of Std Step Trials= 20
Max Error Tol= 0.3
Flow Tol Ratio= 0.001
Split Flow NTrial= 30
Split Flow Tol= 0.02
Split Flow Ratio= 0.02
Log Output Level= 0
Friction Slope Method= 1
Unsteady Friction Slope Method= 2
Unsteady Bridges Friction Slope Method= 1
Parabolic Critical Depth
Global Vel Dist=  1 , 1 , 1
Global Log Level= 0
CheckData=True
Encroach Param= -1, 0, 0, 0
BEGIN DESCRIPTION:
Multiple Run
END DESCRIPTION:

--- Stream0226_DS.f01 (steady flow) ---

Flow Title=Multiple
Number of Profiles=7
Profile Names=10-year,25-year,50-year,1pct_min,100-year,1pct_plu,500-year
River Rch & RM= Stream0226_DS,Reach-1,4669
     542     882    1195     788    1572    3137    2684
River Rch & RM= Stream0226_DS,Reach-1,3674
     898    1503    2073    1387    2768    5523    4877
Boundary for River Rch & Prof#=Stream0226_DS,Reach-1,1
Up Type=0
Dn Type=3
Dn Slope=0.005
Boundary for River Rch & Prof#=Stream0226_DS,Reach-1,2
Up Type=0
Dn Type=3
Dn Slope=0.005
Boundary for River Rch & Prof#=Stream0226_DS,Reach-1,3
Up Type=0
Dn Type=3
Dn Slope=0.005
Boundary for River Rch & Prof#=Stream0226_DS,Reach-1,4
Up Type=0
Dn Type=3
Dn Slope=0.005
Boundary for River Rch & Prof#=Stream0226_DS,Reach-1,5
Up Type=0
Dn Type=3
Dn Slope=0.005
Boundary for River Rch & Prof#=Stream0226_DS,Reach-1,6
Up Type=0
Dn Type=3
Dn Slope=0.005
Boundary for River Rch & Prof#=Stream0226_DS,Reach-1,7
Up Type=0
Dn Type=3
Dn Slope=0.005

--- Stream0226_DS.g01 (geometry) ---

Geom Title=Existing Conditions

River Reach=Stream0226_DS,Reach-1
Reach XY= 30
      2094730.14     13898926.92      2094823.68     13899128.27
      2094917.23     13899221.57      2094877.37     13899280.89
      2094876.11     13899364.45      2094922.64     13899430.98
      2094930.54     13899527.42      2095021.45     13899626.47
      2095026.20     13899814.50      2095080.83     13899927.30
      2095261.79     13900111.37      2095440.17     13900224.63
      2095573.53     13900221.46      2095672.71     13900130.85
      2095873.42     13900071.17      2096130.93     13899927.25
      2096269.06     13899922.73      2096490.42     13899825.15
      2096578.40     13899867.17      2096668.94     13899783.18
      2096876.55     13899678.75      2097069.14     13899672.93
      2097185.44     13899576.06      2097374.00     13899571.46
      2097417.11     13899528.61      2097382.47     13899474.77
      2097426.00     13899428.54      2097569.06     13899422.73
      2097780.94     13899327.27      2098075.00     13899275.00

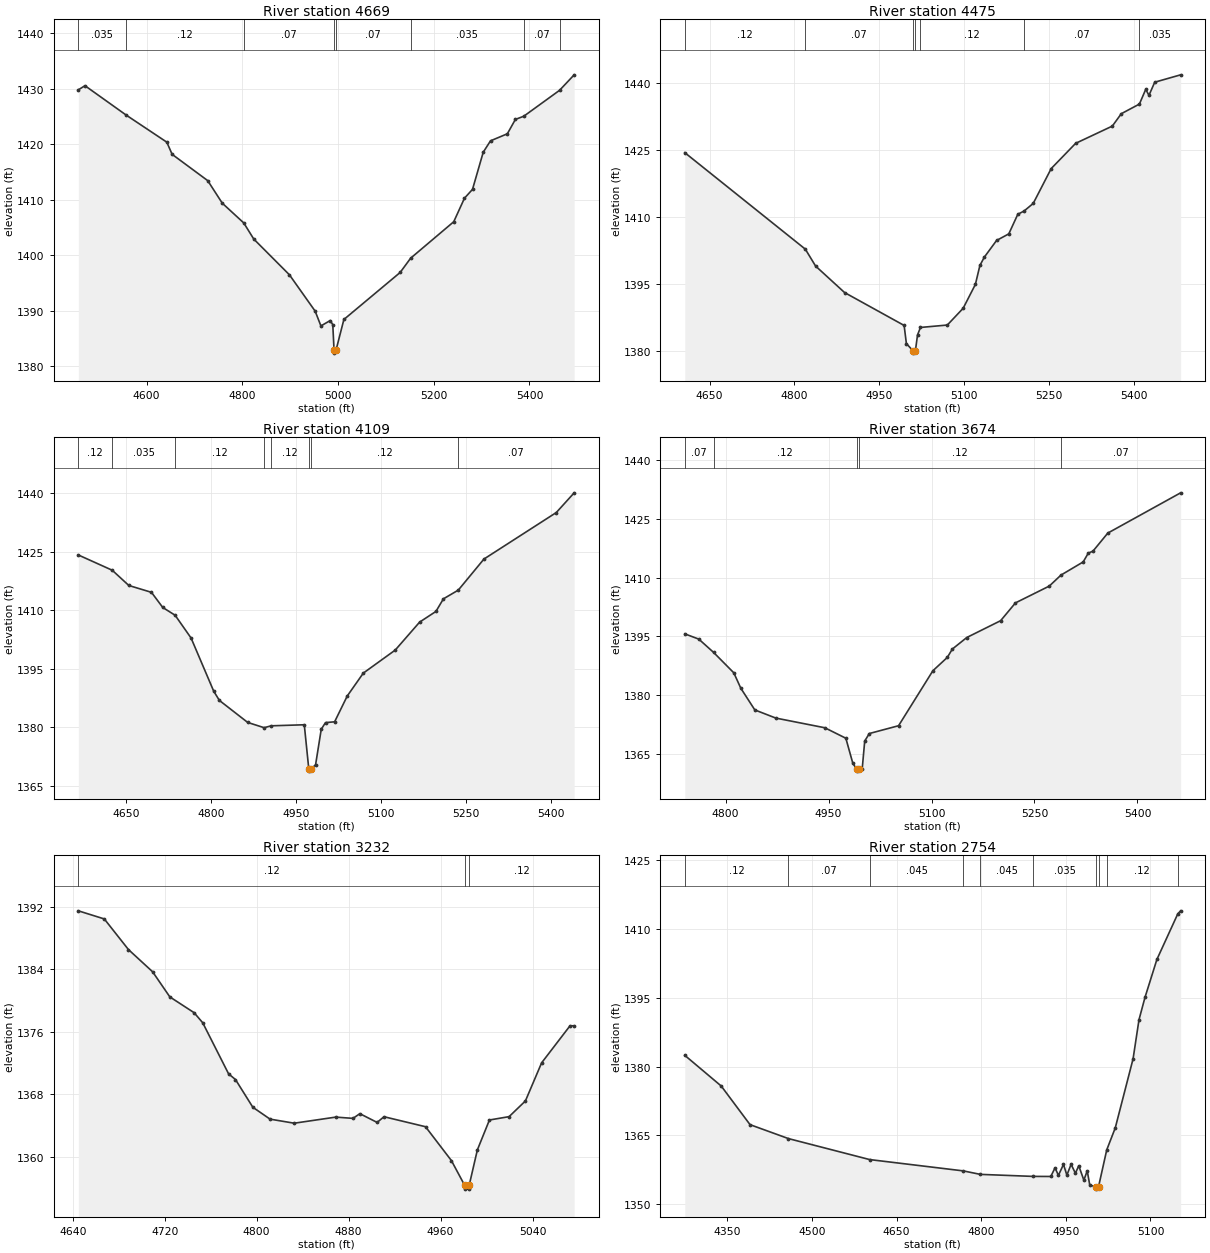
Type RM Length L Ch R = 1,4669,194,194,194
BEGIN DESCRIPTION:
Stream0226_DS 6.0
END DESCRIPTION:
XS GIS Cut Line= 3
      2094231.95     13899147.37      2094737.79     13898956.68
      2095181.53     13898736.15
#Sta/Elev= 30
  4457.3 1429.82  4471.2 1430.56  4557.6 1425.25  4642.2 1420.39  4653.3 1418.20
  4727.7 1413.46  4758.1 1409.40  4803.0 1405.84  4823.9 1402.94  4898.4 1396.50
  4952.2 1389.95  4964.2 1387.29  4983.7 1388.26  4989.0 1387.52  4991.7 1382.89
  4992.0 1382.39  4995.7 1382.89  5012.2 1388.45  5129.8 1396.92  5151.7 1399.49
  5241.8 1406.06  5264.2 1410.30  5281.0 1411.89  5303.4 1418.58  5318.6 1420.63
  5353.8 1421.90  5370.6 1424.49  5388.1 1425.06  5462.9 1429.73  5493.4 1432.52
#Mann=8,-1,0
  4457.3   0.035       0  4557.6    0.12       0  4803.0    0.07       0
  4991.7    0.05       0  4995.7    0.07       0  5151.7   0.035       0
  5388.1    0.07       0  5462.9   0.035       0
Bank Sta=4991.7,4995.7
Exp/Cntr=0.3,0.1

Type RM Length L Ch R = 1,4475,366,366,366
BEGIN DESCRIPTION:
Stream0226_DS 5.0
END DESCRIPTION:
XS GIS Cut Line= 3
      2094439.05     13899212.74      2094823.68     13899128.27
      2095243.65     13898889.51
#Sta/Elev= 30
  4606.2 1424.39  4819.4 1402.81  4837.5 1399.04  4888.7 1393.12  4994.1 1385.76
  4998.1 1381.70  5010.0 1380.07  5010.3 1379.57  5014.0 1380.07  5017.8 1383.63
  5023.0 1385.31  5070.5 1385.85  5098.5 1389.60  5120.1 1394.93  5128.1 1399.17
  5136.0 1401.04  5157.6 1404.76  5179.2 1406.23  5195.1 1410.60  5206.4 1411.36
  5222.4 1413.04  5254.2 1420.83  5297.4 1426.47  5362.3 1430.33  5378.2 1433.10
  5410.2 1435.25  5421.4 1438.55  5427.1 1437.21  5437.3 1440.14  5483.1 1441.79
#Mann=7,-1,0
  4606.2    0.12       0  4819.4    0.07       0  5010.0    0.05       0
  5014.0    0.07       0  5023.0    0.12       0  5206.4    0.07       0
  5410.2   0.035       0
Bank Sta=5010,5014
Exp/Cntr=0.3,0.1

Type RM Length L Ch R = 1,4109,435,435,435
BEGIN DESCRIPTION:
Stream0226_DS 4.0
END DESCRIPTION:
XS GIS Cut Line= 3
      2094485.84     13899420.99      2094925.00     13899425.00
      2095264.52     13899150.17
#Sta/Elev= 30
  4565.5 1424.18  4625.4 1420.26  4654.7 1416.35  4694.7 1414.59  4714.7 1410.70
  4736.5 1408.71  4764.7 1402.86  4804.7 1389.21  4814.7 1386.85  4864.7 1381.20
  4893.7 1379.85  4906.3 1380.33  4964.7 1380.60  4972.7 1369.20  4972.9 1368.70
  4976.7 1369.20  4984.7 1370.37  4994.7 1379.46  5002.2 1381.15  5018.3 1381.36
  5040.6 1387.98  5069.0 1393.86  5125.4 1399.77  5168.5 1406.95  5197.3 1409.69
  5210.5 1412.92  5236.8 1415.16  5282.1 1423.13  5410.0 1435.08  5441.5 1440.13
#Mann=8,-1,0
  4565.5    0.12       0  4625.4   0.035       0  4736.5    0.12       0
  4893.7    0.07       0  4906.3    0.12       0  4972.7    0.05       0
  4976.7    0.12       0  5236.8    0.07       0
Bank Sta=4972.7,4976.7
Exp/Cntr=0.3,0.1

Type RM Length L Ch R = 1,3674,442,442,442
BEGIN DESCRIPTION:
Stream0226_DS 3.0
END DESCRIPTION:
XS GIS Cut Line= 3
      2094774.96     13899774.99      2095025.00     13899825.00
      2095370.85     13899510.73
#Sta/Elev= 30
  4740.6 1395.64  4761.0 1394.30  4782.6 1390.90  4812.0 1385.70  4822.2 1381.77
  4842.6 1376.24  4873.2 1374.16  4944.6 1371.69  4975.2 1369.02  4985.4 1362.62
  4991.0 1361.13  4991.3 1360.63  4995.0 1361.13  4999.0 1361.13  5002.7 1368.30
  5009.4 1370.22  5052.0 1372.21  5102.0 1386.23  5123.0 1389.63  5130.4 1391.77
  5151.4 1394.71  5200.7 1399.00  5222.3 1403.54  5271.6 1407.83  5288.6 1410.63
  5321.0 1413.99  5328.4 1416.24  5335.2 1416.73  5356.8 1421.34  5462.9 1431.61
#Mann=5,-1,0
  4740.6    0.07       0  4782.6    0.12       0  4991.0    0.05       0
  4995.0    0.12       0  5288.6    0.07       0
Bank Sta=4991,4995
Exp/Cntr=0.3,0.1

Type RM Length L Ch R = 1,3232,478,478,478
BEGIN DESCRIPTION:
Stream0226_DS 2.0
END DESCRIPTION:
XS GIS Cut Line= 3
      2095024.98     13900325.01      2095325.00     13900125.00
      2095375.01     13900074.99
#Sta/Elev= 30
  4644.9 1391.48  4667.5 1390.44  4688.5 1386.52  4709.5 1383.68  4724.5 1380.46
  4745.6 1378.44  4753.1 1377.15  4775.6 1370.61  4781.6 1369.88  4796.7 1366.33
  4811.7 1364.81  4832.7 1364.29  4868.8 1365.07  4883.8 1364.91  4889.8 1365.51
  4904.8 1364.39  4910.8 1365.12  4946.9 1363.84  4969.4 1359.51  4980.9 1356.35
  4981.2 1355.85  4984.7 1355.85  4984.9 1356.35  4992.0 1360.87  5002.5 1364.70
  5019.6 1365.13  5033.8 1367.14  5047.9 1372.02  5072.6 1376.76  5076.2 1376.76
#Mann=3,-1,0
  4644.9    0.12       0  4980.9    0.05       0  4984.9    0.12       0
Bank Sta=4980.9,4984.9
Exp/Cntr=0.3,0.1

Type RM Length L Ch R = 1,2754,0,0,0
BEGIN DESCRIPTION:
Stream0226_DS 1.0
END DESCRIPTION:
XS GIS Cut Line= 3
      2095325.00     13900724.99      2095725.00     13900125.00
      2095675.01     13899975.02
#Sta/Elev= 30
  4274.3 1382.45  4338.9 1375.75  4390.0 1367.32  4458.1 1364.28  4602.1 1359.70
  4768.1 1357.23  4798.4 1356.47  4891.2 1356.03  4923.3 1356.01  4930.8 1357.90
  4936.8 1356.26  4945.8 1358.64  4951.8 1356.31  4959.3 1358.66  4966.9 1356.72
  4972.9 1358.35  4981.9 1355.21  4987.9 1357.24  4992.4 1354.13  5003.9 1353.75
  5004.2 1353.25  5007.9 1353.75  5022.5 1361.82  5037.6 1366.61  5069.2 1381.69
  5079.7 1390.23  5090.3 1395.09  5111.4 1403.37  5148.5 1413.34  5153.5 1413.99
#Mann=10,-1,0
  4274.3    0.12       0  4458.1    0.07       0  4602.1   0.045       0
  4768.1   0.035       0  4798.4   0.045       0  4891.2   0.035       0
  5003.9   0.035       0  5007.9   0.035       0  5022.5    0.12       0
  5148.5    0.07       0
Bank Sta=5003.9,5007.9
Exp/Cntr=0.3,0.1

Chan Stop Cuts=-1