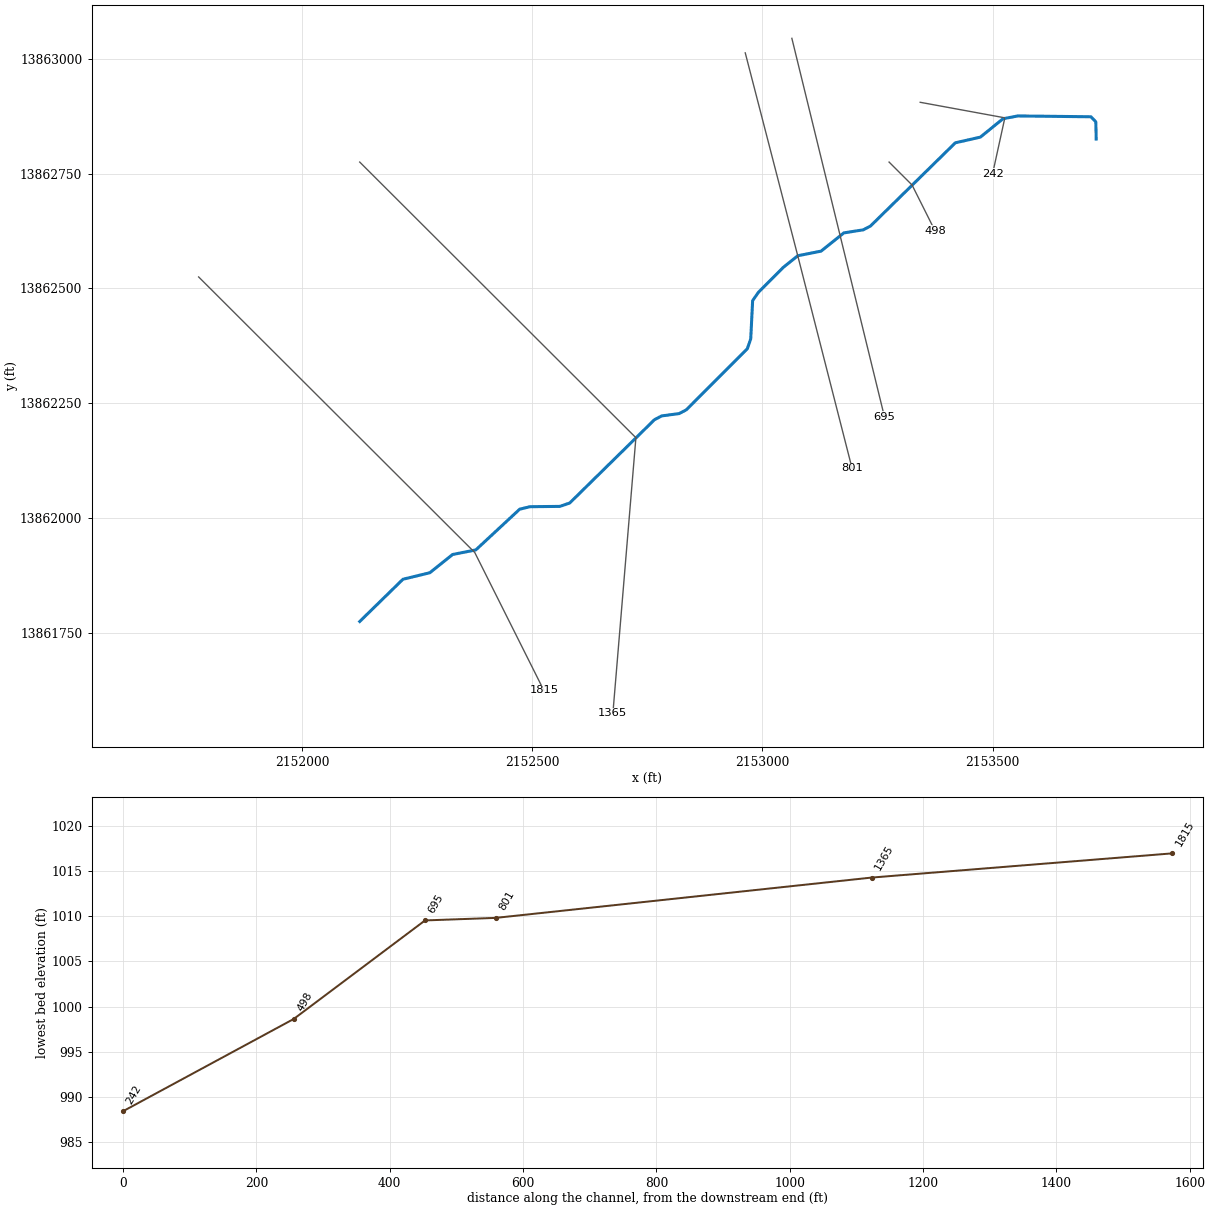
--- Stream0227_DS.prj (project) ---

Proj Title=Stream0227_DS Base Level Engineering
Current Plan=p01
Default Exp/Contr=0.3,0.1
English Units
Geom File=g01
Flow File=f01
Plan File=p01
BEGIN DESCRIPTION:
Stream0227_DS
END DESCRIPTION:

--- Stream0227_DS.p01 (plan) ---

Plan Title=Multiple Run
Short Identifier=Multiple
Geom File=g01
Flow File=f01
Subcritical Flow
K Sum by GR= 0
Std Step Tol= 0.01
Critical Tol= 0.01
Num of Std Step Trials= 20
Max Error Tol= 0.3
Flow Tol Ratio= 0.001
Split Flow NTrial= 30
Split Flow Tol= 0.02
Split Flow Ratio= 0.02
Log Output Level= 0
Friction Slope Method= 1
Unsteady Friction Slope Method= 2
Unsteady Bridges Friction Slope Method= 1
Parabolic Critical Depth
Global Vel Dist=  1 , 1 , 1
Global Log Level= 0
CheckData=True
Encroach Param= -1, 0, 0, 0
BEGIN DESCRIPTION:
Multiple Run
END DESCRIPTION:

--- Stream0227_DS.f01 (steady flow) ---

Flow Title=Multiple
Number of Profiles=7
Profile Names=10-year,25-year,50-year,1pct_min,100-year,1pct_plu,500-year
River Rch & RM= Stream0227_DS,Reach-1,1815
     451     725     973     635    1267    2529    2122
Boundary for River Rch & Prof#=Stream0227_DS,Reach-1,1
Up Type=0
Dn Type=3
Dn Slope=0.005
Boundary for River Rch & Prof#=Stream0227_DS,Reach-1,2
Up Type=0
Dn Type=3
Dn Slope=0.005
Boundary for River Rch & Prof#=Stream0227_DS,Reach-1,3
Up Type=0
Dn Type=3
Dn Slope=0.005
Boundary for River Rch & Prof#=Stream0227_DS,Reach-1,4
Up Type=0
Dn Type=3
Dn Slope=0.005
Boundary for River Rch & Prof#=Stream0227_DS,Reach-1,5
Up Type=0
Dn Type=3
Dn Slope=0.005
Boundary for River Rch & Prof#=Stream0227_DS,Reach-1,6
Up Type=0
Dn Type=3
Dn Slope=0.005
Boundary for River Rch & Prof#=Stream0227_DS,Reach-1,7
Up Type=0
Dn Type=3
Dn Slope=0.005

--- Stream0227_DS.g01 (geometry) ---

Geom Title=Existing Conditions

River Reach=Stream0227_DS,Reach-1
Reach XY= 30
      2152125.00     13861775.00      2152218.92     13861866.91
      2152277.19     13861881.09      2152326.73     13861920.81
      2152377.29     13861930.85      2152472.58     13862019.46
      2152495.06     13862024.86      2152559.78     13862025.53
      2152581.17     13862032.86      2152765.32     13862214.22
      2152781.05     13862222.47      2152818.95     13862227.53
      2152834.68     13862235.78      2152967.14     13862368.83
      2152974.47     13862390.22      2152978.61     13862473.51
      2152991.44     13862491.79      2153044.76     13862545.42
      2153076.62     13862571.06      2153127.19     13862581.10
      2153176.74     13862620.81      2153218.96     13862627.50
      2153234.68     13862635.76      2153418.94     13862816.86
      2153473.25     13862829.22      2153522.65     13862869.29
      2153554.85     13862875.37      2153713.57     13862873.57
      2153724.17     13862862.57      2153725.00     13862825.00

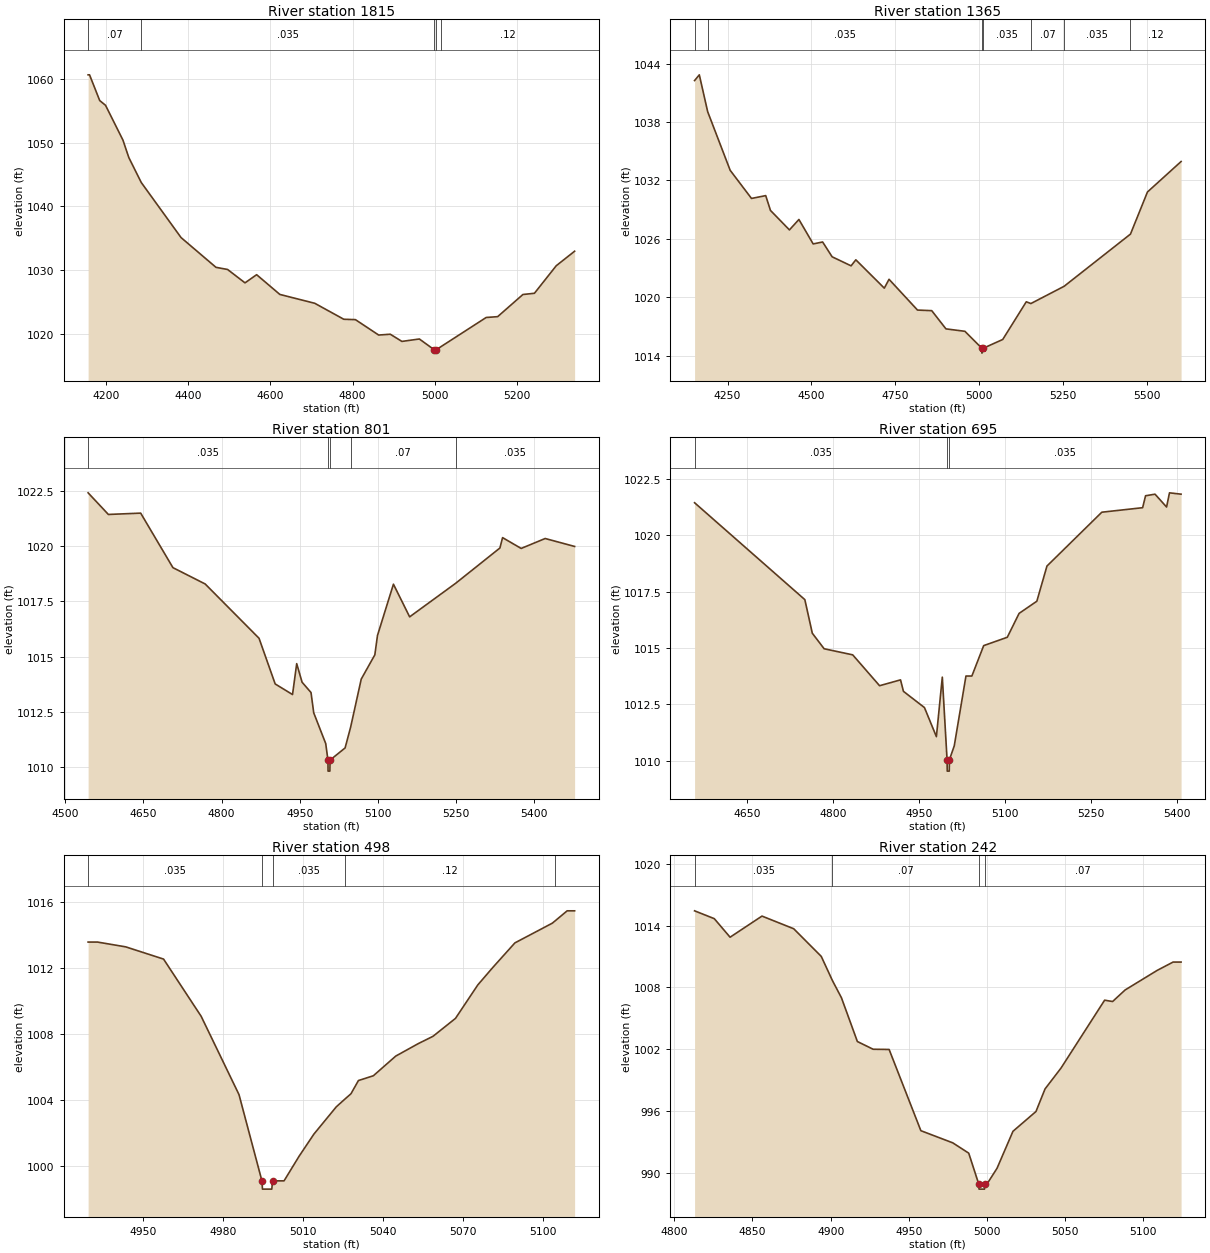
Type RM Length L Ch R = 1,1815,450,450,450
BEGIN DESCRIPTION:
Stream0227_DS 4.0
END DESCRIPTION:
XS GIS Cut Line= 3
      2151775.03     13862524.97      2152375.00     13861925.00
      2152525.00     13861625.00
#Sta/Elev= 30
  4156.3 1060.66  4159.8 1060.66  4184.5 1056.62  4198.7 1055.87  4241.1 1050.40
  4255.3 1047.67  4285.7 1043.74  4382.5 1035.09  4467.4 1030.42  4495.7 1030.08
  4538.1 1027.98  4566.4 1029.26  4622.9 1026.16  4707.8 1024.77  4778.5 1022.26
  4806.8 1022.20  4863.4 1019.78  4891.6 1019.91  4919.9 1018.78  4962.4 1019.16
  4999.2 1017.44  4999.5 1016.94  5003.2 1017.44  5015.5 1017.98  5125.0 1022.54
  5152.9 1022.67  5214.4 1026.15  5242.4 1026.34  5295.5 1030.67  5340.2 1032.95
#Mann=5,-1,0
  4156.3    0.07       0  4285.7   0.035       0  4999.2   0.035       0
  5003.2   0.035       0  5015.5    0.12       0
Bank Sta=4999.2,5003.2
Exp/Cntr=0.3,0.1

Type RM Length L Ch R = 1,1365,564,564,564
BEGIN DESCRIPTION:
Stream0227_DS 3.0
END DESCRIPTION:
XS GIS Cut Line= 3
      2152125.00     13862775.00      2152725.00     13862175.00
      2152675.00     13861575.01
#Sta/Elev= 30
  4151.7 1042.25  4165.8 1042.84  4190.7 1039.06  4257.8 1033.04  4321.4 1030.15
  4363.8 1030.44  4378.0 1028.92  4434.5 1026.92  4462.8 1027.99  4505.3 1025.48
  4533.5 1025.68  4561.8 1024.16  4618.4 1023.23  4632.5 1023.85  4717.4 1020.94
  4731.5 1021.85  4816.4 1018.69  4858.8 1018.63  4901.2 1016.76  4957.8 1016.51
  5008.3 1014.77  5008.5 1014.27  5012.3 1014.77  5070.5 1015.67  5140.7 1019.54
  5154.5 1019.36  5253.5 1021.13  5451.4 1026.49  5502.0 1030.81  5602.3 1033.94
#Mann=7,-1,0
  4151.7    0.12       0  4190.7   0.035       0  5008.3   0.035       0
  5012.3   0.035       0  5154.5    0.07       0  5253.5   0.035       0
  5451.4    0.12       0
Bank Sta=5008.3,5012.3
Exp/Cntr=0.3,0.1

Type RM Length L Ch R = 1,801,106,106,106
BEGIN DESCRIPTION:
Stream0227_DS 2.0
END DESCRIPTION:
XS GIS Cut Line= 3
      2152962.56     13863012.67      2153076.62     13862571.06
      2153194.70     13862108.08
#Sta/Elev= 30
  4543.9 1022.42  4582.8 1021.44  4644.8 1021.50  4706.7 1019.03  4768.6 1018.29
  4872.0 1015.83  4903.0 1013.76  4936.3 1013.28  4944.3 1014.68  4954.6 1013.84
  4971.8 1013.37  4977.0 1012.45  5000.0 1011.06  5004.3 1010.31  5004.5 1009.81
  5008.0 1009.81  5008.3 1010.31  5037.2 1010.86  5047.9 1011.81  5068.2 1013.98
  5094.3 1015.08  5099.4 1015.96  5130.0 1018.28  5161.1 1016.80  5249.4 1018.32
  5334.4 1019.92  5339.5 1020.39  5375.2 1019.90  5421.3 1020.35  5477.8 1019.99
#Mann=5,-1,0
  4543.9   0.035       0  5004.3   0.035       0  5008.3   0.035       0
  5047.9    0.07       0  5249.4   0.035       0
Bank Sta=5004.3,5008.3
Exp/Cntr=0.3,0.1

Type RM Length L Ch R = 1,695,197,197,197
BEGIN DESCRIPTION:
Stream0227_DS 1.5
END DESCRIPTION:
XS GIS Cut Line= 2
      2153063.84     13863044.29      2153264.91     13862220.88
#Sta/Elev= 30
  4559.2 1021.44  4751.3 1017.14  4764.3 1015.65  4784.9 1014.96  4834.7 1014.69
  4881.5 1013.32  4918.0 1013.58  4923.1 1013.07  4959.7 1012.35  4980.5 1011.06
  4990.8 1013.70  4999.1 1010.03  4999.4 1009.53  5002.9 1009.53  5003.1 1010.03
  5011.6 1010.65  5032.0 1013.75  5042.3 1013.75  5062.9 1015.10  5104.0 1015.47
  5124.6 1016.53  5155.5 1017.07  5173.1 1018.63  5268.7 1021.02  5339.8 1021.22
  5344.9 1021.75  5361.4 1021.82  5381.5 1021.25  5386.6 1021.88  5406.8 1021.82
#Mann=3,-1,0
  4559.2   0.035       0  4999.1   0.035       0  5003.1   0.035       0
Bank Sta=4999.1,5003.1
Exp/Cntr=0.3,0.1

Type RM Length L Ch R = 1,498,256,256,256
BEGIN DESCRIPTION:
Stream0227_DS 1.0
END DESCRIPTION:
XS GIS Cut Line= 3
      2153275.01     13862774.99      2153325.00     13862725.00
      2153375.00     13862625.00
#Sta/Elev= 30
  4929.3 1013.58  4932.8 1013.58  4943.4 1013.29  4957.6 1012.55  4971.7 1009.09
  4985.9 1004.35  4994.5  999.13  4994.7  998.63  4998.2  998.63  4998.5  999.13
  5000.0  999.13  5002.8  999.13  5008.4 1000.61  5014.0 1001.96  5022.4 1003.61
  5025.5 1004.06  5027.9 1004.40  5030.7 1005.20  5036.3 1005.49  5044.7 1006.68
  5053.1 1007.43  5058.7 1007.88  5067.1 1008.96  5075.5 1010.99  5081.1 1012.04
  5089.4 1013.53  5103.4 1014.72  5104.4 1014.85  5109.0 1015.47  5111.8 1015.47
#Mann=5,-1,0
  4929.3   0.035       0  4994.5   0.035       0  4998.5   0.035       0
  5025.5    0.12       0  5104.4   0.035       0
Bank Sta=4994.5,4998.5
Exp/Cntr=0.3,0.1

Type RM Length L Ch R = 1,242,0,0,0
BEGIN DESCRIPTION:
Stream0227_DS 0.1
END DESCRIPTION:
XS GIS Cut Line= 3
      2153342.64     13862905.08      2153526.55     13862871.25
      2153500.01     13862750.03
#Sta/Elev= 30
  4813.0 1015.43  4825.6 1014.67  4835.7 1012.87  4856.1 1014.92  4876.4 1013.69
  4894.0 1011.01  4901.1 1008.68  4906.9 1007.00  4917.1 1002.75  4927.2 1002.00
  4937.4 1001.98  4957.7  994.10  4978.1  992.92  4988.3  991.92  4994.7  988.93
  4994.9  988.43  4998.4  988.43  4998.7  988.93  5000.0  988.93  5006.4  990.45
  5016.6  994.04  5031.3  995.96  5037.1  998.15  5047.3 1000.17  5075.2 1006.76
  5080.3 1006.63  5088.3 1007.75  5108.8 1009.65  5119.0 1010.46  5124.1 1010.46
#Mann=4,-1,0
  4813.0   0.035       0  4901.1    0.07       0  4994.7    0.05       0
  4998.7    0.07       0
Bank Sta=4994.7,4998.7
Exp/Cntr=0.3,0.1

Chan Stop Cuts=-1