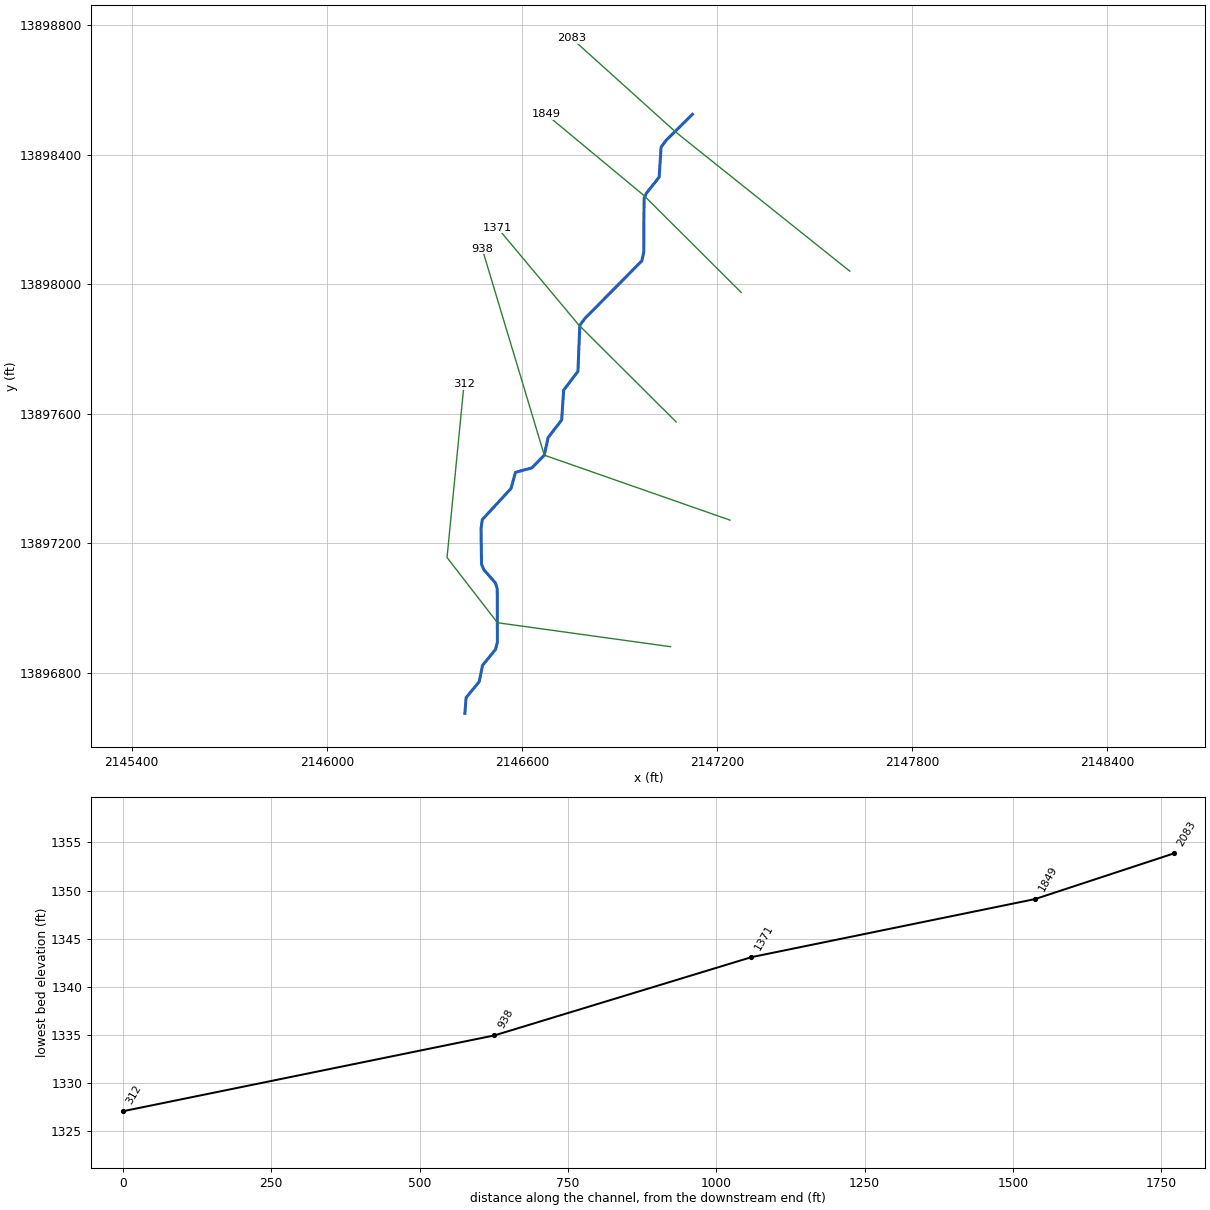
--- Stream0229_DS.prj (project) ---

Proj Title=Stream0229_DS Base Level Engineering
Current Plan=p01
Default Exp/Contr=0.3,0.1
English Units
Geom File=g01
Flow File=f01
Plan File=p01
BEGIN DESCRIPTION:
Stream0229_DS
END DESCRIPTION:

--- Stream0229_DS.p01 (plan) ---

Plan Title=Multiple Run
Short Identifier=Multiple
Geom File=g01
Flow File=f01
Subcritical Flow
K Sum by GR= 0
Std Step Tol= 0.01
Critical Tol= 0.01
Num of Std Step Trials= 20
Max Error Tol= 0.3
Flow Tol Ratio= 0.001
Split Flow NTrial= 30
Split Flow Tol= 0.02
Split Flow Ratio= 0.02
Log Output Level= 0
Friction Slope Method= 1
Unsteady Friction Slope Method= 2
Unsteady Bridges Friction Slope Method= 1
Parabolic Critical Depth
Global Vel Dist=  1 , 1 , 1
Global Log Level= 0
CheckData=True
Encroach Param= -1, 0, 0, 0
BEGIN DESCRIPTION:
Multiple Run
END DESCRIPTION:

--- Stream0229_DS.f01 (steady flow) ---

Flow Title=Multiple
Number of Profiles=7
Profile Names=10-year,25-year,50-year,1pct_min,100-year,1pct_plu,500-year
River Rch & RM= Stream0229_DS,Reach-1,2083
     644    1055    1435     948    1891    3773    3243
Boundary for River Rch & Prof#=Stream0229_DS,Reach-1,1
Up Type=0
Dn Type=3
Dn Slope=0.005
Boundary for River Rch & Prof#=Stream0229_DS,Reach-1,2
Up Type=0
Dn Type=3
Dn Slope=0.005
Boundary for River Rch & Prof#=Stream0229_DS,Reach-1,3
Up Type=0
Dn Type=3
Dn Slope=0.005
Boundary for River Rch & Prof#=Stream0229_DS,Reach-1,4
Up Type=0
Dn Type=3
Dn Slope=0.005
Boundary for River Rch & Prof#=Stream0229_DS,Reach-1,5
Up Type=0
Dn Type=3
Dn Slope=0.005
Boundary for River Rch & Prof#=Stream0229_DS,Reach-1,6
Up Type=0
Dn Type=3
Dn Slope=0.005
Boundary for River Rch & Prof#=Stream0229_DS,Reach-1,7
Up Type=0
Dn Type=3
Dn Slope=0.005

--- Stream0229_DS.g01 (geometry) ---

Geom Title=Existing Conditions

River Reach=Stream0229_DS,Reach-1
Reach XY= 30
      2147125.00     13898525.00      2147044.52     13898445.20
      2147028.56     13898423.52      2147022.64     13898330.98
      2146983.14     13898281.06      2146976.22     13898264.50
      2146975.29     13898099.88      2146969.54     13898072.55
      2146794.61     13897895.16      2146778.54     13897873.53
      2146772.73     13897730.94      2146728.86     13897673.40
      2146722.67     13897580.96      2146681.15     13897527.15
      2146669.24     13897472.47      2146631.04     13897433.17
      2146580.65     13897419.37      2146566.70     13897369.26
      2146478.54     13897273.53      2146474.54     13897245.17
      2146476.21     13897135.51      2146483.14     13897118.95
      2146519.25     13897077.33      2146524.48     13897059.78
      2146524.94     13896895.03      2146519.29     13896872.65
      2146479.17     13896823.27      2146469.05     13896772.75
      2146428.60     13896723.51      2146425.00     13896675.00

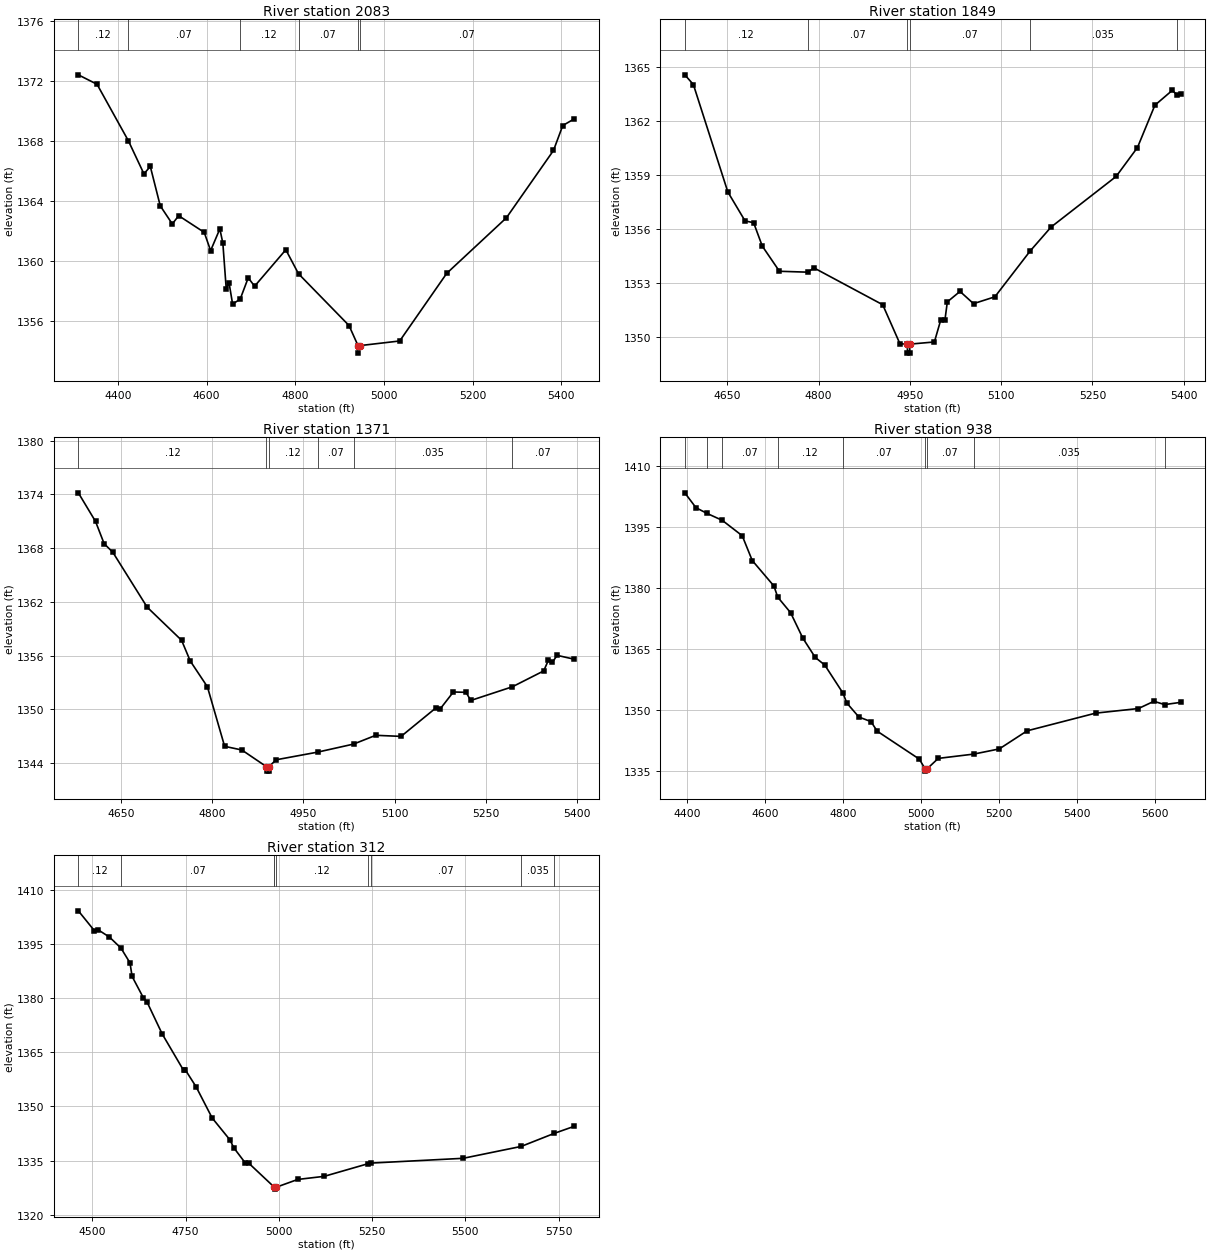
Type RM Length L Ch R = 1,2083,234,234,234
BEGIN DESCRIPTION:
Stream0229_DS 3.0
END DESCRIPTION:
XS GIS Cut Line= 3
      2147609.21     13898040.60      2147075.14     13898468.93
      2146753.65     13898759.70
#Sta/Elev= 30
  4310.6 1372.41  4352.8 1371.78  4423.5 1368.01  4458.5 1365.81  4472.9 1366.30
  4495.3 1363.68  4522.5 1362.47  4536.9 1363.02  4594.5 1361.91  4608.9 1360.69
  4629.7 1362.14  4636.5 1361.19  4644.1 1358.15  4650.5 1358.54  4658.5 1357.13
  4675.6 1357.46  4693.7 1358.88  4708.1 1358.32  4778.5 1360.75  4807.1 1359.15
  4921.0 1355.70  4941.3 1354.36  4941.6 1353.86  4945.3 1354.36  5035.3 1354.67
  5141.4 1359.18  5275.9 1362.88  5382.1 1367.37  5403.0 1369.03  5428.7 1369.47
#Mann=6,-1,0
  4310.6    0.12       0  4423.5    0.07       0  4675.6    0.12       0
  4807.1    0.07       0  4941.3    0.05       0  4945.3    0.07       0
Bank Sta=4941.3,4945.3
Exp/Cntr=0.3,0.1

Type RM Length L Ch R = 1,1849,478,478,478
BEGIN DESCRIPTION:
Stream0229_DS 2.0
END DESCRIPTION:
XS GIS Cut Line= 3
      2147274.98     13897975.02      2146975.00     13898275.00
      2146675.04     13898524.97
#Sta/Elev= 30
  4580.3 1364.59  4594.4 1364.05  4651.0 1358.08  4679.3 1356.47  4693.4 1356.37
  4707.6 1355.07  4735.8 1353.67  4782.6 1353.62  4792.4 1353.86  4905.5 1351.81
  4933.8 1349.64  4946.0 1349.62  4946.2 1349.12  4949.7 1349.12  4950.0 1349.62
  4990.4 1349.74  5001.0 1350.98  5007.8 1350.98  5011.7 1351.97  5032.5 1352.55
  5054.7 1351.87  5089.8 1352.25  5147.6 1354.79  5182.2 1356.13  5289.0 1358.94
  5324.1 1360.55  5352.7 1362.90  5381.4 1363.73  5388.4 1363.49  5395.0 1363.54
#Mann=6,-1,0
  4580.3    0.12       0  4782.6    0.07       0  4946.0    0.05       0
  4950.0    0.07       0  5147.6   0.035       0  5388.4    0.07       0
Bank Sta=4946,4950
Exp/Cntr=0.3,0.1

Type RM Length L Ch R = 1,1371,433,433,433
BEGIN DESCRIPTION:
Stream0229_DS 1.0
END DESCRIPTION:
XS GIS Cut Line= 3
      2147075.01     13897574.99      2146775.00     13897875.00
      2146524.99     13898175.01
#Sta/Elev= 30
  4580.0 1374.17  4608.3 1370.97  4622.4 1368.49  4636.6 1367.54  4693.1 1361.40
  4749.7 1357.70  4763.9 1355.39  4792.1 1352.51  4820.4 1345.86  4848.7 1345.45
  4889.1 1343.59  4889.4 1343.09  4892.9 1343.09  4893.1 1343.59  4905.3 1344.36
  4973.1 1345.21  5032.3 1346.11  5068.7 1347.09  5110.4 1346.97  5167.6 1350.15
  5174.1 1349.99  5196.3 1351.93  5217.1 1351.89  5224.9 1350.98  5293.3 1352.51
  5344.7 1354.28  5352.5 1355.48  5359.0 1355.24  5366.8 1356.02  5394.8 1355.59
#Mann=6,-1,0
  4580.0    0.12       0  4889.1    0.05       0  4893.1    0.12       0
  4973.1    0.07       0  5032.3   0.035       0  5293.3    0.07       0
Bank Sta=4889.1,4893.1
Exp/Cntr=0.3,0.1

Type RM Length L Ch R = 1,938,626,626,626
BEGIN DESCRIPTION:
Stream0229_DS 0.5
END DESCRIPTION:
XS GIS Cut Line= 3
      2147240.72     13897271.78      2146669.24     13897472.47
      2146477.96     13898110.62
#Sta/Elev= 30
  4394.3 1403.40  4423.0 1399.74  4450.9 1398.36  4490.5 1396.63  4541.6 1392.85
  4567.3 1386.76  4622.9 1380.49  4632.7 1377.75  4665.6 1373.94  4697.1 1367.67
  4728.9 1362.93  4753.3 1361.06  4800.0 1354.16  4809.9 1351.72  4840.9 1348.27
  4871.9 1347.15  4887.9 1344.79  4995.9 1337.92  5011.1 1335.47  5011.3 1334.97
  5015.1 1335.47  5044.4 1338.10  5135.6 1339.16  5201.0 1340.43  5272.4 1344.88
  5448.2 1349.23  5557.9 1350.36  5597.7 1352.14  5625.2 1351.33  5666.2 1351.88
#Mann=9,-1,0
  4394.3    0.07       0  4450.9    0.12       0  4490.5    0.07       0
  4632.7    0.12       0  4800.0    0.07       0  5011.1    0.05       0
  5015.1    0.07       0  5135.6   0.035       0  5625.2    0.07       0
Bank Sta=5011.1,5015.1
Exp/Cntr=0.3,0.1

Type RM Length L Ch R = 1,312,0,0,0
BEGIN DESCRIPTION:
Stream0229_DS 0.0
END DESCRIPTION:
XS GIS Cut Line= 4
      2147057.68     13896880.93      2146525.20     13896954.94
      2146370.00     13897156.29      2146422.24     13897691.13
#Sta/Elev= 30
  4462.4 1404.13  4505.5 1398.63  4515.6 1398.87  4545.9 1396.86  4576.6 1393.83
  4600.9 1389.73  4606.5 1385.98  4636.7 1380.07  4646.8 1378.85  4687.2 1370.05
  4744.5 1359.98  4749.5 1360.06  4778.1 1355.43  4821.2 1346.79  4869.0 1340.71
  4879.0 1338.57  4909.3 1334.43  4919.4 1334.27  4987.9 1327.62  4988.1 1327.60
  4988.4 1327.10  4992.1 1327.60  5050.6 1329.78  5121.6 1330.64  5240.2 1334.17
  5245.7 1334.30  5494.1 1335.63  5649.6 1338.92  5738.4 1342.54  5791.6 1344.48
#Mann=9,-1,0
  4462.4    0.12       0  4576.6    0.07       0  4987.9    0.12       0
  4988.1    0.05       0  4992.1    0.12       0  5240.2   0.035       0
  5245.7    0.07       0  5649.6   0.035       0  5738.4    0.07       0
Bank Sta=4988.1,4992.1
Exp/Cntr=0.3,0.1

Chan Stop Cuts=-1