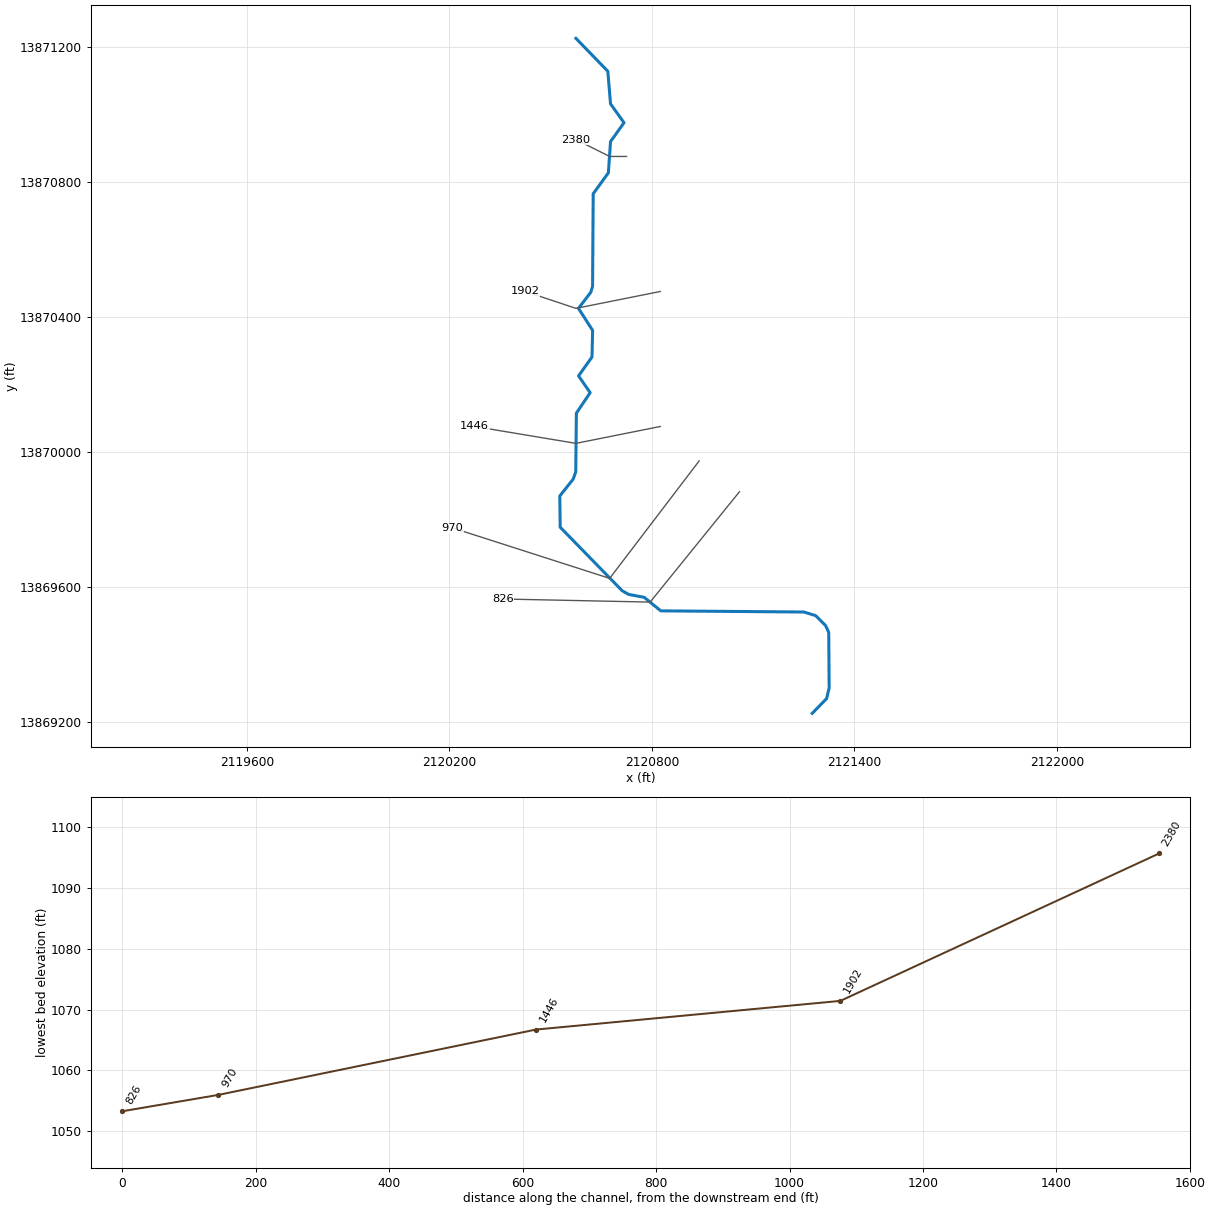
--- Stream0232_DS.prj (project) ---

Proj Title=Stream0232_DS Base Level Engineering
Current Plan=p01
Default Exp/Contr=0.3,0.1
English Units
Geom File=g01
Flow File=f01
Plan File=p01
BEGIN DESCRIPTION:
Stream0232_DS
END DESCRIPTION:

--- Stream0232_DS.p01 (plan) ---

Plan Title=Multiple Run
Short Identifier=Multiple
Geom File=g01
Flow File=f01
Subcritical Flow
K Sum by GR= 0
Std Step Tol= 0.01
Critical Tol= 0.01
Num of Std Step Trials= 20
Max Error Tol= 0.3
Flow Tol Ratio= 0.001
Split Flow NTrial= 30
Split Flow Tol= 0.02
Split Flow Ratio= 0.02
Log Output Level= 0
Friction Slope Method= 1
Unsteady Friction Slope Method= 2
Unsteady Bridges Friction Slope Method= 1
Parabolic Critical Depth
Global Vel Dist=  1 , 1 , 1
Global Log Level= 0
CheckData=True
Encroach Param= -1, 0, 0, 0
BEGIN DESCRIPTION:
Multiple Run
END DESCRIPTION:

--- Stream0232_DS.f01 (steady flow) ---

Flow Title=Multiple
Number of Profiles=7
Profile Names=10-year,25-year,50-year,1pct_min,100-year,1pct_plu,500-year
River Rch & RM= Stream0232_DS,Reach-1,2380
     721    1192    1630    1082    2159    4308    3743
Boundary for River Rch & Prof#=Stream0232_DS,Reach-1,1
Up Type=0
Dn Type=3
Dn Slope=0.005
Boundary for River Rch & Prof#=Stream0232_DS,Reach-1,2
Up Type=0
Dn Type=3
Dn Slope=0.005
Boundary for River Rch & Prof#=Stream0232_DS,Reach-1,3
Up Type=0
Dn Type=3
Dn Slope=0.005
Boundary for River Rch & Prof#=Stream0232_DS,Reach-1,4
Up Type=0
Dn Type=3
Dn Slope=0.005
Boundary for River Rch & Prof#=Stream0232_DS,Reach-1,5
Up Type=0
Dn Type=3
Dn Slope=0.005
Boundary for River Rch & Prof#=Stream0232_DS,Reach-1,6
Up Type=0
Dn Type=3
Dn Slope=0.005
Boundary for River Rch & Prof#=Stream0232_DS,Reach-1,7
Up Type=0
Dn Type=3
Dn Slope=0.005

--- Stream0232_DS.g01 (geometry) ---

Geom Title=Existing Conditions

River Reach=Stream0232_DS,Reach-1
Reach XY= 30
      2120575.00     13871225.00      2120669.54     13871127.45
      2120677.55     13871030.89      2120717.44     13870975.00
      2120677.55     13870919.11      2120671.15     13870826.60
      2120626.22     13870764.50      2120624.34     13870490.16
      2120618.98     13870472.55      2120582.56     13870425.00
      2120624.48     13870359.78      2120622.64     13870280.89
      2120582.80     13870224.90      2120617.21     13870175.10
      2120576.38     13870114.57      2120574.48     13869940.22
      2120566.85     13869918.94      2120527.16     13869869.02
      2120528.46     13869776.50      2120711.78     13869588.62
      2120731.03     13869577.50      2120777.17     13869568.86
      2120826.55     13869528.75      2121250.22     13869525.33
      2121285.18     13869514.68      2121314.68     13869485.18
      2121324.02     13869464.74      2121325.24     13869299.90
      2121317.57     13869268.65      2121275.00     13869225.00

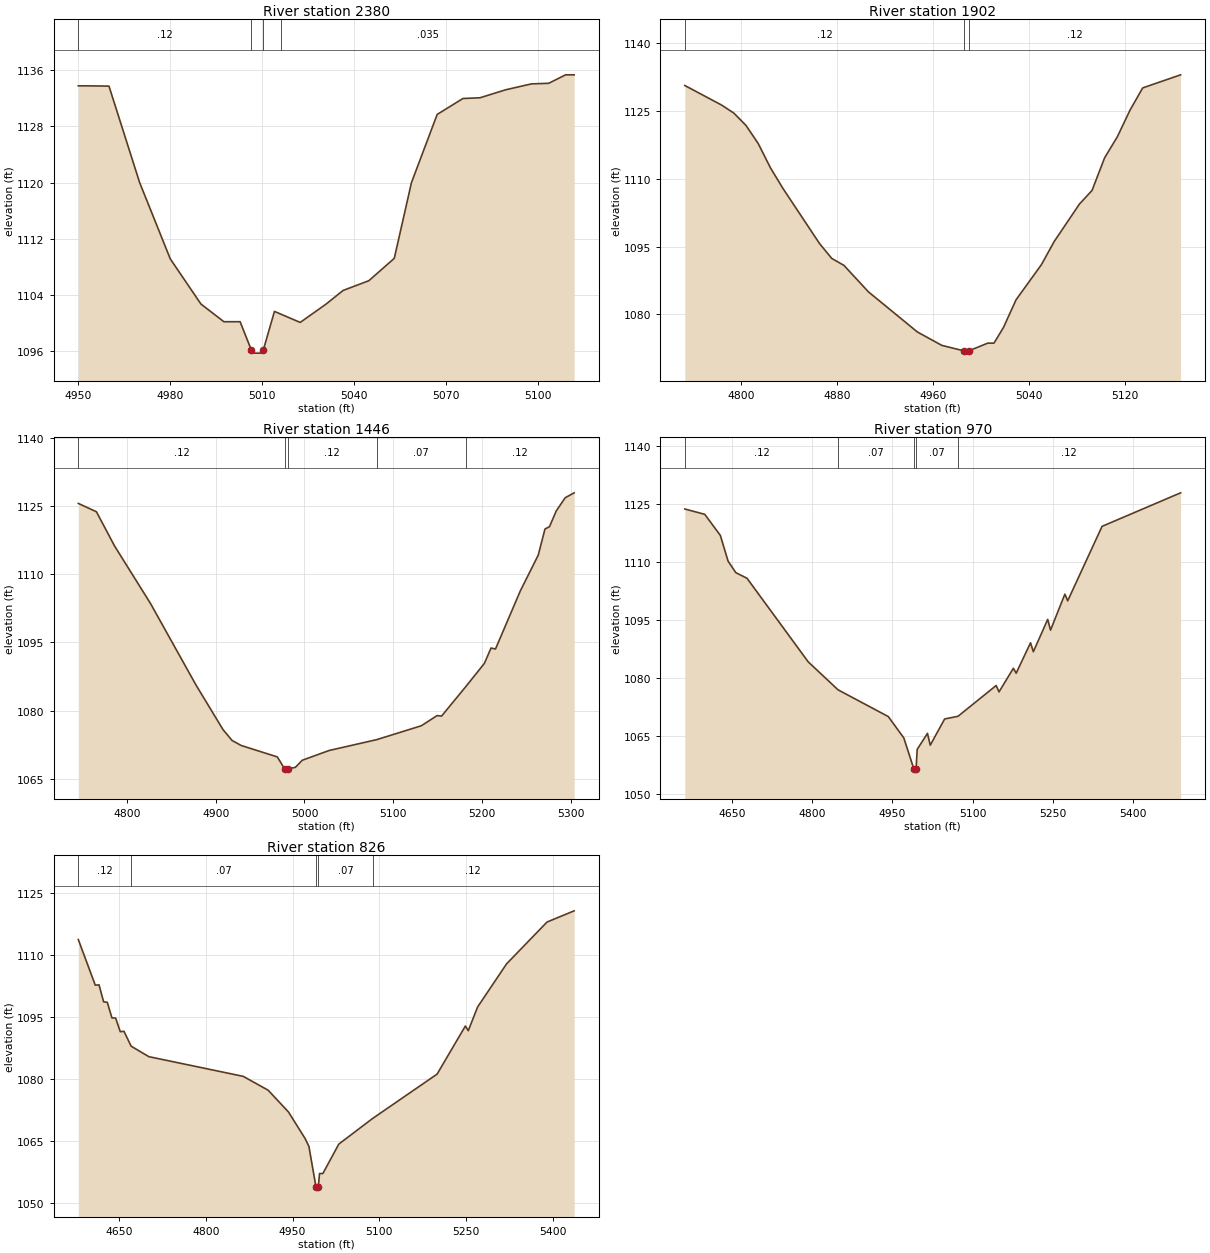
Type RM Length L Ch R = 1,2380,478,478,478
BEGIN DESCRIPTION:
Stream0232_DS 5.0
END DESCRIPTION:
XS GIS Cut Line= 3
      2120725.04     13870875.00      2120675.00     13870875.00
      2120575.04     13870924.98
#Sta/Elev= 29
  4950.0 1133.80  4952.5 1133.80  4960.0 1133.76  4970.0 1120.01  4980.0 1109.12
  4990.0 1102.68  4997.5 1100.15  5000.0 1100.15  5002.8 1100.15  5006.4 1096.17
  5006.7 1095.67  5010.2 1095.67  5010.4 1096.17  5014.0 1101.62  5016.2 1101.21
  5022.4 1100.05  5030.8 1102.65  5036.4 1104.61  5044.8 1106.00  5053.1 1109.19
  5058.7 1119.98  5067.1 1129.72  5075.5 1131.99  5081.1 1132.10  5089.5 1133.24
  5097.9 1134.08  5103.5 1134.16  5109.0 1135.37  5111.8 1135.37
#Mann=4,-1,0
  4950.0    0.12       0  5006.4    0.05       0  5010.4    0.12       0
  5016.2   0.035       0
Bank Sta=5006.4,5010.4
Exp/Cntr=0.3,0.1

Type RM Length L Ch R = 1,1902,456,456,456
BEGIN DESCRIPTION:
Stream0232_DS 4.0
END DESCRIPTION:
XS GIS Cut Line= 3
      2120825.01     13870475.00      2120575.00     13870425.00
      2120424.98     13870475.01
#Sta/Elev= 30
  4753.0 1130.69  4783.6 1126.36  4793.8 1124.59  4804.0 1121.84  4814.2 1117.82
  4824.4 1112.44  4834.6 1107.96  4865.2 1095.71  4875.4 1092.40  4885.6 1090.85
  4906.0 1084.99  4946.8 1076.10  4967.2 1073.13  4985.6 1071.92  4985.8 1071.42
  4989.3 1071.42  4989.6 1071.92  5005.4 1073.63  5010.6 1073.63  5018.5 1077.10
  5029.0 1083.24  5050.1 1091.00  5060.7 1096.11  5081.8 1104.43  5092.3 1107.45
  5102.8 1114.69  5113.4 1119.34  5123.9 1125.21  5134.5 1130.15  5166.1 1133.05
#Mann=3,-1,0
  4753.0    0.12       0  4985.6    0.05       0  4989.6    0.12       0
Bank Sta=4985.6,4989.6
Exp/Cntr=0.3,0.1

Type RM Length L Ch R = 1,1446,476,476,476
BEGIN DESCRIPTION:
Stream0232_DS 3.0
END DESCRIPTION:
XS GIS Cut Line= 3
      2120825.05     13870075.01      2120575.00     13870025.00
      2120275.04     13870074.99
#Sta/Elev= 30
  4745.0 1125.53  4765.4 1123.70  4785.8 1116.20  4826.6 1103.47  4877.6 1085.66
  4908.2 1075.82  4918.4 1073.44  4928.6 1072.35  4969.4 1069.83  4977.6 1067.21
  4977.9 1066.71  4981.6 1067.21  4989.8 1067.55  4997.5 1069.10  5027.9 1071.25
  5081.3 1073.62  5131.8 1076.68  5149.5 1078.91  5154.6 1078.80  5181.7 1085.23
  5202.8 1090.36  5210.4 1093.76  5215.4 1093.54  5243.3 1106.27  5263.6 1114.17
  5271.2 1119.91  5276.3 1120.42  5283.9 1123.88  5294.0 1126.78  5304.1 1127.86
#Mann=5,-1,0
  4745.0    0.12       0  4977.6    0.05       0  4981.6    0.12       0
  5081.3    0.07       0  5181.7    0.12       0
Bank Sta=4977.6,4981.6
Exp/Cntr=0.3,0.1

Type RM Length L Ch R = 1,970,144,144,144
BEGIN DESCRIPTION:
Stream0232_DS 2.0
END DESCRIPTION:
XS GIS Cut Line= 3
      2120940.11     13869972.95      2120675.00     13869625.00
      2120209.27     13869774.57
#Sta/Elev= 30
  4562.1 1123.67  4599.4 1122.30  4628.5 1116.86  4643.0 1110.21  4657.5 1107.23
  4678.4 1105.78  4792.7 1084.20  4848.5 1076.97  4942.4 1070.06  4971.4 1064.55
  4990.3 1056.47  4990.5 1055.97  4994.3 1056.47  4996.4 1061.59  5015.6 1065.72
  5020.8 1062.67  5047.7 1069.44  5072.7 1070.14  5144.0 1078.08  5149.3 1076.43
  5176.1 1082.53  5181.4 1081.27  5208.2 1089.12  5213.5 1086.81  5240.3 1095.16
  5245.6 1092.39  5272.4 1101.68  5277.7 1099.96  5341.9 1119.19  5488.7 1127.85
#Mann=5,-1,0
  4562.1    0.12       0  4848.5    0.07       0  4990.3    0.05       0
  4994.3    0.07       0  5072.7    0.12       0
Bank Sta=4990.3,4994.3
Exp/Cntr=0.3,0.1

Type RM Length L Ch R = 1,826,0,0,0
BEGIN DESCRIPTION:
Stream0232_DS 1.0
END DESCRIPTION:
XS GIS Cut Line= 3
      2121059.44     13869881.56      2120794.88     13869554.72
      2120358.08     13869563.85
#Sta/Elev= 30
  4579.5 1113.81  4608.8 1102.76  4615.3 1102.83  4623.2 1098.73  4629.6 1098.59
  4637.6 1094.82  4644.0 1094.78  4652.0 1091.48  4658.4 1091.57  4670.8 1087.96
  4701.5 1085.41  4864.6 1080.64  4907.8 1077.27  4943.0 1071.97  4971.7 1065.54
  4978.2 1063.66  4990.5 1053.78  4990.8 1053.28  4994.5 1053.78  4996.6 1057.07
  5002.4 1057.07  5029.9 1064.20  5088.2 1070.40  5199.9 1081.18  5248.8 1092.85
  5253.8 1091.71  5269.9 1097.45  5320.0 1107.92  5390.0 1118.07  5436.9 1120.79
#Mann=5,-1,0
  4579.5    0.12       0  4670.8    0.07       0  4990.5    0.05       0
  4994.5    0.07       0  5088.2    0.12       0
Bank Sta=4990.5,4994.5
Exp/Cntr=0.3,0.1

Chan Stop Cuts=-1