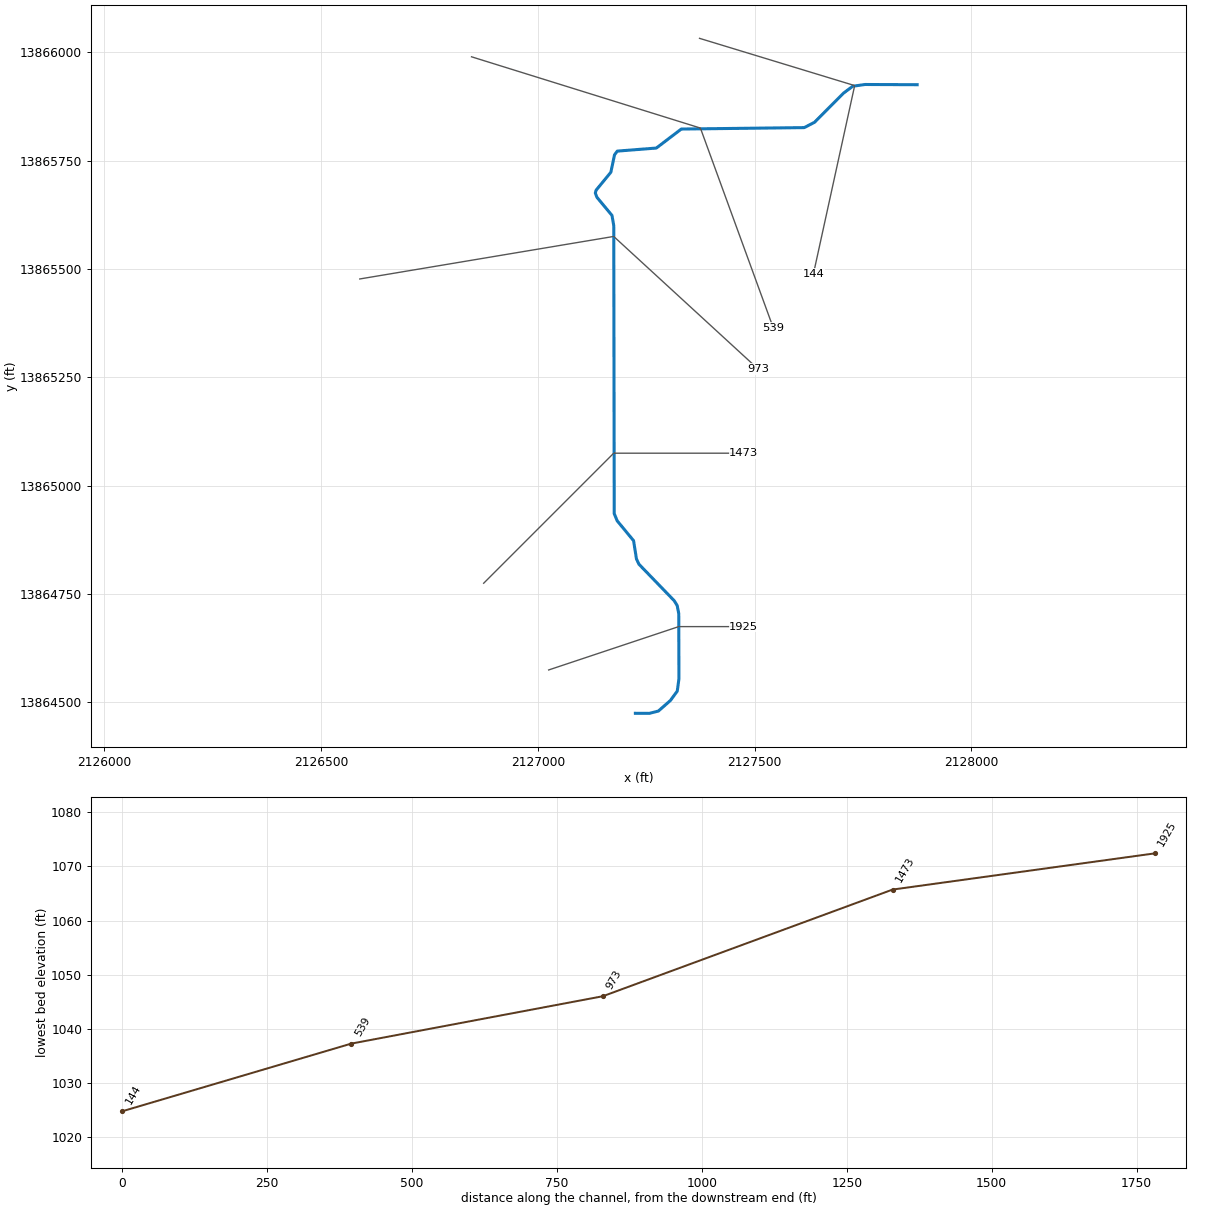
--- Stream0233_DS.prj (project) ---

Proj Title=Stream0233_DS Base Level Engineering
Current Plan=p01
Default Exp/Contr=0.3,0.1
English Units
Geom File=g01
Flow File=f01
Plan File=p01
BEGIN DESCRIPTION:
Stream0233_DS
END DESCRIPTION:

--- Stream0233_DS.p01 (plan) ---

Plan Title=Multiple Run
Short Identifier=Multiple
Geom File=g01
Flow File=f01
Subcritical Flow
K Sum by GR= 0
Std Step Tol= 0.01
Critical Tol= 0.01
Num of Std Step Trials= 20
Max Error Tol= 0.3
Flow Tol Ratio= 0.001
Split Flow NTrial= 30
Split Flow Tol= 0.02
Split Flow Ratio= 0.02
Log Output Level= 0
Friction Slope Method= 1
Unsteady Friction Slope Method= 2
Unsteady Bridges Friction Slope Method= 1
Parabolic Critical Depth
Global Vel Dist=  1 , 1 , 1
Global Log Level= 0
CheckData=True
Encroach Param= -1, 0, 0, 0
BEGIN DESCRIPTION:
Multiple Run
END DESCRIPTION:

--- Stream0233_DS.f01 (steady flow) ---

Flow Title=Multiple
Number of Profiles=7
Profile Names=10-year,25-year,50-year,1pct_min,100-year,1pct_plu,500-year
River Rch & RM= Stream0233_DS,Reach-1,1925
     706    1172    1607    1071    2137    4263    3731
Boundary for River Rch & Prof#=Stream0233_DS,Reach-1,1
Up Type=0
Dn Type=3
Dn Slope=0.005
Boundary for River Rch & Prof#=Stream0233_DS,Reach-1,2
Up Type=0
Dn Type=3
Dn Slope=0.005
Boundary for River Rch & Prof#=Stream0233_DS,Reach-1,3
Up Type=0
Dn Type=3
Dn Slope=0.005
Boundary for River Rch & Prof#=Stream0233_DS,Reach-1,4
Up Type=0
Dn Type=3
Dn Slope=0.005
Boundary for River Rch & Prof#=Stream0233_DS,Reach-1,5
Up Type=0
Dn Type=3
Dn Slope=0.005
Boundary for River Rch & Prof#=Stream0233_DS,Reach-1,6
Up Type=0
Dn Type=3
Dn Slope=0.005
Boundary for River Rch & Prof#=Stream0233_DS,Reach-1,7
Up Type=0
Dn Type=3
Dn Slope=0.005

--- Stream0233_DS.g01 (geometry) ---

Geom Title=Existing Conditions

River Reach=Stream0233_DS,Reach-1
Reach XY= 30
      2127225.00     13864475.00      2127257.08     13864474.84
      2127277.95     13864480.13      2127305.72     13864504.44
      2127321.63     13864526.26      2127325.45     13864554.77
      2127325.04     13864705.02      2127321.45     13864723.53
      2127314.50     13864734.79      2127233.16     13864818.95
      2127227.50     13864831.04      2127220.78     13864873.25
      2127183.09     13864918.92      2127176.20     13864935.50
      2127175.11     13865600.12      2127170.98     13865623.53
      2127136.45     13865665.12      2127132.52     13865675.04
      2127134.39     13865681.67      2127168.42     13865723.11
      2127176.90     13865763.26      2127183.29     13865771.84
      2127273.33     13865778.89      2127330.93     13865822.74
      2127614.56     13865826.06      2127638.31     13865838.40
      2127704.85     13865905.35      2127726.45     13865921.49
      2127754.79     13865925.51      2127875.00     13865925.00

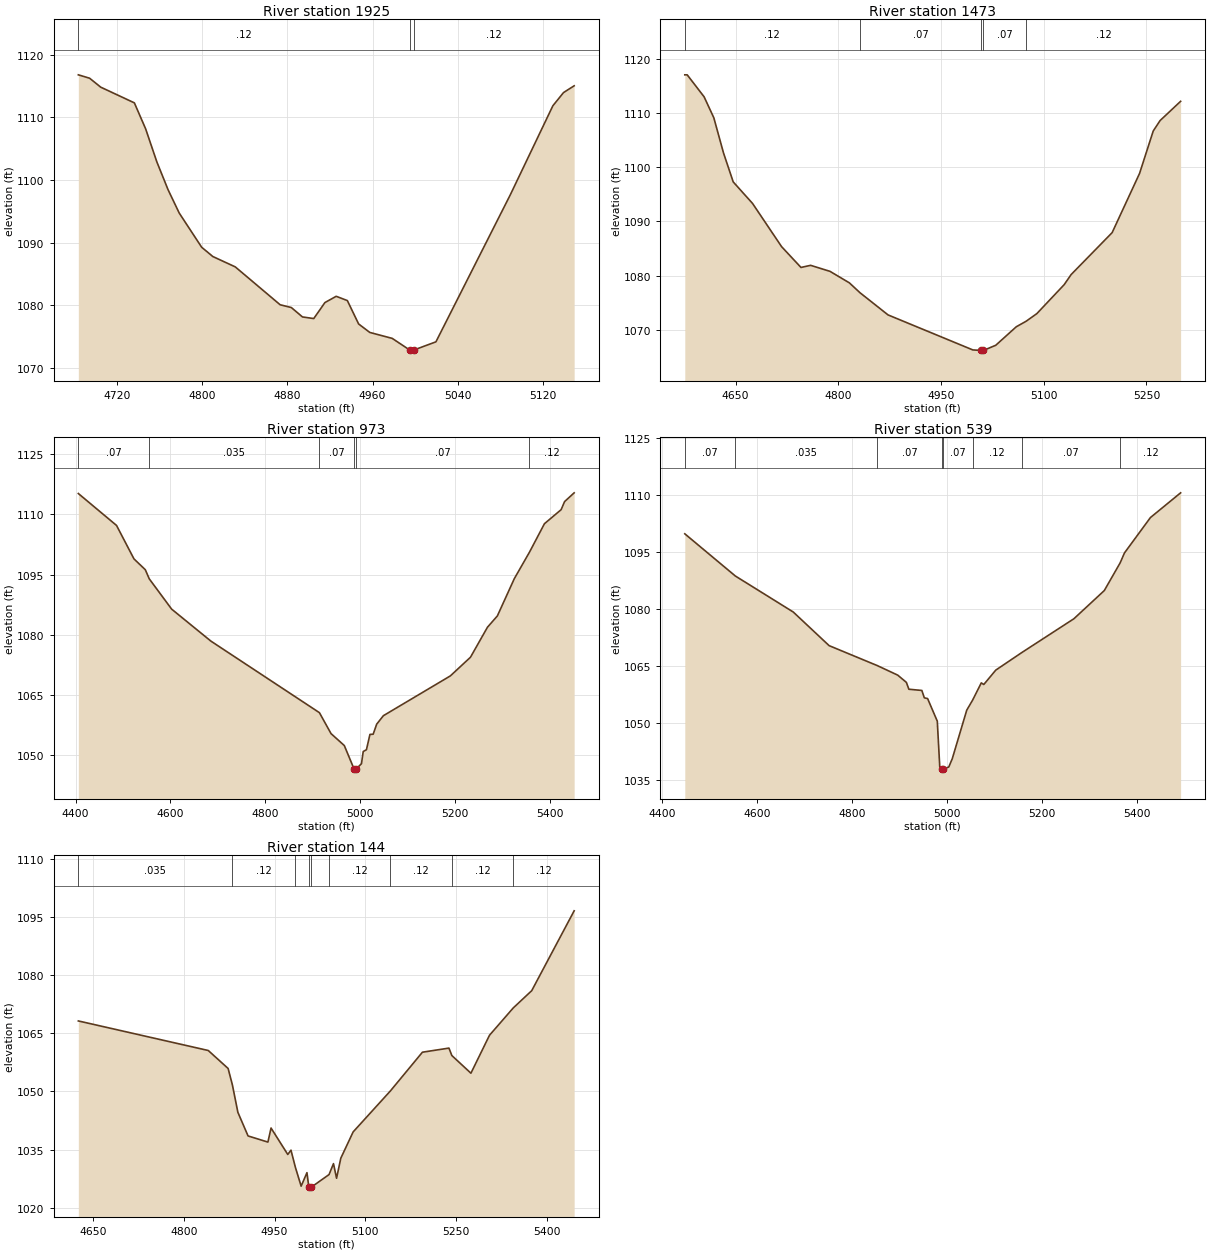
Type RM Length L Ch R = 1,1925,452,452,452
BEGIN DESCRIPTION:
Stream0233_DS 4.0
END DESCRIPTION:
XS GIS Cut Line= 3
      2127024.97     13864574.99      2127325.00     13864675.00
      2127475.04     13864675.00
#Sta/Elev= 30
  4683.3 1116.77  4693.9 1116.23  4704.4 1114.80  4736.0 1112.30  4746.6 1108.16
  4757.1 1102.91  4767.7 1098.45  4778.2 1094.73  4799.3 1089.28  4809.8 1087.80
  4830.9 1086.15  4873.1 1080.11  4883.6 1079.67  4894.1 1078.17  4904.7 1077.91
  4915.2 1080.46  4925.8 1081.46  4936.3 1080.78  4946.9 1077.05  4957.4 1075.70
  4978.5 1074.75  4994.9 1072.90  4995.2 1072.40  4998.7 1072.40  4998.9 1072.90
  5019.6 1074.20  5089.6 1097.66  5129.6 1111.84  5139.6 1113.94  5149.6 1115.02
#Mann=3,-1,0
  4683.3    0.12       0  4994.9    0.05       0  4998.9    0.12       0
Bank Sta=4994.9,4998.9
Exp/Cntr=0.3,0.1

Type RM Length L Ch R = 1,1473,500,500,500
BEGIN DESCRIPTION:
Stream0233_DS 3.0
END DESCRIPTION:
XS GIS Cut Line= 3
      2126875.03     13864775.03      2127175.00     13865075.00
      2127474.97     13865075.00
#Sta/Elev= 30
  4575.8 1117.01  4579.3 1117.01  4604.0 1112.96  4618.2 1109.09  4632.3 1102.63
  4646.5 1097.28  4674.8 1093.30  4717.2 1085.34  4745.5 1081.51  4759.6 1081.90
  4787.9 1080.79  4816.2 1078.67  4831.6 1076.86  4872.7 1072.76  4996.5 1066.31
  5008.0 1066.22  5008.3 1065.72  5011.8 1065.72  5012.0 1066.22  5030.0 1067.17
  5060.0 1070.58  5074.4 1071.60  5090.0 1073.00  5130.0 1078.35  5140.0 1080.19
  5200.0 1087.93  5240.0 1098.83  5260.0 1106.66  5270.0 1108.58  5300.0 1112.13
#Mann=5,-1,0
  4575.8    0.12       0  4831.6    0.07       0  5008.0    0.05       0
  5012.0    0.07       0  5074.4    0.12       0
Bank Sta=5008,5012
Exp/Cntr=0.3,0.1

Type RM Length L Ch R = 1,973,434,434,434
BEGIN DESCRIPTION:
Stream0233_DS 2.0
END DESCRIPTION:
XS GIS Cut Line= 3
      2126589.22     13865476.90      2127175.00     13865575.00
      2127507.99     13865269.25
#Sta/Elev= 30
  4405.6 1115.21  4486.2 1107.25  4523.0 1098.91  4546.9 1096.22  4555.2 1093.95
  4602.5 1086.39  4685.2 1078.43  4914.2 1060.59  4938.7 1055.37  4966.7 1052.40
  4987.4 1046.52  4987.6 1046.02  4991.4 1046.52  5002.9 1047.87  5006.6 1050.90
  5013.4 1051.36  5020.8 1055.17  5027.6 1055.22  5035.0 1057.72  5049.2 1059.84
  5190.4 1069.75  5232.9 1074.41  5268.7 1081.88  5289.6 1084.70  5325.4 1094.00
  5357.3 1100.58  5388.9 1107.68  5424.1 1111.18  5431.4 1113.19  5451.6 1115.38
#Mann=6,-1,0
  4405.6    0.07       0  4555.2   0.035       0  4914.2    0.07       0
  4987.4    0.05       0  4991.4    0.07       0  5357.3    0.12       0
Bank Sta=4987.4,4991.4
Exp/Cntr=0.3,0.1

Type RM Length L Ch R = 1,539,395,395,395
BEGIN DESCRIPTION:
Stream0233_DS 1.0
END DESCRIPTION:
XS GIS Cut Line= 3
      2126847.01     13865989.40      2127375.00     13865825.00
      2127543.10     13865363.98
#Sta/Elev= 30
  4448.4 1099.81  4554.7 1088.70  4676.7 1079.20  4752.2 1070.34  4853.6 1065.08
  4896.7 1062.56  4914.8 1060.66  4920.1 1058.85  4947.4 1058.53  4952.6 1056.59
  4959.5 1056.39  4979.9 1050.43  4985.1 1038.38  4988.9 1037.77  4989.2 1037.27
  4992.9 1037.77  5004.1 1038.37  5011.4 1040.53  5041.9 1053.34  5054.2 1055.97
  5072.5 1060.52  5077.8 1060.10  5103.0 1063.89  5157.7 1068.51  5267.5 1077.43
  5331.4 1084.85  5364.8 1092.15  5373.9 1094.77  5428.6 1104.10  5492.1 1110.61
#Mann=8,-1,0
  4448.4    0.07       0  4554.7   0.035       0  4853.6    0.07       0
  4988.9    0.05       0  4992.9    0.07       0  5054.2    0.12       0
  5157.7    0.07       0  5364.8    0.12       0
Bank Sta=4988.9,4992.9
Exp/Cntr=0.3,0.1

Type RM Length L Ch R = 1,144,0,0,0
BEGIN DESCRIPTION:
Stream0233_DS 0.0
END DESCRIPTION:
XS GIS Cut Line= 3
      2127372.97     13866031.98      2127730.84     13865922.98
      2127635.65     13865488.49
#Sta/Elev= 30
  4625.9 1068.19  4840.5 1060.56  4873.3 1055.92  4880.4 1051.65  4889.4 1044.61
  4906.2 1038.51  4939.0 1036.92  4944.2 1040.55  4971.8 1033.73  4977.1 1034.84
  4984.4 1030.41  4993.9 1025.55  5003.5 1029.03  5006.6 1025.28  5006.8 1024.78
  5010.6 1025.28  5040.0 1028.54  5047.3 1031.36  5052.4 1027.59  5059.4 1032.76
  5079.8 1039.55  5141.4 1050.14  5194.2 1060.12  5238.0 1061.18  5242.8 1059.26
  5274.3 1054.70  5305.0 1064.50  5344.2 1071.54  5374.7 1076.00  5444.8 1096.61
#Mann=9,-1,0
  4625.9   0.035       0  4880.4    0.12       0  4984.4   0.033       0
  5006.6   0.033       0  5010.6   0.033       0  5040.0    0.12       0
  5141.4    0.12       0  5242.8    0.12       0  5344.2    0.12       0
Bank Sta=5006.6,5010.6
Exp/Cntr=0.3,0.1

Chan Stop Cuts=-1