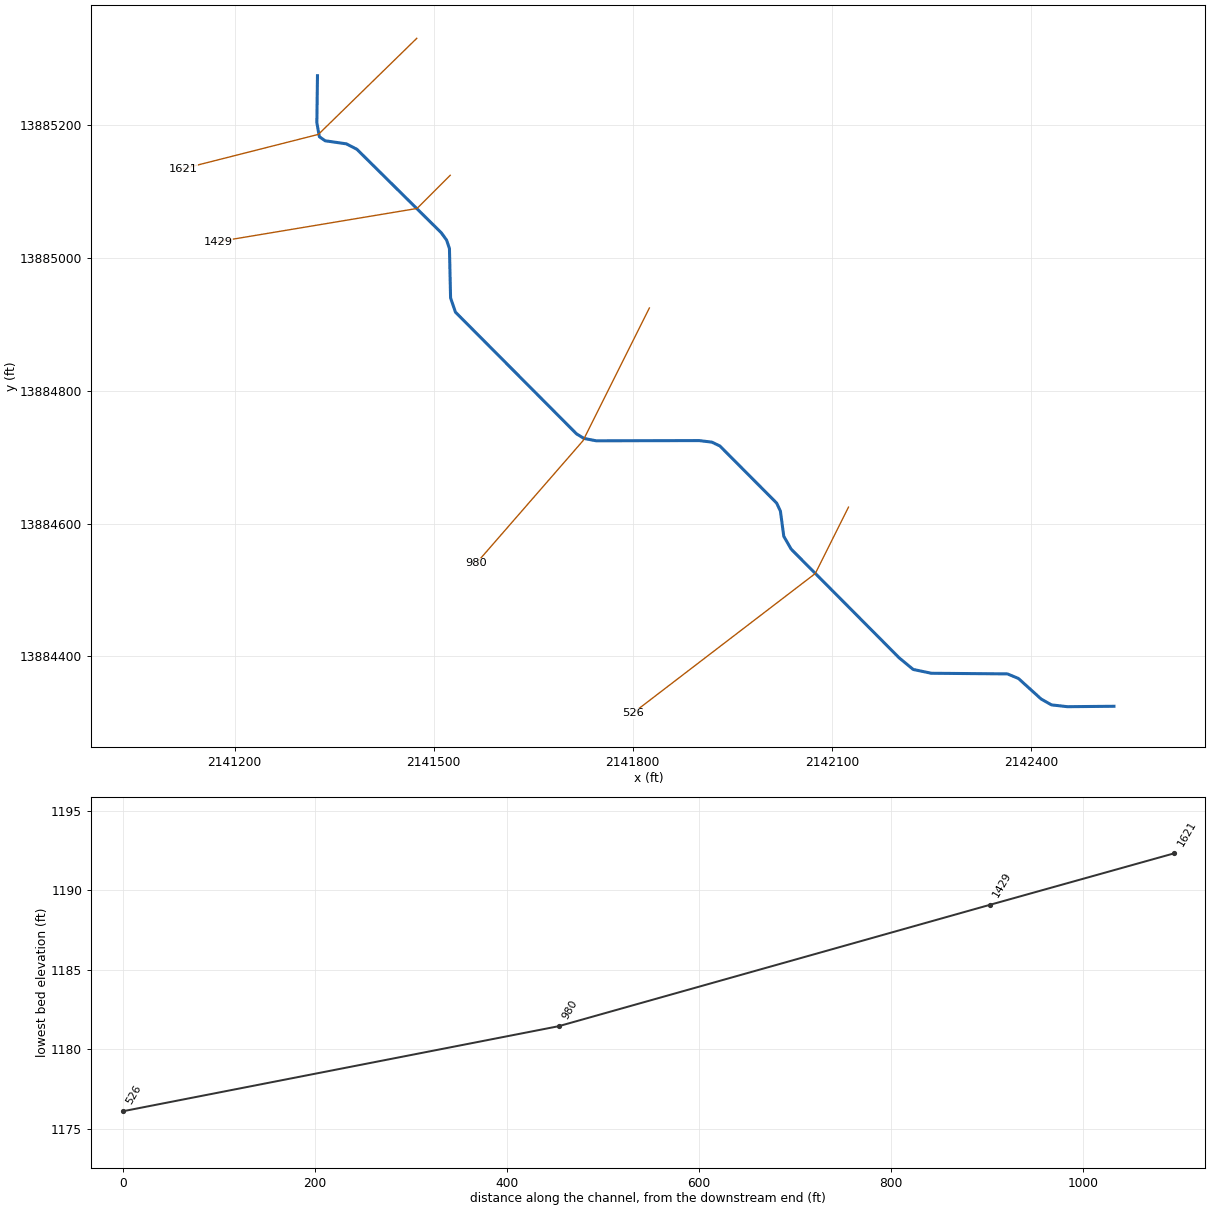
--- Stream0236_DS.prj (project) ---

Proj Title=Stream0236_DS Base Level Engineering
Current Plan=p01
Default Exp/Contr=0.3,0.1
English Units
Geom File=g01
Flow File=f01
Plan File=p01
BEGIN DESCRIPTION:
Stream0236_DS
END DESCRIPTION:

--- Stream0236_DS.p01 (plan) ---

Plan Title=Multiple Run
Short Identifier=Multiple
Geom File=g01
Flow File=f01
Subcritical Flow
K Sum by GR= 0
Std Step Tol= 0.01
Critical Tol= 0.01
Num of Std Step Trials= 20
Max Error Tol= 0.3
Flow Tol Ratio= 0.001
Split Flow NTrial= 30
Split Flow Tol= 0.02
Split Flow Ratio= 0.02
Log Output Level= 0
Friction Slope Method= 1
Unsteady Friction Slope Method= 2
Unsteady Bridges Friction Slope Method= 1
Parabolic Critical Depth
Global Vel Dist=  1 , 1 , 1
Global Log Level= 0
CheckData=True
Encroach Param= -1, 0, 0, 0
BEGIN DESCRIPTION:
Multiple Run
END DESCRIPTION:

--- Stream0236_DS.f01 (steady flow) ---

Flow Title=Multiple
Number of Profiles=7
Profile Names=10-year,25-year,50-year,1pct_min,100-year,1pct_plu,500-year
River Rch & RM= Stream0236_DS,Reach-1,1621
     824    1367    1874    1246    2485    4959    4322
Boundary for River Rch & Prof#=Stream0236_DS,Reach-1,1
Up Type=0
Dn Type=3
Dn Slope=0.005
Boundary for River Rch & Prof#=Stream0236_DS,Reach-1,2
Up Type=0
Dn Type=3
Dn Slope=0.005
Boundary for River Rch & Prof#=Stream0236_DS,Reach-1,3
Up Type=0
Dn Type=3
Dn Slope=0.005
Boundary for River Rch & Prof#=Stream0236_DS,Reach-1,4
Up Type=0
Dn Type=3
Dn Slope=0.005
Boundary for River Rch & Prof#=Stream0236_DS,Reach-1,5
Up Type=0
Dn Type=3
Dn Slope=0.005
Boundary for River Rch & Prof#=Stream0236_DS,Reach-1,6
Up Type=0
Dn Type=3
Dn Slope=0.005
Boundary for River Rch & Prof#=Stream0236_DS,Reach-1,7
Up Type=0
Dn Type=3
Dn Slope=0.005

--- Stream0236_DS.g01 (geometry) ---

Geom Title=Existing Conditions

River Reach=Stream0236_DS,Reach-1
Reach XY= 30
      2141325.00     13885275.00      2141324.06     13885204.20
      2141327.83     13885183.11      2141336.63     13885176.97
      2141368.53     13885172.35      2141384.40     13885164.13
      2141511.60     13885038.30      2141519.48     13885027.43
      2141523.83     13885014.52      2141525.53     13884940.22
      2141532.86     13884918.83      2141715.20     13884735.48
      2141726.46     13884728.54      2141744.98     13884724.96
      2141900.12     13884725.29      2141919.16     13884722.95
      2141931.21     13884717.20      2142016.85     13884631.07
      2142022.47     13884618.96      2142027.54     13884581.05
      2142038.63     13884561.79      2142201.47     13884397.86
      2142222.55     13884380.47      2142249.89     13884374.73
      2142364.50     13884373.79      2142381.07     13884366.90
      2142415.35     13884335.86      2142430.87     13884327.10
      2142454.74     13884324.37      2142525.00     13884325.00

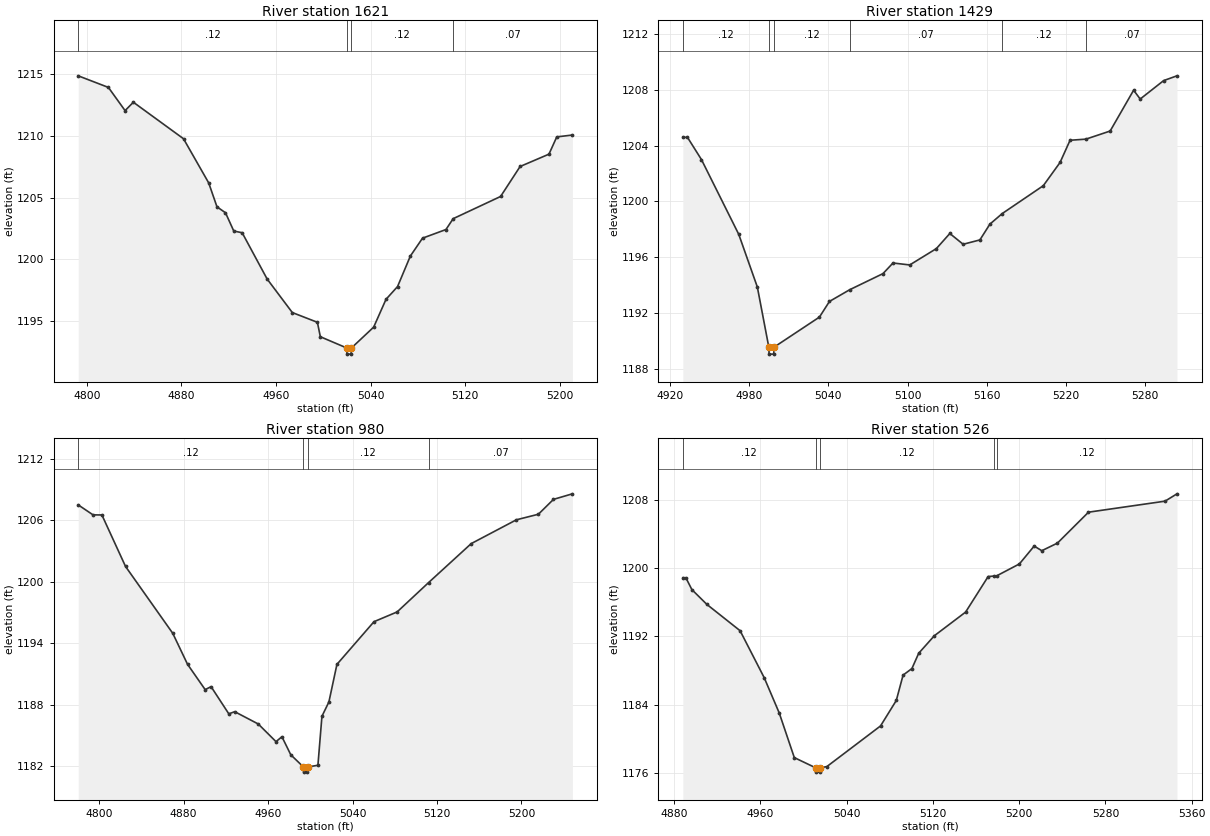
Type RM Length L Ch R = 1,1621,192,192,192
BEGIN DESCRIPTION:
Stream0236_DS 4.0
END DESCRIPTION:
XS GIS Cut Line= 3
      2141474.58     13885331.32      2141326.33     13885186.58
      2141122.19     13885134.79
#Sta/Elev= 30
  4792.8 1214.88  4818.3 1213.94  4832.4 1212.06  4839.4 1212.74  4881.8 1209.78
  4903.1 1206.20  4910.1 1204.26  4917.3 1203.78  4924.3 1202.30  4931.4 1202.16
  4952.5 1198.41  4973.8 1195.69  4995.0 1194.90  4997.5 1193.73  5019.8 1192.82
  5020.0 1192.32  5023.5 1192.32  5023.8 1192.82  5042.6 1194.51  5053.0 1196.76
  5062.8 1197.80  5073.6 1200.27  5083.9 1201.72  5103.7 1202.42  5109.8 1203.30
  5149.9 1205.10  5166.4 1207.53  5190.8 1208.53  5197.4 1209.93  5210.6 1210.08
#Mann=4,-1,0
  4792.8    0.12       0  5019.8    0.05       0  5023.8    0.12       0
  5109.8    0.07       0
Bank Sta=5019.8,5023.8
Exp/Cntr=0.3,0.1

Type RM Length L Ch R = 1,1429,449,449,449
BEGIN DESCRIPTION:
Stream0236_DS 3.0
END DESCRIPTION:
XS GIS Cut Line= 3
      2141524.98     13885124.98      2141475.00     13885075.00
      2141175.03     13885025.00
#Sta/Elev= 30
  4929.6 1204.59  4933.1 1204.59  4943.7 1203.00  4972.0 1197.65  4986.1 1193.88
  4994.8 1189.58  4995.0 1189.08  4998.5 1189.08  4998.8 1189.58  5033.2 1191.73
  5040.8 1192.85  5056.2 1193.69  5081.4 1194.84  5089.0 1195.60  5101.7 1195.46
  5121.9 1196.63  5132.1 1197.71  5142.2 1196.94  5154.9 1197.25  5162.5 1198.38
  5171.9 1199.14  5203.0 1201.13  5215.7 1202.79  5223.3 1204.38  5235.3 1204.46
  5253.7 1205.04  5271.5 1207.96  5276.5 1207.33  5294.3 1208.65  5304.4 1208.99
#Mann=6,-1,0
  4929.6    0.12       0  4994.8    0.05       0  4998.8    0.12       0
  5056.2    0.07       0  5171.9    0.12       0  5235.3    0.07       0
Bank Sta=4994.8,4998.8
Exp/Cntr=0.3,0.1

Type RM Length L Ch R = 1,980,454,454,454
BEGIN DESCRIPTION:
Stream0236_DS 2.0
END DESCRIPTION:
XS GIS Cut Line= 3
      2141825.02     13884925.04      2141725.00     13884725.00
      2141564.58     13884540.69
#Sta/Elev= 30
  4780.2 1207.49  4794.2 1206.52  4802.6 1206.51  4825.0 1201.49  4869.7 1194.98
  4883.7 1191.96  4900.4 1189.49  4906.0 1189.78  4922.8 1187.13  4928.4 1187.34
  4950.7 1186.14  4967.5 1184.42  4973.1 1184.90  4981.5 1183.14  4993.5 1181.95
  4993.7 1181.45  4997.2 1181.45  4997.5 1181.95  5007.2 1182.12  5011.0 1186.89
  5017.6 1188.29  5025.2 1191.95  5060.3 1196.11  5082.2 1197.06  5112.0 1199.92
  5152.4 1203.72  5195.2 1206.04  5216.0 1206.58  5230.3 1208.03  5248.2 1208.57
#Mann=4,-1,0
  4780.2    0.12       0  4993.5    0.05       0  4997.5    0.12       0
  5112.0    0.07       0
Bank Sta=4993.5,4997.5
Exp/Cntr=0.3,0.1

Type RM Length L Ch R = 1,526,0,0,0
BEGIN DESCRIPTION:
Stream0236_DS 1.0
END DESCRIPTION:
XS GIS Cut Line= 3
      2142124.99     13884624.99      2142075.00     13884525.00
      2141799.78     13884314.30
#Sta/Elev= 30
  4888.0 1198.86  4890.8 1198.86  4896.4 1197.47  4910.3 1195.74  4941.1 1192.66
  4963.5 1187.15  4977.4 1183.03  4991.4 1177.80  5011.3 1176.60  5011.6 1176.10
  5015.1 1176.10  5015.3 1176.60  5021.6 1176.75  5071.4 1181.51  5086.0 1184.49
  5092.3 1187.46  5100.5 1188.23  5106.8 1190.02  5121.3 1192.07  5150.3 1194.84
  5171.2 1199.00  5176.5 1199.06  5179.2 1199.09  5200.2 1200.48  5213.9 1202.57
  5221.0 1202.03  5235.5 1202.92  5264.3 1206.54  5335.3 1207.83  5346.4 1208.69
#Mann=5,-1,0
  4888.0    0.12       0  5011.3    0.05       0  5015.3    0.12       0
  5176.5    0.07       0  5179.2    0.12       0
Bank Sta=5011.3,5015.3
Exp/Cntr=0.3,0.1

Chan Stop Cuts=-1