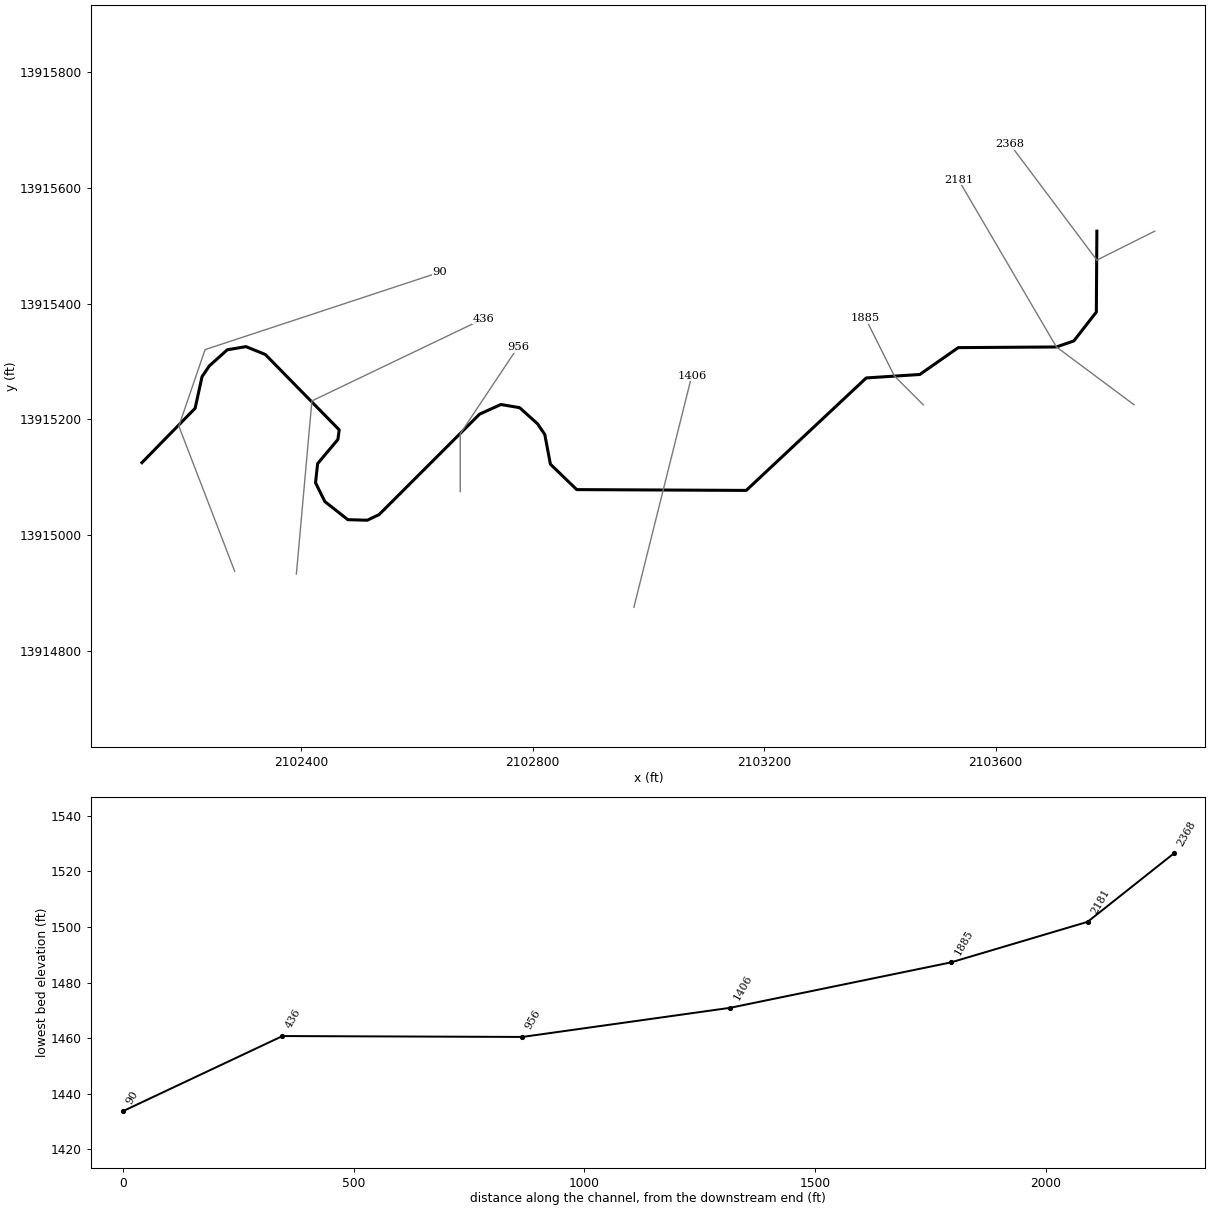
--- Stream0238_DS.prj (project) ---

Proj Title=Stream0238_DS Base Level Engineering
Current Plan=p01
Default Exp/Contr=0.3,0.1
English Units
Geom File=g01
Flow File=f01
Plan File=p01
BEGIN DESCRIPTION:
Stream0238_DS
END DESCRIPTION:

--- Stream0238_DS.p01 (plan) ---

Plan Title=Multiple Run
Short Identifier=Multiple
Geom File=g01
Flow File=f01
Subcritical Flow
K Sum by GR= 0
Std Step Tol= 0.01
Critical Tol= 0.01
Num of Std Step Trials= 20
Max Error Tol= 0.3
Flow Tol Ratio= 0.001
Split Flow NTrial= 30
Split Flow Tol= 0.02
Split Flow Ratio= 0.02
Log Output Level= 0
Friction Slope Method= 1
Unsteady Friction Slope Method= 2
Unsteady Bridges Friction Slope Method= 1
Parabolic Critical Depth
Global Vel Dist=  1 , 1 , 1
Global Log Level= 0
CheckData=True
Encroach Param= -1, 0, 0, 0
BEGIN DESCRIPTION:
Multiple Run
END DESCRIPTION:

--- Stream0238_DS.f01 (steady flow) ---

Flow Title=Multiple
Number of Profiles=7
Profile Names=10-year,25-year,50-year,1pct_min,100-year,1pct_plu,500-year
River Rch & RM= Stream0238_DS,Reach-1,2368
     279     441     586     382     762    1520    1267
River Rch & RM= Stream0238_DS,Reach-1,2181
     429     699     948     628    1253    2501    2162
Boundary for River Rch & Prof#=Stream0238_DS,Reach-1,1
Up Type=0
Dn Type=3
Dn Slope=0.005
Boundary for River Rch & Prof#=Stream0238_DS,Reach-1,2
Up Type=0
Dn Type=3
Dn Slope=0.005
Boundary for River Rch & Prof#=Stream0238_DS,Reach-1,3
Up Type=0
Dn Type=3
Dn Slope=0.005
Boundary for River Rch & Prof#=Stream0238_DS,Reach-1,4
Up Type=0
Dn Type=3
Dn Slope=0.005
Boundary for River Rch & Prof#=Stream0238_DS,Reach-1,5
Up Type=0
Dn Type=3
Dn Slope=0.005
Boundary for River Rch & Prof#=Stream0238_DS,Reach-1,6
Up Type=0
Dn Type=3
Dn Slope=0.005
Boundary for River Rch & Prof#=Stream0238_DS,Reach-1,7
Up Type=0
Dn Type=3
Dn Slope=0.005

--- Stream0238_DS.g01 (geometry) ---

Geom Title=Existing Conditions

River Reach=Stream0238_DS,Reach-1
Reach XY= 30
      2103775.00     13915525.00      2103774.09     13915385.23
      2103735.18     13915335.32      2103705.13     13915324.91
      2103535.50     13915323.78      2103469.02     13915277.36
      2103376.50     13915271.39      2103169.15     13915077.06
      2102876.25     13915078.45      2102830.75     13915122.45
      2102821.10     13915173.60      2102808.50     13915192.21
      2102777.54     13915220.04      2102745.23     13915225.50
      2102708.34     13915208.80      2102534.66     13915035.17
      2102514.30     13915025.53      2102480.82     13915026.50
      2102441.07     13915057.77      2102424.96     13915090.20
      2102428.57     13915123.32      2102463.61     13915165.13
      2102465.85     13915181.73      2102338.20     13915311.90
      2102304.77     13915325.50      2102272.46     13915320.04
      2102241.49     13915292.23      2102228.87     13915273.64
      2102216.88     13915218.95      2102125.00     13915125.00

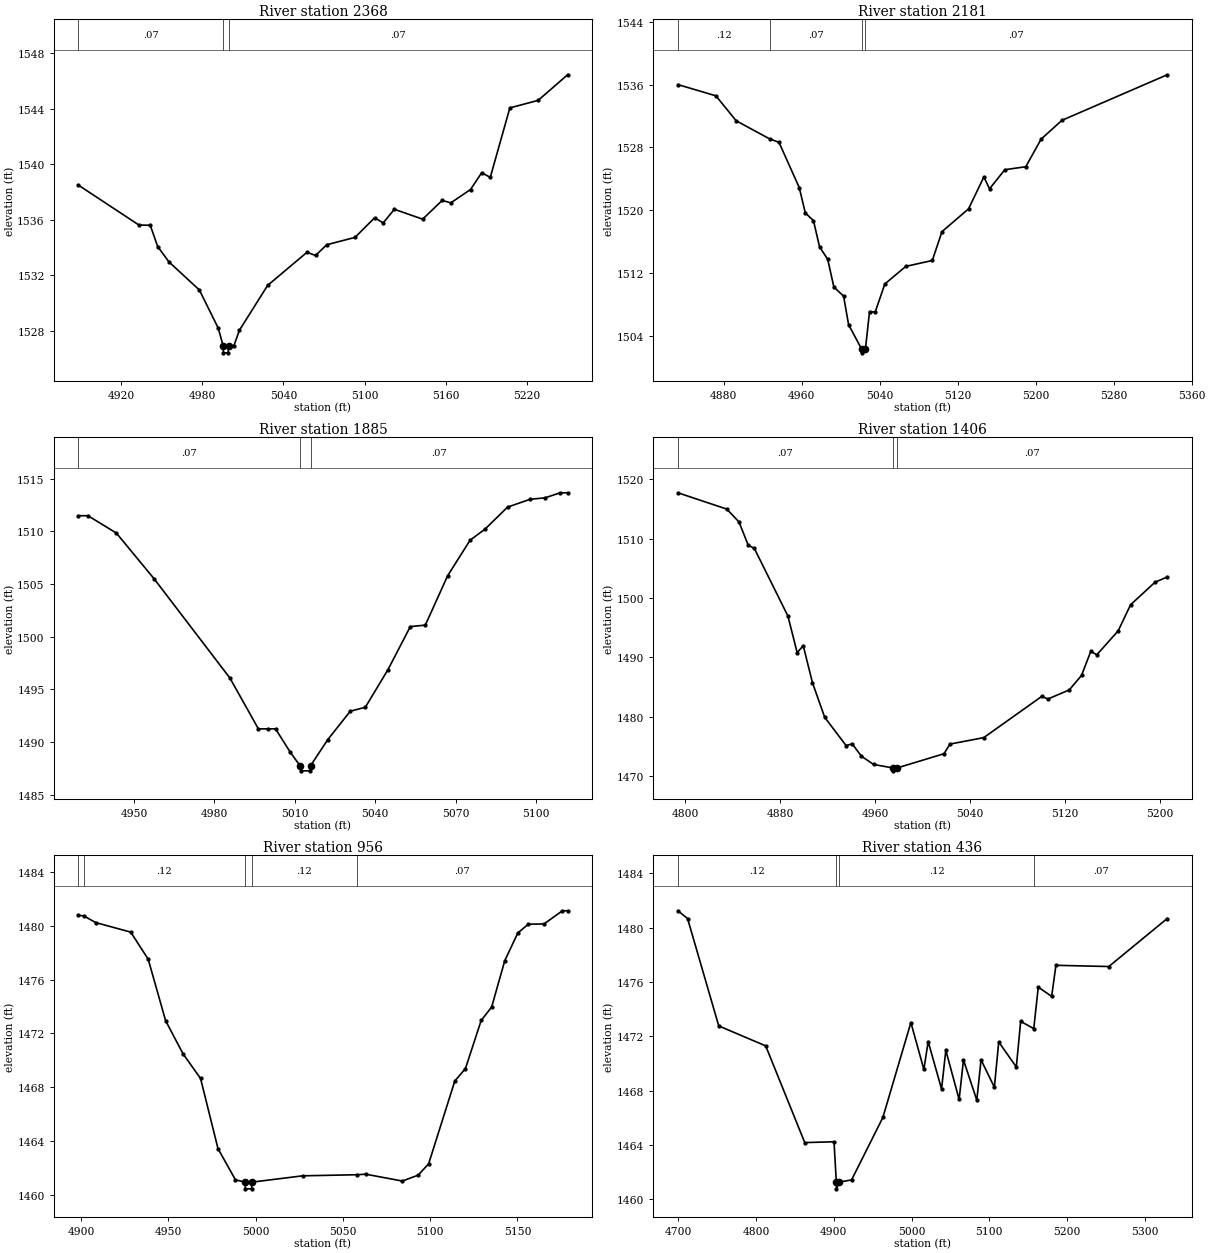
Type RM Length L Ch R = 1,2368,187,187,187
BEGIN DESCRIPTION:
Stream0238_DS 4.0
END DESCRIPTION:
XS GIS Cut Line= 3
      2103875.04     13915525.02      2103775.00     13915475.00
      2103625.03     13915674.96
#Sta/Elev= 30
  4888.3 1538.50  4933.1 1535.63  4941.5 1535.61  4947.0 1534.08  4955.4 1532.97
  4977.8 1530.96  4991.8 1528.21  4995.4 1526.94  4995.6 1526.44  4999.1 1526.44
  4999.4 1526.94  5003.3 1526.94  5007.4 1528.06  5028.3 1531.29  5057.4 1533.67
  5063.7 1533.44  5072.0 1534.21  5092.9 1534.74  5107.4 1536.15  5113.7 1535.78
  5122.0 1536.76  5142.9 1536.05  5157.4 1537.40  5163.7 1537.22  5178.3 1538.18
  5186.6 1539.39  5192.9 1539.05  5207.4 1544.05  5228.3 1544.59  5250.1 1546.43
#Mann=3,-1,0
  4888.3    0.07       0  4995.4    0.05       0  4999.4    0.07       0
Bank Sta=4995.4,4999.4
Exp/Cntr=0.3,0.1

Type RM Length L Ch R = 1,2181,296,296,296
BEGIN DESCRIPTION:
Stream0238_DS 3.5
END DESCRIPTION:
XS GIS Cut Line= 3
      2103839.17     13915225.13      2103705.13     13915324.91
      2103535.84     13915613.87
#Sta/Elev= 30
  4832.9 1535.99  4871.9 1534.56  4892.7 1531.38  4927.1 1529.07  4936.6 1528.64
  4957.4 1522.87  4963.6 1519.65  4972.0 1518.66  4978.2 1515.33  4986.6 1513.74
  4992.9 1510.21  5002.9 1509.05  5008.0 1505.42  5021.3 1502.33  5021.5 1501.83
  5025.3 1502.33  5029.5 1507.08  5035.3 1507.02  5045.2 1510.60  5066.7 1512.84
  5093.9 1513.59  5103.8 1517.26  5131.1 1520.17  5146.8 1524.23  5152.6 1522.72
  5168.3 1525.15  5189.8 1525.53  5205.5 1529.04  5226.9 1531.44  5334.9 1537.24
#Mann=4,-1,0
  4832.9    0.12       0  4927.1    0.07       0  5021.3    0.05       0
  5025.3    0.07       0
Bank Sta=5021.3,5025.3
Exp/Cntr=0.3,0.1

Type RM Length L Ch R = 1,1885,479,479,479
BEGIN DESCRIPTION:
Stream0238_DS 3.0
END DESCRIPTION:
XS GIS Cut Line= 3
      2103475.03     13915224.97      2103425.00     13915275.00
      2103374.98     13915375.04
#Sta/Elev= 27
  4929.2 1511.50  4932.8 1511.50  4943.4 1509.85  4957.5 1505.50  4985.8 1496.06
  4996.4 1491.24  5000.0 1491.24  5002.8 1491.24  5008.3 1489.02  5011.9 1487.75
  5012.2 1487.25  5015.7 1487.25  5015.9 1487.75  5022.3 1490.22  5030.7 1492.92
  5036.3 1493.29  5044.7 1496.84  5053.1 1500.96  5058.7 1501.10  5067.0 1505.78
  5075.4 1509.17  5081.0 1510.23  5089.4 1512.32  5097.8 1513.06  5103.4 1513.20
  5109.0 1513.68  5111.8 1513.68
#Mann=3,-1,0
  4929.2    0.07       0  5011.9    0.05       0  5015.9    0.07       0
Bank Sta=5011.9,5015.9
Exp/Cntr=0.3,0.1

Type RM Length L Ch R = 1,1406,450,450,450
BEGIN DESCRIPTION:
Stream0238_DS 2.0
END DESCRIPTION:
XS GIS Cut Line= 3
      2102975.01     13914875.03      2103025.00     13915075.00
      2103075.00     13915275.02
#Sta/Elev= 30
  4793.9 1517.73  4835.1 1514.98  4845.4 1512.81  4853.1 1508.92  4858.3 1508.36
  4886.6 1496.97  4894.4 1490.80  4899.5 1491.98  4907.3 1485.73  4917.6 1479.91
  4935.6 1475.16  4940.8 1475.44  4948.5 1473.37  4958.8 1471.97  4974.8 1471.40
  4975.1 1470.90  4978.8 1471.40  5018.1 1473.78  5023.2 1475.41  5051.6 1476.49
  5100.5 1483.44  5105.7 1483.00  5123.7 1484.53  5134.0 1486.97  5141.8 1491.02
  5146.9 1490.45  5164.9 1494.48  5175.3 1498.86  5195.9 1502.66  5206.2 1503.55
#Mann=3,-1,0
  4793.9    0.07       0  4974.8    0.05       0  4978.8    0.07       0
Bank Sta=4974.8,4978.8
Exp/Cntr=0.3,0.1

Type RM Length L Ch R = 1,956,520,520,520
BEGIN DESCRIPTION:
Stream0238_DS 1.0
END DESCRIPTION:
XS GIS Cut Line= 3
      2102675.00     13915075.04      2102675.00     13915175.00
      2102774.98     13915324.97
#Sta/Elev= 30
  4898.5 1480.80  4901.6 1480.76  4908.5 1480.26  4928.5 1479.55  4938.5 1477.54
  4948.5 1472.95  4958.5 1470.48  4968.5 1468.65  4978.5 1463.42  4988.5 1461.10
  4994.0 1460.93  4994.2 1460.43  4997.7 1460.43  4998.0 1460.93  5027.0 1461.40
  5057.9 1461.48  5063.1 1461.52  5084.1 1461.01  5093.1 1461.45  5099.1 1462.29
  5114.1 1468.46  5120.2 1469.39  5129.2 1472.97  5135.2 1473.97  5142.7 1477.42
  5150.2 1479.49  5156.2 1480.14  5165.2 1480.16  5175.7 1481.14  5178.7 1481.14
#Mann=5,-1,0
  4898.5    0.07       0  4901.6    0.12       0  4994.0    0.05       0
  4998.0    0.12       0  5057.9    0.07       0
Bank Sta=4994,4998
Exp/Cntr=0.3,0.1

Type RM Length L Ch R = 1,436,346,346,346
BEGIN DESCRIPTION:
Stream0238_DS 0.5
END DESCRIPTION:
XS GIS Cut Line= 3
      2102391.86     13914932.69      2102418.68     13915231.69
      2102715.03     13915373.67
#Sta/Elev= 30
  4699.8 1481.25  4712.2 1480.68  4752.3 1472.76  4812.6 1471.29  4862.8 1464.16
  4900.4 1464.22  4903.4 1461.25  4903.6 1460.75  4907.4 1461.25  4923.0 1461.41
  4963.2 1466.01  4999.2 1473.01  5015.9 1469.55  5021.4 1471.61  5038.6 1468.11
  5044.1 1470.96  5061.2 1467.34  5066.8 1470.25  5083.9 1467.29  5089.4 1470.26
  5106.5 1468.24  5112.1 1471.58  5134.7 1469.73  5140.3 1473.10  5157.1 1472.56
  5162.9 1475.62  5180.1 1474.94  5185.6 1477.23  5253.6 1477.14  5328.6 1480.68
#Mann=4,-1,0
  4699.8    0.12       0  4903.4    0.05       0  4907.4    0.12       0
  5157.1    0.07       0
Bank Sta=4903.4,4907.4
Exp/Cntr=0.3,0.1

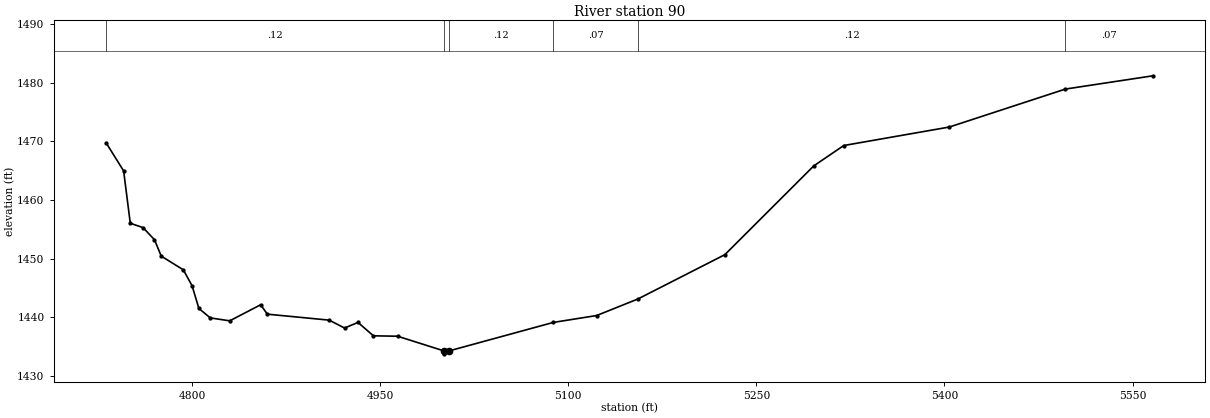
Type RM Length L Ch R = 1,90,0,0,0
BEGIN DESCRIPTION:
Stream0238_DS 0.0
END DESCRIPTION:
XS GIS Cut Line= 4
      2102285.22     13914937.46      2102188.78     13915188.15
      2102234.08     13915320.33      2102639.29     13915453.97
#Sta/Elev= 30
  4731.4 1469.78  4745.4 1464.97  4750.7 1456.03  4760.9 1455.28  4770.0 1453.21
  4775.4 1450.41  4793.0 1448.07  4800.0 1445.34  4805.4 1441.47  4814.5 1439.85
  4830.0 1439.35  4854.7 1442.10  4860.0 1440.49  4909.3 1439.47  4921.6 1438.12
  4932.3 1439.08  4944.6 1436.79  4963.9 1436.72  5000.9 1434.21  5001.1 1433.71
  5004.9 1434.21  5088.1 1439.08  5122.7 1440.26  5155.6 1443.09  5224.9 1450.66
  5295.8 1465.83  5319.7 1469.31  5403.9 1472.47  5496.5 1478.96  5566.4 1481.23
#Mann=6,-1,0
  4731.4    0.12       0  5000.9    0.05       0  5004.9    0.12       0
  5088.1    0.07       0  5155.6    0.12       0  5496.5    0.07       0
Bank Sta=5000.9,5004.9
Exp/Cntr=0.3,0.1

Chan Stop Cuts=-1