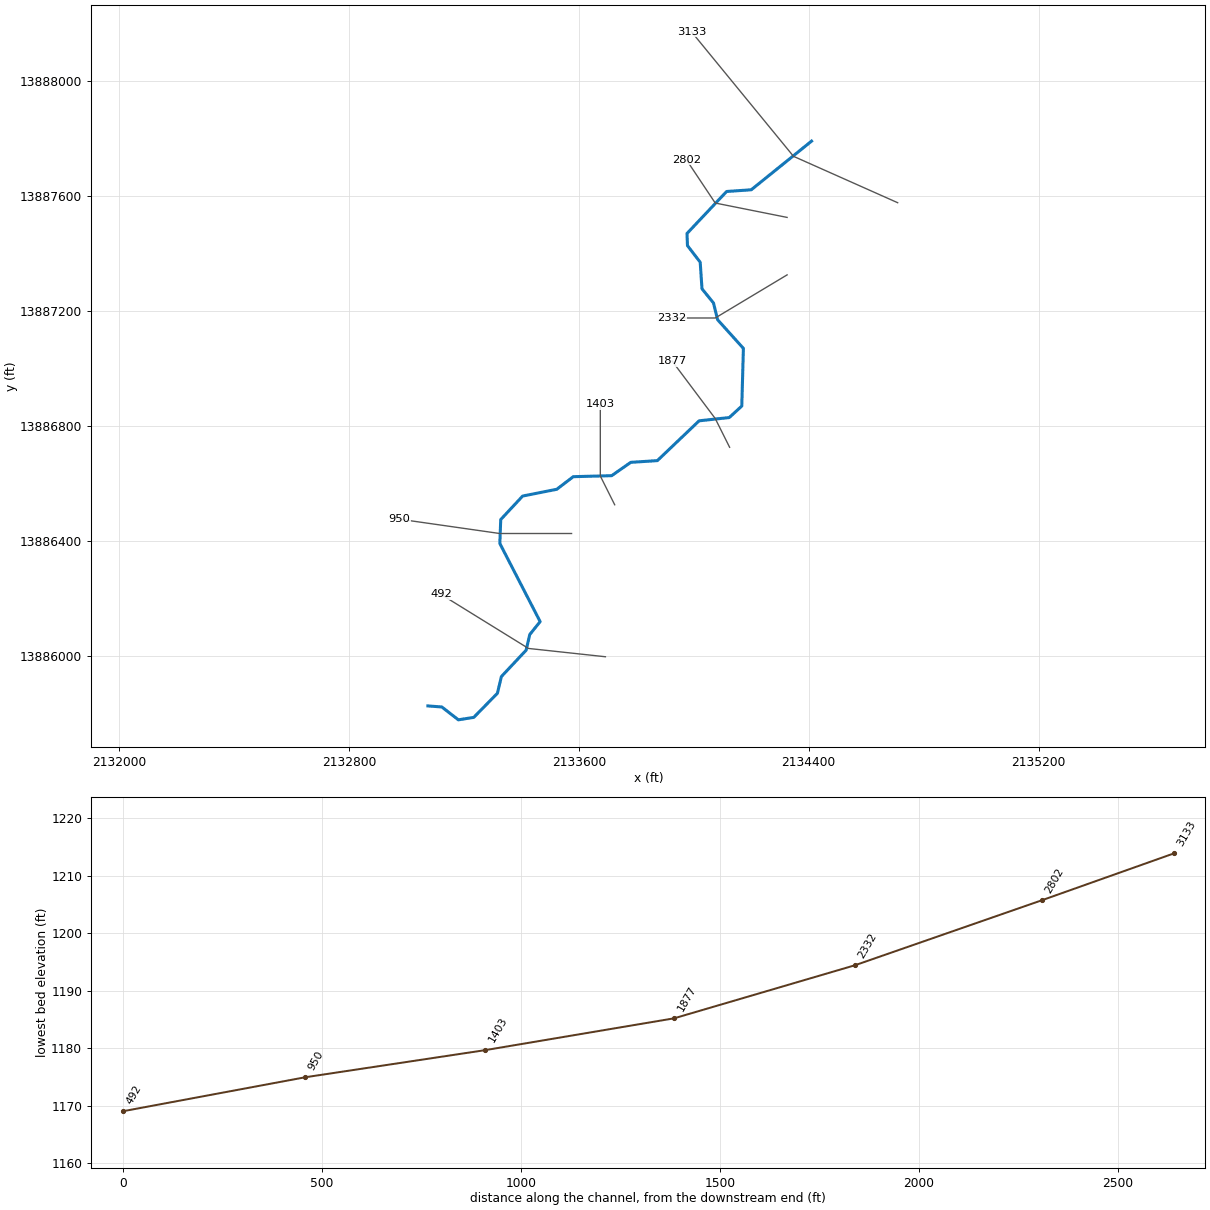
--- Stream0241_DS.prj (project) ---

Proj Title=Stream0241_DS Base Level Engineering
Current Plan=p01
Default Exp/Contr=0.3,0.1
English Units
Geom File=g01
Flow File=f01
Plan File=p01
BEGIN DESCRIPTION:
Stream0241_DS
END DESCRIPTION:

--- Stream0241_DS.p01 (plan) ---

Plan Title=Multiple Run
Short Identifier=Multiple
Geom File=g01
Flow File=f01
Subcritical Flow
K Sum by GR= 0
Std Step Tol= 0.01
Critical Tol= 0.01
Num of Std Step Trials= 20
Max Error Tol= 0.3
Flow Tol Ratio= 0.001
Split Flow NTrial= 30
Split Flow Tol= 0.02
Split Flow Ratio= 0.02
Log Output Level= 0
Friction Slope Method= 1
Unsteady Friction Slope Method= 2
Unsteady Bridges Friction Slope Method= 1
Parabolic Critical Depth
Global Vel Dist=  1 , 1 , 1
Global Log Level= 0
CheckData=True
Encroach Param= -1, 0, 0, 0
BEGIN DESCRIPTION:
Multiple Run
END DESCRIPTION:

--- Stream0241_DS.f01 (steady flow) ---

Flow Title=Multiple
Number of Profiles=7
Profile Names=10-year,25-year,50-year,1pct_min,100-year,1pct_plu,500-year
River Rch & RM= Stream0241_DS,Reach-1,3133
     626    1027    1397     924    1843    3677    3165
River Rch & RM= Stream0241_DS,Reach-1,2802
     901    1510    2084    1395    2784    5554    4910
Boundary for River Rch & Prof#=Stream0241_DS,Reach-1,1
Up Type=0
Dn Type=3
Dn Slope=0.005
Boundary for River Rch & Prof#=Stream0241_DS,Reach-1,2
Up Type=0
Dn Type=3
Dn Slope=0.005
Boundary for River Rch & Prof#=Stream0241_DS,Reach-1,3
Up Type=0
Dn Type=3
Dn Slope=0.005
Boundary for River Rch & Prof#=Stream0241_DS,Reach-1,4
Up Type=0
Dn Type=3
Dn Slope=0.005
Boundary for River Rch & Prof#=Stream0241_DS,Reach-1,5
Up Type=0
Dn Type=3
Dn Slope=0.005
Boundary for River Rch & Prof#=Stream0241_DS,Reach-1,6
Up Type=0
Dn Type=3
Dn Slope=0.005
Boundary for River Rch & Prof#=Stream0241_DS,Reach-1,7
Up Type=0
Dn Type=3
Dn Slope=0.005

--- Stream0241_DS.g01 (geometry) ---

Geom Title=Existing Conditions

River Reach=Stream0241_DS,Reach-1
Reach XY= 30
      2134410.21     13887790.55      2134200.25     13887621.11
      2134114.52     13887615.20      2133976.62     13887468.97
      2133978.34     13887426.75      2134022.62     13887369.03
      2134028.82     13887276.58      2134068.86     13887227.17
      2134083.16     13887168.95      2134172.94     13887069.14
      2134167.33     13886868.48      2134123.75     13886828.51
      2134018.83     13886817.14      2133873.50     13886678.61
      2133780.98     13886672.64      2133714.49     13886626.23
      2133580.94     13886622.73      2133523.40     13886578.86
      2133404.80     13886555.39      2133328.45     13886473.52
      2133325.36     13886390.27      2133465.61     13886118.39
      2133429.45     13886073.35      2133416.86     13886018.96
      2133330.87     13885927.28      2133316.85     13885868.93
      2133234.71     13885785.17      2133181.10     13885776.60
      2133123.51     13885821.31      2133075.00     13885825.00

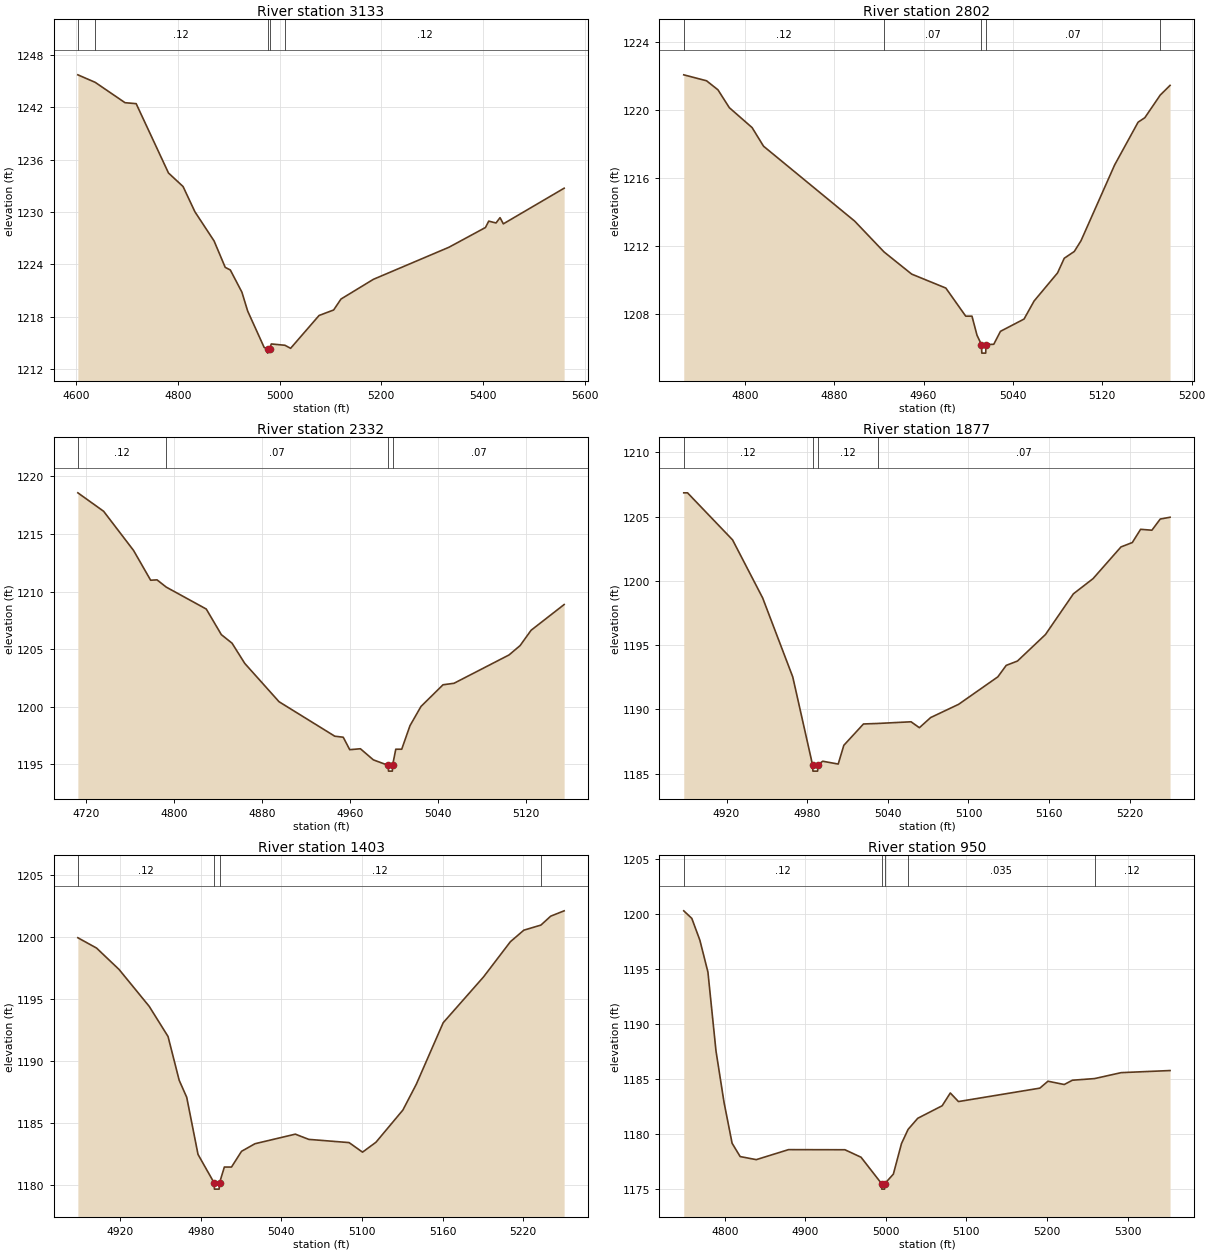
Type RM Length L Ch R = 1,3133,331,331,331
BEGIN DESCRIPTION:
Stream0241_DS 7.0
END DESCRIPTION:
XS GIS Cut Line= 3
      2134709.79     13887576.12      2134347.23     13887737.61
      2133992.59     13888170.61
#Sta/Elev= 30
  4603.1 1245.70  4637.2 1244.84  4695.9 1242.51  4717.8 1242.40  4781.4 1234.46
  4810.1 1232.91  4833.3 1230.03  4871.1 1226.68  4893.0 1223.66  4903.0 1223.36
  4925.8 1220.82  4937.2 1218.65  4969.6 1214.49  4976.2 1214.34  4976.4 1213.84
  4980.2 1214.34  4983.7 1214.89  5010.4 1214.74  5021.6 1214.39  5077.6 1218.15
  5106.3 1218.78  5120.7 1220.03  5184.5 1222.29  5333.1 1225.96  5404.9 1228.22
  5411.3 1228.95  5425.7 1228.74  5433.6 1229.35  5440.1 1228.64  5559.7 1232.72
#Mann=5,-1,0
  4603.1    0.07       0  4637.2    0.12       0  4976.2    0.05       0
  4980.2    0.12       0  5010.4    0.12       0
Bank Sta=4976.2,4980.2
Exp/Cntr=0.3,0.1

Type RM Length L Ch R = 1,2802,470,470,470
BEGIN DESCRIPTION:
Stream0241_DS 6.0
END DESCRIPTION:
XS GIS Cut Line= 3
      2134325.04     13887524.99      2134075.00     13887575.00
      2133974.98     13887725.03
#Sta/Elev= 30
  4745.3 1222.06  4765.7 1221.71  4775.9 1221.18  4786.1 1220.13  4806.5 1218.96
  4816.7 1217.87  4898.3 1213.47  4924.6 1211.66  4949.3 1210.36  4979.9 1209.54
  4997.7 1207.89  5003.3 1207.89  5007.8 1206.77  5011.8 1206.22  5012.1 1205.72
  5015.6 1205.72  5015.8 1206.22  5022.8 1206.24  5028.8 1207.00  5049.9 1207.72
  5058.9 1208.78  5079.9 1210.43  5085.9 1211.29  5094.9 1211.69  5100.9 1212.32
  5131.0 1216.77  5152.0 1219.28  5158.0 1219.54  5171.8 1220.87  5180.6 1221.44
#Mann=5,-1,0
  4745.3    0.12       0  4924.6    0.07       0  5011.8    0.05       0
  5015.8    0.07       0  5171.8    0.12       0
Bank Sta=5011.8,5015.8
Exp/Cntr=0.3,0.1

Type RM Length L Ch R = 1,2332,455,455,455
BEGIN DESCRIPTION:
Stream0241_DS 5.0
END DESCRIPTION:
XS GIS Cut Line= 3
      2134325.03     13887325.02      2134075.00     13887175.00
      2133924.98     13887175.00
#Sta/Elev= 30
  4712.8 1218.56  4736.2 1216.96  4763.4 1213.56  4778.9 1210.98  4784.7 1211.01
  4793.1 1210.38  4829.4 1208.48  4843.1 1206.26  4852.8 1205.52  4864.4 1203.76
  4895.5 1200.44  4946.1 1197.45  4953.8 1197.36  4959.7 1196.28  4969.4 1196.36
  4981.1 1195.40  4994.6 1194.92  4994.9 1194.42  4998.4 1194.42  4998.6 1194.92
  5001.5 1196.32  5006.9 1196.32  5014.4 1198.36  5024.4 1200.03  5044.4 1201.91
  5054.4 1202.04  5104.4 1204.50  5114.4 1205.31  5124.4 1206.64  5154.4 1208.87
#Mann=4,-1,0
  4712.8    0.12       0  4793.1    0.07       0  4994.6    0.05       0
  4998.6    0.07       0
Bank Sta=4994.6,4998.6
Exp/Cntr=0.3,0.1

Type RM Length L Ch R = 1,1877,474,474,474
BEGIN DESCRIPTION:
Stream0241_DS 4.0
END DESCRIPTION:
XS GIS Cut Line= 3
      2134125.00     13886725.00      2134075.00     13886825.00
      2133925.00     13887025.00
#Sta/Elev= 30
  4888.2 1206.85  4891.0 1206.85  4924.5 1203.19  4946.9 1198.67  4969.3 1192.52
  4984.0 1185.69  4984.3 1185.19  4987.8 1185.19  4988.0 1185.69  4991.6 1185.96
  5003.1 1185.74  5007.3 1187.20  5021.9 1188.86  5032.6 1188.90  5057.3 1189.03
  5063.5 1188.57  5071.9 1189.36  5092.7 1190.39  5121.9 1192.53  5128.1 1193.42
  5136.5 1193.76  5157.3 1195.82  5178.1 1198.99  5192.7 1200.17  5213.5 1202.64
  5221.9 1202.98  5228.1 1204.01  5236.5 1203.94  5242.7 1204.81  5250.0 1204.95
#Mann=4,-1,0
  4888.2    0.12       0  4984.0    0.05       0  4988.0    0.12       0
  5032.6    0.07       0
Bank Sta=4984,4988
Exp/Cntr=0.3,0.1

Type RM Length L Ch R = 1,1403,453,453,453
BEGIN DESCRIPTION:
Stream0241_DS 3.0
END DESCRIPTION:
XS GIS Cut Line= 3
      2133724.99     13886525.03      2133675.00     13886625.00
      2133675.00     13886875.03
#Sta/Elev= 30
  4888.6 1199.93  4902.5 1199.10  4919.3 1197.37  4941.7 1194.40  4955.7 1191.97
  4964.0 1188.44  4969.6 1187.07  4978.0 1182.47  4990.0 1180.17  4990.2 1179.67
  4993.7 1179.67  4994.0 1180.17  4997.6 1181.45  5002.9 1181.45  5010.4 1182.72
  5020.4 1183.33  5050.4 1184.10  5060.4 1183.68  5090.4 1183.42  5100.4 1182.65
  5110.4 1183.45  5130.4 1186.04  5140.4 1188.12  5160.4 1193.08  5190.4 1196.77
  5210.4 1199.61  5220.4 1200.54  5233.1 1200.95  5240.4 1201.67  5250.4 1202.10
#Mann=4,-1,0
  4888.6    0.12       0  4990.0    0.05       0  4994.0    0.12       0
  5233.1    0.07       0
Bank Sta=4990,4994
Exp/Cntr=0.3,0.1

Type RM Length L Ch R = 1,950,458,458,458
BEGIN DESCRIPTION:
Stream0241_DS 2.0
END DESCRIPTION:
XS GIS Cut Line= 3
      2133574.96     13886425.00      2133325.00     13886425.00
      2132975.01     13886475.00
#Sta/Elev= 30
  4749.2 1200.25  4759.2 1199.56  4769.2 1197.58  4779.2 1194.68  4789.2 1187.51
  4799.2 1182.83  4809.2 1179.12  4819.2 1177.91  4839.2 1177.63  4879.2 1178.54
  4949.2 1178.53  4969.2 1177.85  4994.7 1175.45  4994.9 1174.95  4998.4 1174.95
  4998.7 1175.45  5009.3 1176.31  5019.4 1179.09  5027.6 1180.38  5039.6 1181.39
  5069.9 1182.53  5080.0 1183.69  5090.1 1182.91  5191.1 1184.13  5201.2 1184.76
  5221.4 1184.46  5231.5 1184.85  5259.1 1185.00  5292.1 1185.54  5352.7 1185.73
#Mann=5,-1,0
  4749.2    0.12       0  4994.7    0.05       0  4998.7    0.12       0
  5027.6   0.035       0  5259.1    0.12       0
Bank Sta=4994.7,4998.7
Exp/Cntr=0.3,0.1

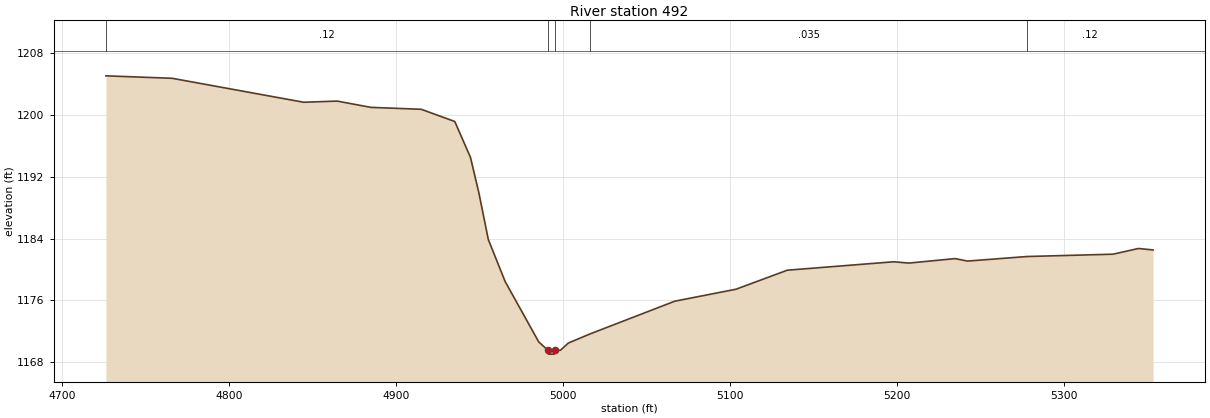
Type RM Length L Ch R = 1,492,0,0,0
BEGIN DESCRIPTION:
Stream0241_DS 1.0
END DESCRIPTION:
XS GIS Cut Line= 3
      2133692.78     13885996.10      2133425.00     13886025.00
      2133120.53     13886213.24
#Sta/Elev= 30
  4726.3 1205.06  4766.0 1204.74  4844.8 1201.64  4864.9 1201.79  4885.0 1200.98
  4915.2 1200.73  4935.3 1199.15  4944.7 1194.51  4949.7 1189.95  4955.4 1183.87
  4965.5 1178.43  4985.6 1170.63  4991.1 1169.55  4991.4 1169.05  4994.9 1169.05
  4995.1 1169.55  4998.6 1169.55  5003.3 1170.48  5016.4 1171.67  5067.1 1175.90
  5103.8 1177.45  5134.5 1179.91  5198.3 1181.00  5207.3 1180.83  5235.0 1181.41
  5242.5 1181.09  5278.1 1181.68  5329.6 1181.98  5344.9 1182.72  5353.6 1182.53
#Mann=5,-1,0
  4726.3    0.12       0  4991.1    0.05       0  4995.1    0.12       0
  5016.4   0.035       0  5278.1    0.12       0
Bank Sta=4991.1,4995.1
Exp/Cntr=0.3,0.1

Chan Stop Cuts=-1