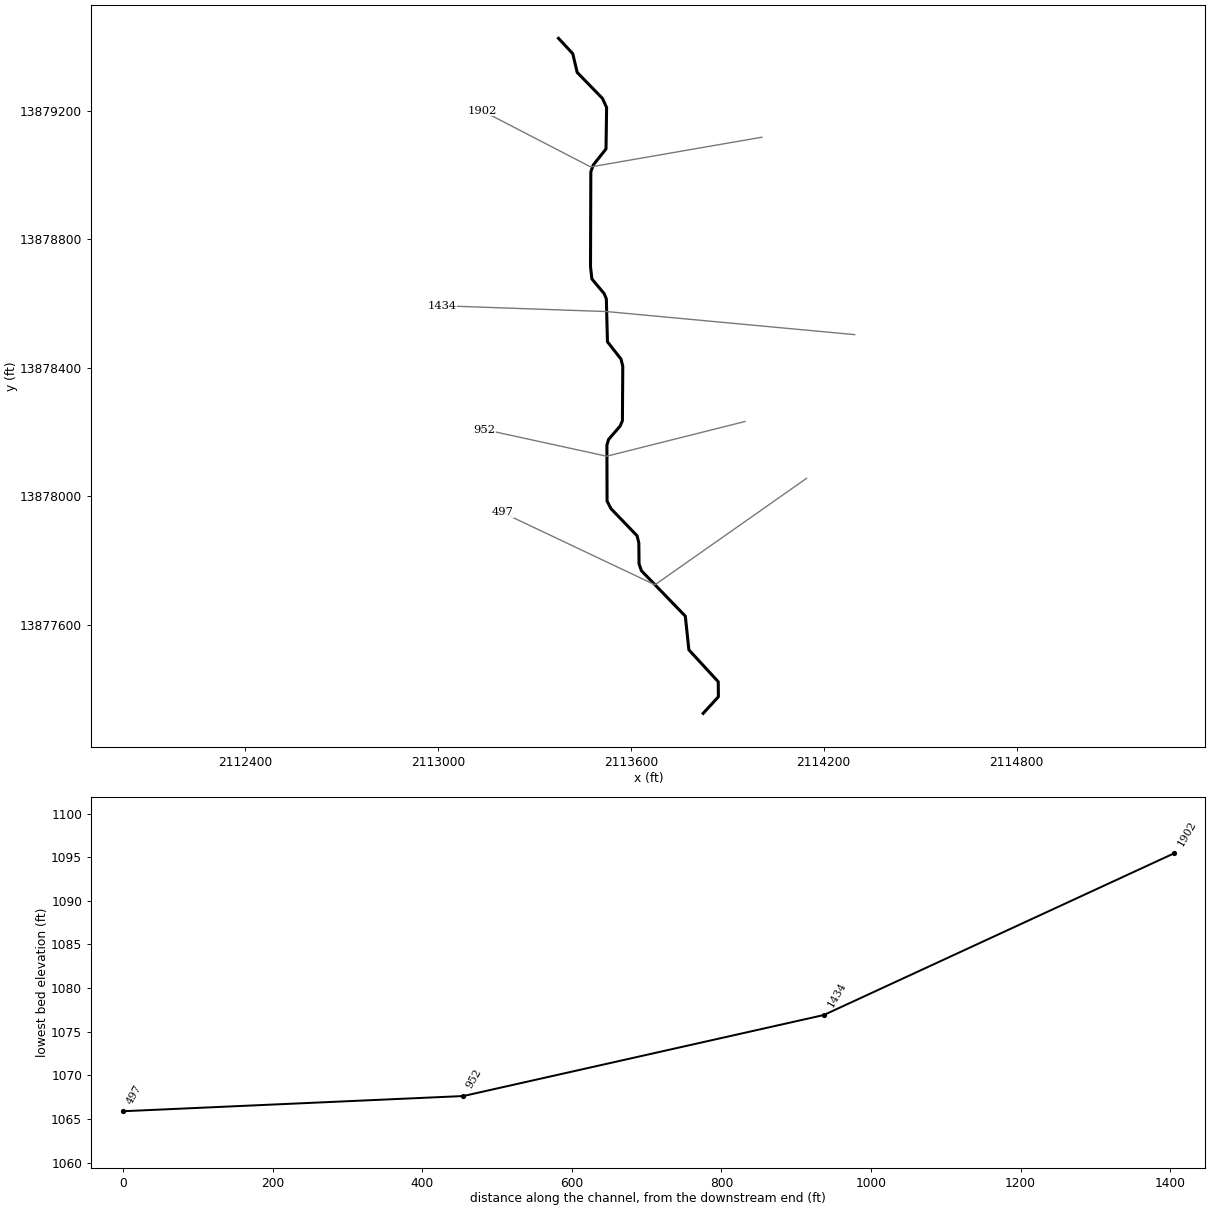
--- Stream0245_DS.prj (project) ---

Proj Title=Stream0245_DS Base Level Engineering
Current Plan=p01
Default Exp/Contr=0.3,0.1
English Units
Geom File=g01
Flow File=f01
Plan File=p01
BEGIN DESCRIPTION:
Stream0245_DS
END DESCRIPTION:

--- Stream0245_DS.p01 (plan) ---

Plan Title=Multiple Run
Short Identifier=Multiple
Geom File=g01
Flow File=f01
Subcritical Flow
K Sum by GR= 0
Std Step Tol= 0.01
Critical Tol= 0.01
Num of Std Step Trials= 20
Max Error Tol= 0.3
Flow Tol Ratio= 0.001
Split Flow NTrial= 30
Split Flow Tol= 0.02
Split Flow Ratio= 0.02
Log Output Level= 0
Friction Slope Method= 1
Unsteady Friction Slope Method= 2
Unsteady Bridges Friction Slope Method= 1
Parabolic Critical Depth
Global Vel Dist=  1 , 1 , 1
Global Log Level= 0
CheckData=True
Encroach Param= -1, 0, 0, 0
BEGIN DESCRIPTION:
Multiple Run
END DESCRIPTION:

--- Stream0245_DS.f01 (steady flow) ---

Flow Title=Multiple
Number of Profiles=7
Profile Names=10-year,25-year,50-year,1pct_min,100-year,1pct_plu,500-year
River Rch & RM= Stream0245_DS,Reach-1,1902
    1114    1894    2641    1786    3563    7109    6412
Boundary for River Rch & Prof#=Stream0245_DS,Reach-1,1
Up Type=0
Dn Type=3
Dn Slope=0.005
Boundary for River Rch & Prof#=Stream0245_DS,Reach-1,2
Up Type=0
Dn Type=3
Dn Slope=0.005
Boundary for River Rch & Prof#=Stream0245_DS,Reach-1,3
Up Type=0
Dn Type=3
Dn Slope=0.005
Boundary for River Rch & Prof#=Stream0245_DS,Reach-1,4
Up Type=0
Dn Type=3
Dn Slope=0.005
Boundary for River Rch & Prof#=Stream0245_DS,Reach-1,5
Up Type=0
Dn Type=3
Dn Slope=0.005
Boundary for River Rch & Prof#=Stream0245_DS,Reach-1,6
Up Type=0
Dn Type=3
Dn Slope=0.005
Boundary for River Rch & Prof#=Stream0245_DS,Reach-1,7
Up Type=0
Dn Type=3
Dn Slope=0.005

--- Stream0245_DS.g01 (geometry) ---

Geom Title=Existing Conditions

River Reach=Stream0245_DS,Reach-1
Reach XY= 30
      2113375.00     13879425.00      2113419.30     13879377.35
      2113433.07     13879318.92      2113511.61     13879238.31
      2113524.63     13879209.83      2113522.75     13879080.94
      2113483.14     13879031.06      2113475.52     13879009.78
      2113474.55     13878714.81      2113478.78     13878676.57
      2113516.85     13878631.05      2113523.77     13878614.49
      2113527.27     13878480.94      2113569.25     13878427.33
      2113574.93     13878404.97      2113573.78     13878235.51
      2113566.86     13878218.94      2113530.75     13878177.33
      2113525.52     13878159.78      2113526.05     13877985.44
      2113538.40     13877961.69      2113619.46     13877877.42
      2113624.86     13877854.94      2113625.53     13877790.22
      2113632.86     13877768.83      2113769.48     13877627.43
      2113780.54     13877522.58      2113871.91     13877423.42
      2113872.33     13877376.62      2113825.00     13877325.00

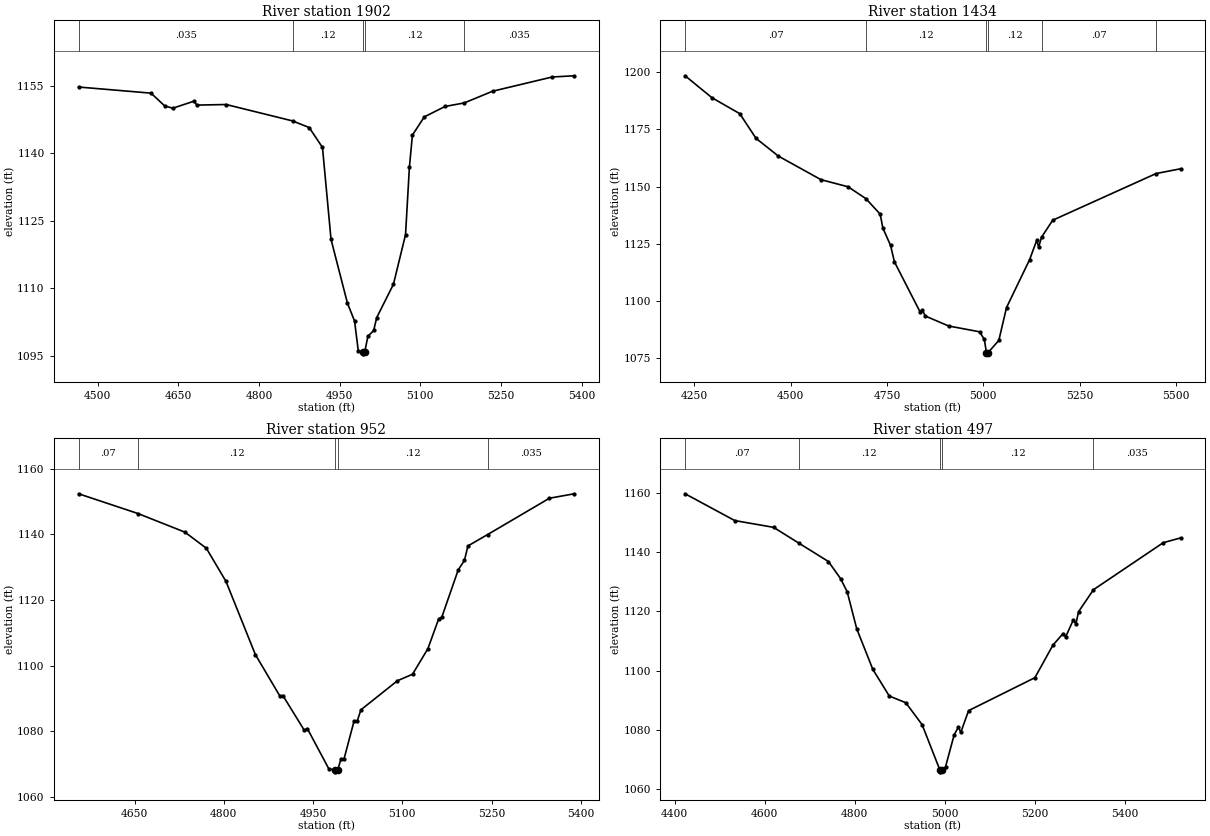
Type RM Length L Ch R = 1,1902,468,468,468
BEGIN DESCRIPTION:
Stream0245_DS 4.0
END DESCRIPTION:
XS GIS Cut Line= 3
      2114007.63     13879117.40      2113475.00     13879025.00
      2113136.42     13879200.18
#Sta/Elev= 30
  4464.5 1154.76  4599.1 1153.40  4624.6 1150.56  4639.7 1150.05  4679.3 1151.62
  4684.3 1150.74  4739.0 1150.87  4862.5 1147.22  4893.4 1145.75  4918.1 1141.33
  4934.0 1120.88  4964.5 1106.71  4977.8 1102.72  4984.8 1095.98  4992.9 1095.93
  4993.2 1095.43  4996.9 1095.93  5002.5 1099.31  5013.3 1100.62  5019.0 1103.49
  5050.1 1110.90  5072.6 1121.93  5079.8 1136.94  5085.4 1144.07  5107.5 1148.12
  5146.2 1150.44  5181.7 1151.22  5234.7 1153.83  5345.4 1156.99  5386.3 1157.26
#Mann=5,-1,0
  4464.5   0.035       0  4862.5    0.12       0  4992.9    0.05       0
  4996.9    0.12       0  5181.7   0.035       0
Bank Sta=4992.9,4996.9
Exp/Cntr=0.3,0.1

Type RM Length L Ch R = 1,1434,482,482,482
BEGIN DESCRIPTION:
Stream0245_DS 3.0
END DESCRIPTION:
XS GIS Cut Line= 3
      2114296.30     13878503.21      2113525.00     13878575.00
      2113013.05     13878593.02
#Sta/Elev= 30
  4225.7 1198.36  4295.6 1188.76  4367.6 1181.82  4409.8 1171.04  4468.0 1163.28
  4578.5 1152.99  4648.8 1149.89  4695.1 1144.73  4732.4 1137.91  4739.2 1131.89
  4759.3 1124.26  4769.3 1117.10  4836.5 1095.04  4841.6 1096.05  4849.7 1093.43
  4909.9 1089.09  4990.3 1086.55  5002.8 1083.22  5008.3 1077.42  5008.6 1076.92
  5012.3 1077.42  5040.4 1082.77  5060.4 1097.12  5120.4 1118.06  5138.9 1126.50
  5143.9 1123.55  5151.4 1127.89  5180.4 1135.28  5448.7 1155.65  5512.6 1157.75
#Mann=6,-1,0
  4225.7    0.07       0  4695.1    0.12       0  5008.3    0.05       0
  5012.3    0.12       0  5151.4    0.07       0  5448.7   0.035       0
Bank Sta=5008.3,5012.3
Exp/Cntr=0.3,0.1

Type RM Length L Ch R = 1,952,455,455,455
BEGIN DESCRIPTION:
Stream0245_DS 2.0
END DESCRIPTION:
XS GIS Cut Line= 3
      2113955.12     13878233.02      2113525.00     13878125.00
      2113144.80     13878207.84
#Sta/Elev= 30
  4556.1 1152.35  4655.8 1146.33  4734.7 1140.66  4770.7 1135.75  4803.7 1125.65
  4853.0 1103.38  4894.1 1090.77  4899.3 1090.88  4935.3 1080.28  4940.4 1080.81
  4976.4 1068.58  4987.3 1068.14  4987.5 1067.64  4991.3 1068.14  4997.0 1071.62
  5002.1 1071.62  5019.0 1083.20  5024.1 1083.04  5030.3 1086.52  5091.7 1095.39
  5117.1 1097.37  5142.9 1105.14  5161.1 1114.27  5166.2 1114.71  5194.0 1129.22
  5204.3 1132.03  5210.2 1136.46  5243.4 1139.94  5347.1 1150.99  5388.7 1152.35
#Mann=5,-1,0
  4556.1    0.07       0  4655.8    0.12       0  4987.3    0.05       0
  4991.3    0.12       0  5243.4   0.035       0
Bank Sta=4987.3,4991.3
Exp/Cntr=0.3,0.1

Type RM Length L Ch R = 1,497,0,0,0
BEGIN DESCRIPTION:
Stream0245_DS 1.0
END DESCRIPTION:
XS GIS Cut Line= 3
      2114146.56     13878056.14      2113675.00     13877725.00
      2113200.01     13877950.00
#Sta/Elev= 30
  4423.0 1159.63  4533.4 1150.60  4619.7 1148.32  4675.5 1143.03  4741.7 1136.79
  4768.7 1131.03  4783.5 1126.55  4804.5 1114.18  4840.4 1100.44  4877.0 1091.45
  4913.7 1089.20  4950.0 1081.80  4989.8 1066.40  4990.1 1065.90  4993.8 1066.40
  5002.0 1067.57  5021.3 1078.41  5030.6 1080.94  5036.1 1079.24  5053.3 1086.53
  5200.8 1097.64  5240.8 1108.60  5263.5 1112.53  5269.1 1111.37  5286.3 1117.16
  5291.8 1115.72  5298.0 1119.92  5331.0 1127.30  5486.1 1143.14  5524.8 1144.76
#Mann=5,-1,0
  4423.0    0.07       0  4675.5    0.12       0  4989.8    0.05       0
  4993.8    0.12       0  5331.0   0.035       0
Bank Sta=4989.8,4993.8
Exp/Cntr=0.3,0.1

Chan Stop Cuts=-1