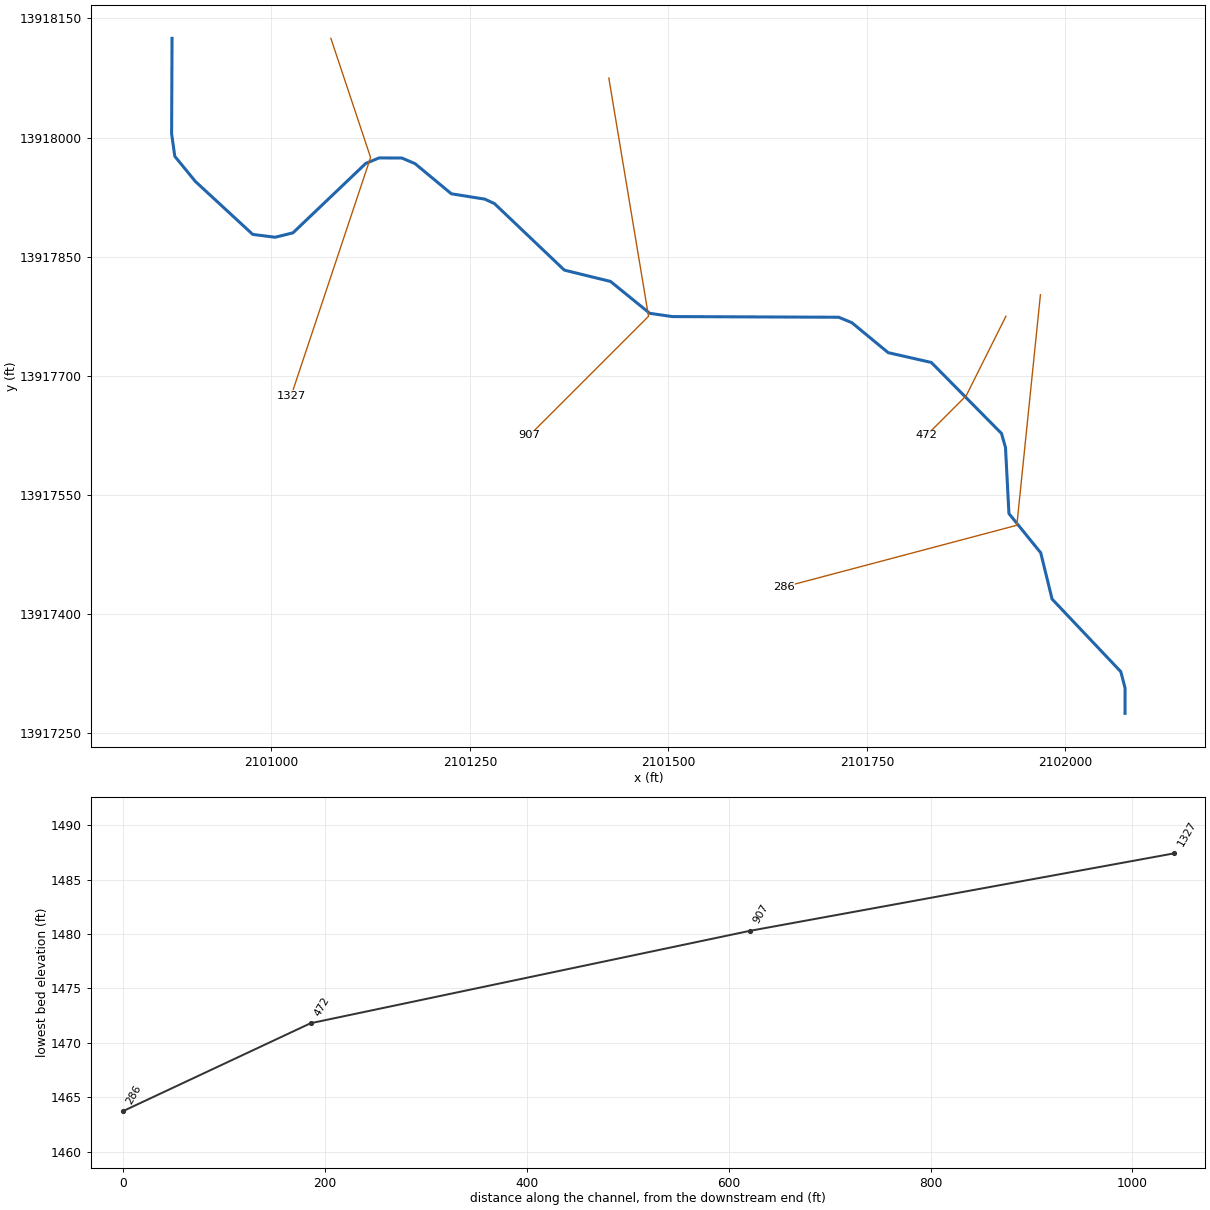
--- Stream0248_DS.prj (project) ---

Proj Title=Stream0248_DS Base Level Engineering
Current Plan=p01
Default Exp/Contr=0.3,0.1
English Units
Geom File=g01
Flow File=f01
Plan File=p01
BEGIN DESCRIPTION:
Stream0248_DS
END DESCRIPTION:

--- Stream0248_DS.p01 (plan) ---

Plan Title=Multiple Run
Short Identifier=Multiple
Geom File=g01
Flow File=f01
Subcritical Flow
K Sum by GR= 0
Std Step Tol= 0.01
Critical Tol= 0.01
Num of Std Step Trials= 20
Max Error Tol= 0.3
Flow Tol Ratio= 0.001
Split Flow NTrial= 30
Split Flow Tol= 0.02
Split Flow Ratio= 0.02
Log Output Level= 0
Friction Slope Method= 1
Unsteady Friction Slope Method= 2
Unsteady Bridges Friction Slope Method= 1
Parabolic Critical Depth
Global Vel Dist=  1 , 1 , 1
Global Log Level= 0
CheckData=True
Encroach Param= -1, 0, 0, 0
BEGIN DESCRIPTION:
Multiple Run
END DESCRIPTION:

--- Stream0248_DS.f01 (steady flow) ---

Flow Title=Multiple
Number of Profiles=7
Profile Names=10-year,25-year,50-year,1pct_min,100-year,1pct_plu,500-year
River Rch & RM= Stream0248_DS,Reach-1,1327
     454     739    1002     663    1322    2639    2274
Boundary for River Rch & Prof#=Stream0248_DS,Reach-1,1
Up Type=0
Dn Type=3
Dn Slope=0.005
Boundary for River Rch & Prof#=Stream0248_DS,Reach-1,2
Up Type=0
Dn Type=3
Dn Slope=0.005
Boundary for River Rch & Prof#=Stream0248_DS,Reach-1,3
Up Type=0
Dn Type=3
Dn Slope=0.005
Boundary for River Rch & Prof#=Stream0248_DS,Reach-1,4
Up Type=0
Dn Type=3
Dn Slope=0.005
Boundary for River Rch & Prof#=Stream0248_DS,Reach-1,5
Up Type=0
Dn Type=3
Dn Slope=0.005
Boundary for River Rch & Prof#=Stream0248_DS,Reach-1,6
Up Type=0
Dn Type=3
Dn Slope=0.005
Boundary for River Rch & Prof#=Stream0248_DS,Reach-1,7
Up Type=0
Dn Type=3
Dn Slope=0.005

--- Stream0248_DS.g01 (geometry) ---

Geom Title=Existing Conditions

River Reach=Stream0248_DS,Reach-1
Reach XY= 30
      2100875.00     13918125.00      2100874.48     13918004.78
      2100878.49     13917976.43      2100904.48     13917944.71
      2100976.63     13917878.09      2101004.83     13917874.53
      2101027.28     13917880.08      2101118.95     13917967.50
      2101135.63     13917974.40      2101164.30     13917974.30
      2101180.93     13917967.26      2101226.73     13917929.25
      2101268.96     13917922.50      2101281.05     13917916.85
      2101368.95     13917833.16      2101427.17     13917818.86
      2101476.55     13917778.75      2101504.85     13917774.64
      2101714.50     13917773.80      2101731.08     13917766.91
      2101776.75     13917729.22      2101831.08     13917716.87
      2101919.48     13917627.44      2101924.48     13917609.79
      2101928.83     13917526.59      2101968.86     13917477.17
      2101983.14     13917418.94      2102069.67     13917327.51
      2102075.07     13917306.88      2102075.00     13917275.00

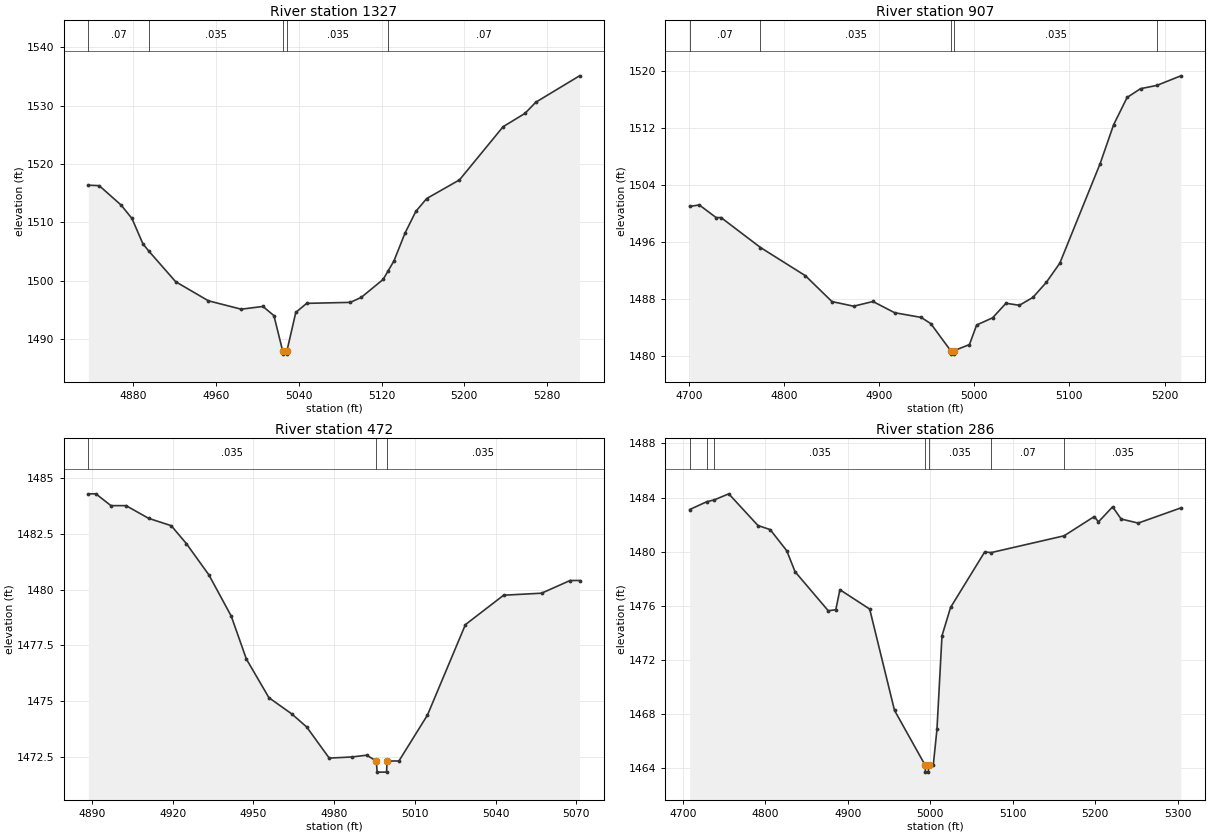
Type RM Length L Ch R = 1,1327,420,420,420
BEGIN DESCRIPTION:
Stream0248_DS 3.0
END DESCRIPTION:
XS GIS Cut Line= 3
      2101075.01     13918124.98      2101125.00     13917975.00
      2101025.01     13917675.02
#Sta/Elev= 30
  4836.9 1516.35  4847.4 1516.27  4868.5 1512.95  4879.0 1510.65  4889.6 1506.30
  4895.1 1505.10  4921.2 1499.81  4952.8 1496.54  4984.5 1495.10  5005.5 1495.57
  5016.1 1494.00  5024.6 1487.90  5024.9 1487.40  5028.4 1487.40  5028.6 1487.90
  5037.2 1494.54  5047.7 1496.10  5089.9 1496.27  5100.4 1497.12  5121.5 1500.19
  5126.3 1501.64  5132.0 1503.37  5142.6 1508.10  5153.1 1511.85  5163.6 1514.06
  5195.3 1517.26  5237.4 1526.37  5258.5 1528.65  5269.1 1530.58  5311.2 1535.09
#Mann=5,-1,0
  4836.9    0.07       0  4895.1   0.035       0  5024.6   0.035       0
  5028.6   0.035       0  5126.3    0.07       0
Bank Sta=5024.6,5028.6
Exp/Cntr=0.3,0.1

Type RM Length L Ch R = 1,907,435,435,435
BEGIN DESCRIPTION:
Stream0248_DS 2.0
END DESCRIPTION:
XS GIS Cut Line= 3
      2101425.00     13918074.97      2101475.00     13917775.00
      2101325.03     13917625.03
#Sta/Elev= 30
  4700.9 1500.97  4711.0 1501.18  4728.8 1499.40  4733.8 1499.42  4775.3 1495.22
  4822.5 1491.27  4850.4 1487.65  4873.2 1487.00  4893.5 1487.66  4916.3 1486.09
  4944.2 1485.43  4954.3 1484.56  4975.1 1480.79  4975.4 1480.29  4978.9 1480.29
  4979.1 1480.79  4994.9 1481.63  5002.5 1484.37  5019.2 1485.37  5033.3 1487.41
  5047.4 1487.13  5061.6 1488.23  5075.7 1490.34  5089.9 1493.03  5132.3 1506.98
  5146.4 1512.40  5160.6 1516.23  5174.7 1517.46  5191.9 1517.92  5217.1 1519.26
#Mann=5,-1,0
  4700.9    0.07       0  4775.3   0.035       0  4975.1   0.035       0
  4979.1   0.035       0  5191.9    0.07       0
Bank Sta=4975.1,4979.1
Exp/Cntr=0.3,0.1

Type RM Length L Ch R = 1,472,186,186,186
BEGIN DESCRIPTION:
Stream0248_DS 1.0
END DESCRIPTION:
XS GIS Cut Line= 3
      2101925.01     13917775.03      2101875.00     13917675.00
      2101825.03     13917625.03
#Sta/Elev= 28
  4888.7 1484.30  4891.5 1484.30  4897.1 1483.77  4902.7 1483.77  4911.1 1483.20
  4919.5 1482.87  4925.1 1482.07  4933.5 1480.66  4941.8 1478.81  4947.4 1476.89
  4955.8 1475.15  4964.2 1474.43  4969.8 1473.84  4978.2 1472.44  4986.6 1472.49
  4992.1 1472.57  4995.7 1472.31  4996.0 1471.81  4999.5 1471.81  4999.7 1472.31
  5000.5 1472.31  5004.1 1472.31  5014.7 1474.37  5028.8 1478.43  5043.0 1479.75
  5057.1 1479.84  5067.7 1480.41  5071.2 1480.41
#Mann=3,-1,0
  4888.7   0.035       0  4995.7   0.035       0  4999.7   0.035       0
Bank Sta=4995.7,4999.7
Exp/Cntr=0.3,0.1

Type RM Length L Ch R = 1,286,0,0,0
BEGIN DESCRIPTION:
Stream0248_DS 0.0
END DESCRIPTION:
XS GIS Cut Line= 3
      2101968.46     13917802.13      2101938.76     13917511.84
      2101644.99     13917434.01
#Sta/Elev= 30
  4708.2 1483.12  4729.0 1483.70  4737.9 1483.83  4755.6 1484.28  4791.0 1481.94
  4805.8 1481.64  4825.9 1480.08  4836.0 1478.53  4876.2 1475.65  4885.4 1475.72
  4890.4 1477.20  4926.5 1475.77  4956.6 1468.29  4993.9 1464.23  4994.1 1463.73
  4997.6 1463.73  4997.9 1464.23  5003.6 1464.23  5008.1 1466.89  5014.2 1473.80
  5024.6 1475.89  5066.0 1479.99  5073.8 1479.94  5162.3 1481.18  5198.8 1482.60
  5204.0 1482.21  5221.1 1483.32  5231.5 1482.42  5252.2 1482.12  5303.9 1483.24
#Mann=7,-1,0
  4708.2   0.035       0  4729.0    0.07       0  4737.9   0.035       0
  4993.9   0.035       0  4997.9   0.035       0  5073.8    0.07       0
  5162.3   0.035       0
Bank Sta=4993.9,4997.9
Exp/Cntr=0.3,0.1

Chan Stop Cuts=-1