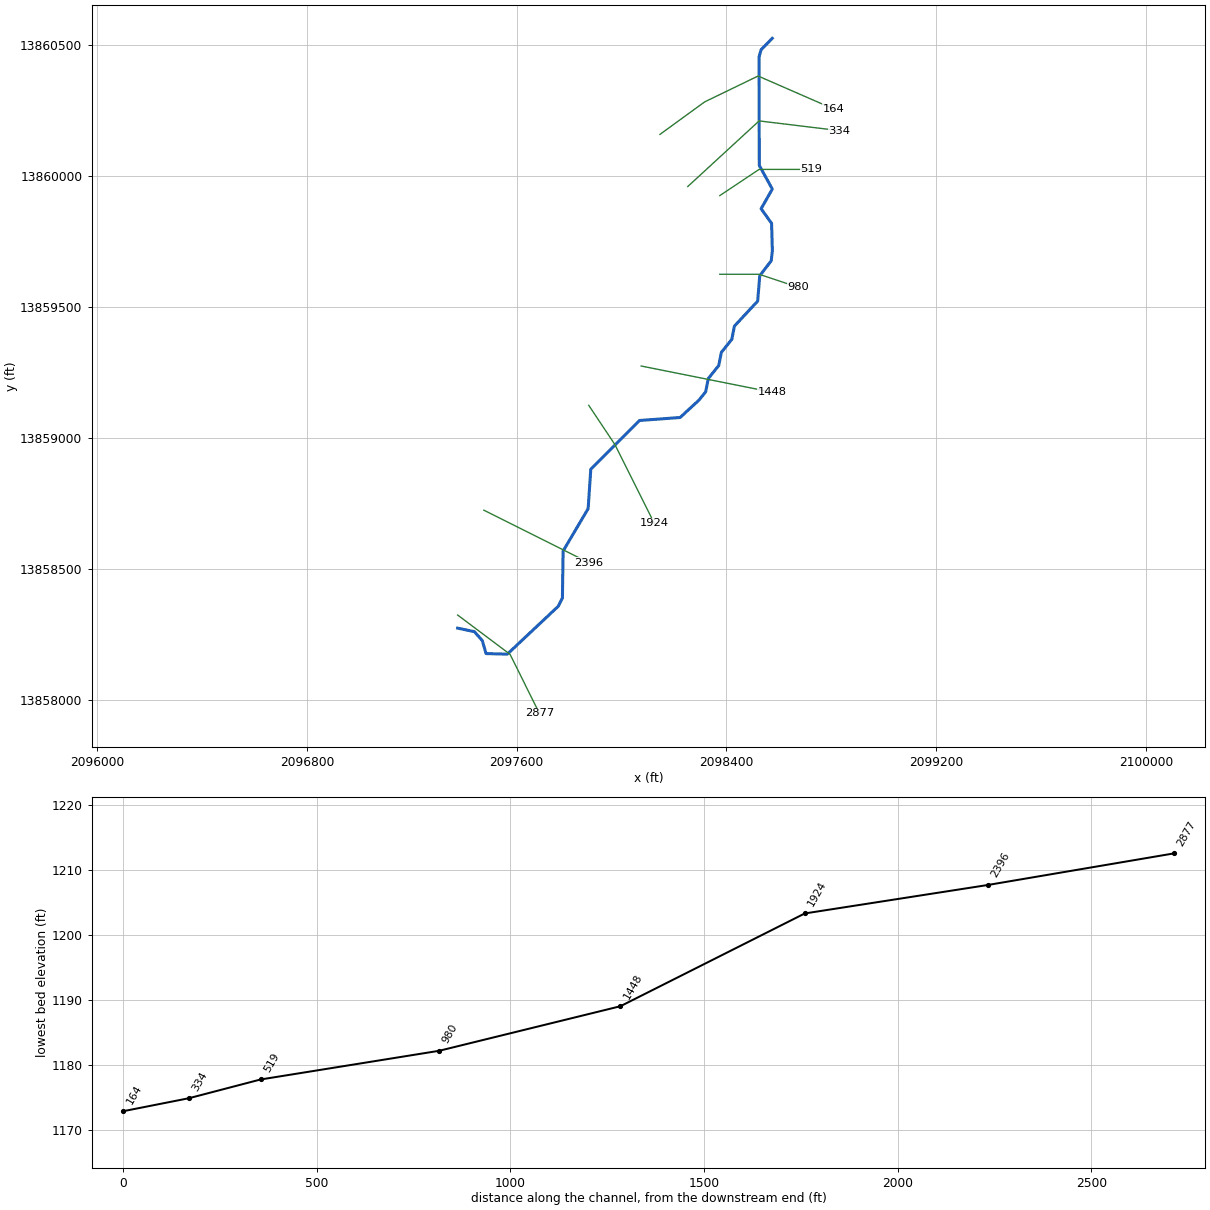
--- Stream0249_DS.prj (project) ---

Proj Title=Stream0249_DS Base Level Engineering
Current Plan=p01
Default Exp/Contr=0.3,0.1
English Units
Geom File=g01
Flow File=f01
Plan File=p01
BEGIN DESCRIPTION:
Stream0249_DS
END DESCRIPTION:

--- Stream0249_DS.p01 (plan) ---

Plan Title=Multiple Run
Short Identifier=Multiple
Geom File=g01
Flow File=f01
Subcritical Flow
K Sum by GR= 0
Std Step Tol= 0.01
Critical Tol= 0.01
Num of Std Step Trials= 20
Max Error Tol= 0.3
Flow Tol Ratio= 0.001
Split Flow NTrial= 30
Split Flow Tol= 0.02
Split Flow Ratio= 0.02
Log Output Level= 0
Friction Slope Method= 1
Unsteady Friction Slope Method= 2
Unsteady Bridges Friction Slope Method= 1
Parabolic Critical Depth
Global Vel Dist=  1 , 1 , 1
Global Log Level= 0
CheckData=True
Encroach Param= -1, 0, 0, 0
BEGIN DESCRIPTION:
Multiple Run
END DESCRIPTION:

--- Stream0249_DS.f01 (steady flow) ---

Flow Title=Multiple
Number of Profiles=7
Profile Names=10-year,25-year,50-year,1pct_min,100-year,1pct_plu,500-year
River Rch & RM= Stream0249_DS,Reach-1,2877
    1152    1963    2740    1855    3701    7385    6676
Boundary for River Rch & Prof#=Stream0249_DS,Reach-1,1
Up Type=0
Dn Type=3
Dn Slope=0.005
Boundary for River Rch & Prof#=Stream0249_DS,Reach-1,2
Up Type=0
Dn Type=3
Dn Slope=0.005
Boundary for River Rch & Prof#=Stream0249_DS,Reach-1,3
Up Type=0
Dn Type=3
Dn Slope=0.005
Boundary for River Rch & Prof#=Stream0249_DS,Reach-1,4
Up Type=0
Dn Type=3
Dn Slope=0.005
Boundary for River Rch & Prof#=Stream0249_DS,Reach-1,5
Up Type=0
Dn Type=3
Dn Slope=0.005
Boundary for River Rch & Prof#=Stream0249_DS,Reach-1,6
Up Type=0
Dn Type=3
Dn Slope=0.005
Boundary for River Rch & Prof#=Stream0249_DS,Reach-1,7
Up Type=0
Dn Type=3
Dn Slope=0.005

--- Stream0249_DS.g01 (geometry) ---

Geom Title=Existing Conditions

River Reach=Stream0249_DS,Reach-1
Reach XY= 30
      2097375.00     13858275.00      2097438.74     13858261.63
      2097469.11     13858227.06      2097483.32     13858177.97
      2097564.41     13858175.88      2097758.57     13858358.24
      2097774.62     13858390.16      2097777.24     13858569.07
      2097872.75     13858730.93      2097882.82     13858881.19
      2098068.81     13859067.18      2098223.54     13859078.54
      2098295.42     13859144.76      2098321.06     13859176.62
      2098331.10     13859227.18      2098370.84     13859276.72
      2098381.08     13859327.20      2098420.81     13859376.74
      2098430.85     13859427.29      2098519.46     13859522.58
      2098527.36     13859619.02      2098571.23     13859676.57
      2098575.50     13859714.83      2098572.55     13859819.14
      2098532.59     13859875.01      2098575.31     13859949.96
      2098525.54     13860040.21      2098524.98     13860455.01
      2098532.43     13860481.35      2098575.00     13860525.00

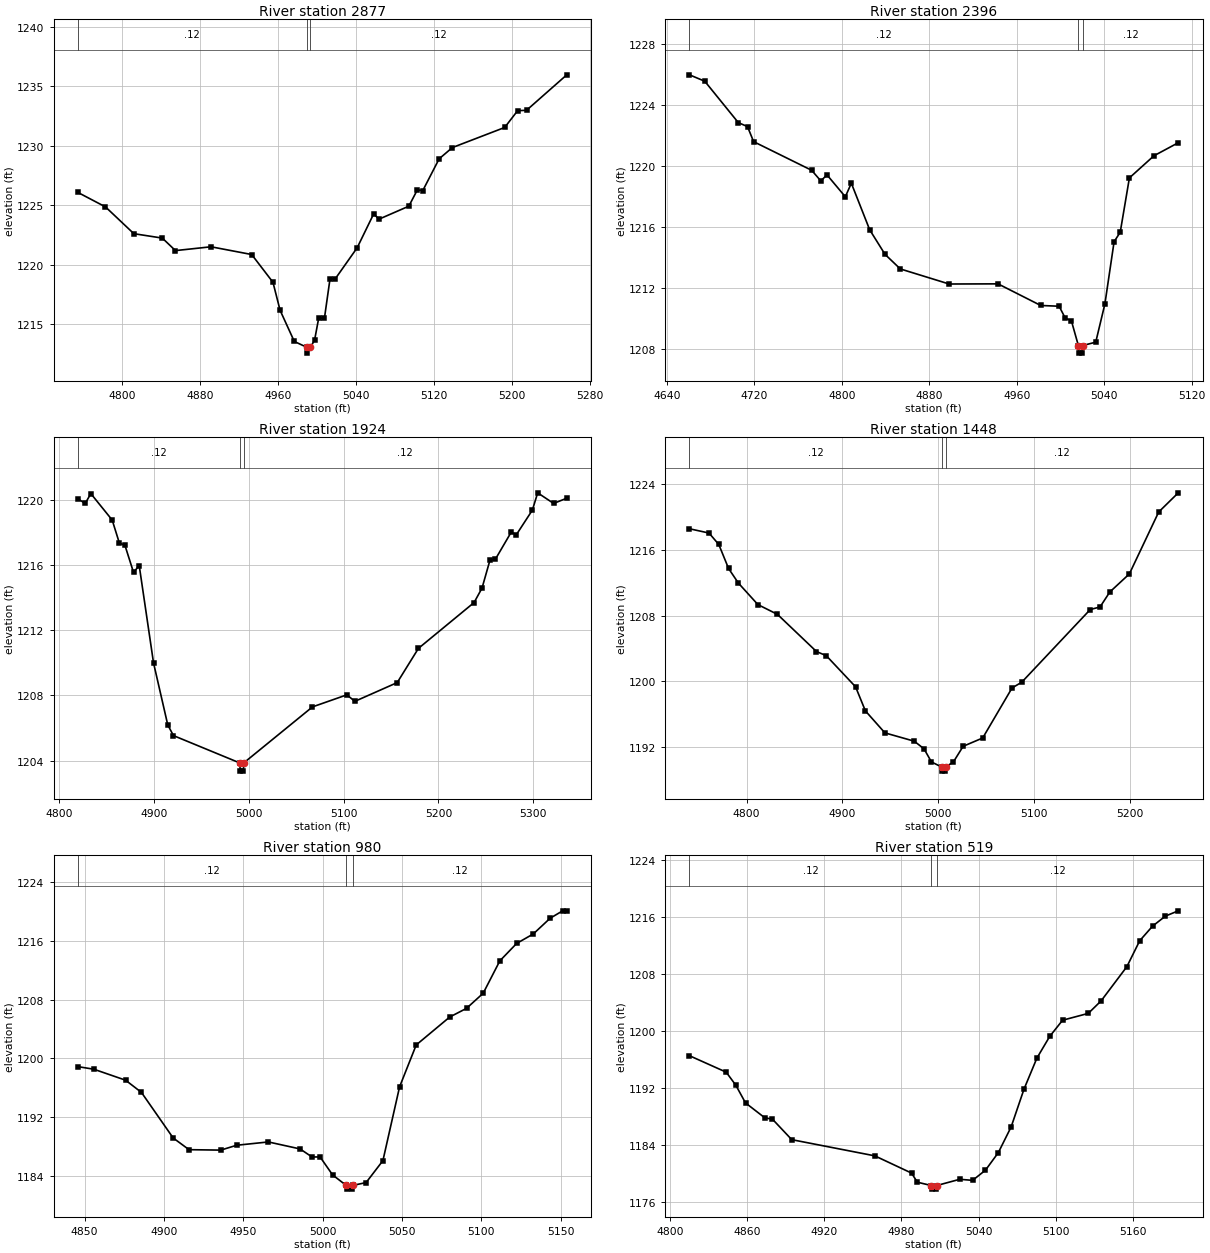
Type RM Length L Ch R = 1,2877,481,481,481
BEGIN DESCRIPTION:
Stream0249_DS 6.0
END DESCRIPTION:
XS GIS Cut Line= 3
      2097374.97     13858325.02      2097575.00     13858175.00
      2097686.81     13857949.88
#Sta/Elev= 30
  4754.5 1226.07  4782.7 1224.86  4811.8 1222.61  4841.0 1222.24  4854.5 1221.19
  4891.0 1221.51  4932.7 1220.86  4954.5 1218.53  4961.8 1216.18  4976.4 1213.56
  4989.0 1213.08  4989.2 1212.58  4993.0 1213.08  4997.2 1213.67  5001.4 1215.51
  5007.3 1215.51  5013.0 1218.80  5018.5 1218.83  5040.9 1221.43  5057.8 1224.27
  5063.3 1223.83  5093.9 1224.92  5102.6 1226.29  5108.2 1226.23  5125.0 1228.90
  5138.5 1229.84  5192.2 1231.53  5205.5 1232.94  5214.6 1232.97  5255.9 1235.95
#Mann=3,-1,0
  4754.5    0.12       0  4989.0    0.05       0  4993.0    0.12       0
Bank Sta=4989,4993
Exp/Cntr=0.3,0.1

Type RM Length L Ch R = 1,2396,472,472,472
BEGIN DESCRIPTION:
Stream0249_DS 5.0
END DESCRIPTION:
XS GIS Cut Line= 3
      2097475.00     13858725.00      2097775.00     13858575.00
      2097874.99     13858525.01
#Sta/Elev= 30
  4660.5 1226.00  4674.5 1225.58  4705.2 1222.86  4713.6 1222.60  4719.2 1221.61
  4772.3 1219.73  4780.7 1219.03  4786.3 1219.43  4803.1 1217.99  4808.6 1218.88
  4825.4 1215.82  4839.4 1214.21  4853.4 1213.25  4898.1 1212.26  4942.8 1212.27
  4981.9 1210.85  4998.7 1210.80  5004.3 1210.02  5009.9 1209.85  5016.3 1208.22
  5016.5 1207.72  5020.0 1207.72  5020.3 1208.22  5032.2 1208.44  5040.6 1210.96
  5049.0 1215.04  5054.6 1215.66  5063.0 1219.23  5085.4 1220.68  5107.7 1221.54
#Mann=3,-1,0
  4660.5    0.12       0  5016.3    0.05       0  5020.3    0.12       0
Bank Sta=5016.3,5020.3
Exp/Cntr=0.3,0.1

Type RM Length L Ch R = 1,1924,476,476,476
BEGIN DESCRIPTION:
Stream0249_DS 4.0
END DESCRIPTION:
XS GIS Cut Line= 3
      2097874.97     13859125.04      2097975.00     13858975.00
      2098124.98     13858675.03
#Sta/Elev= 30
  4819.7 1220.05  4827.3 1219.77  4833.3 1220.37  4855.8 1218.75  4863.3 1217.35
  4869.3 1217.19  4878.3 1215.54  4884.3 1215.96  4899.4 1209.99  4914.4 1206.19
  4920.4 1205.53  4990.5 1203.85  4990.8 1203.35  4994.3 1203.35  4994.5 1203.85
  5067.1 1207.29  5103.4 1208.03  5111.8 1207.63  5156.5 1208.78  5178.9 1210.88
  5237.6 1213.69  5246.0 1214.58  5254.4 1216.30  5260.0 1216.34  5276.7 1218.00
  5282.3 1217.86  5299.1 1219.36  5304.7 1220.42  5321.5 1219.77  5335.4 1220.09
#Mann=3,-1,0
  4819.7    0.12       0  4990.5    0.05       0  4994.5    0.12       0
Bank Sta=4990.5,4994.5
Exp/Cntr=0.3,0.1

Type RM Length L Ch R = 1,1448,468,468,468
BEGIN DESCRIPTION:
Stream0249_DS 3.0
END DESCRIPTION:
XS GIS Cut Line= 3
      2098075.03     13859274.99      2098325.00     13859225.00
      2098575.03     13859174.99
#Sta/Elev= 30
  4740.4 1218.56  4760.8 1218.04  4771.0 1216.65  4781.2 1213.73  4791.4 1211.96
  4811.8 1209.34  4832.2 1208.15  4872.9 1203.63  4883.1 1203.13  4913.7 1199.34
  4923.9 1196.42  4944.3 1193.74  4974.9 1192.73  4985.1 1191.80  4992.8 1190.21
  5003.5 1189.59  5003.8 1189.09  5007.3 1189.09  5007.5 1189.59  5015.7 1190.20
  5025.9 1192.11  5046.3 1193.12  5076.9 1199.20  5087.1 1199.91  5158.5 1208.74
  5168.7 1209.05  5178.9 1210.87  5199.3 1213.07  5229.9 1220.60  5250.3 1222.93
#Mann=3,-1,0
  4740.4    0.12       0  5003.5    0.05       0  5007.5    0.12       0
Bank Sta=5003.5,5007.5
Exp/Cntr=0.3,0.1

Type RM Length L Ch R = 1,980,461,461,461
BEGIN DESCRIPTION:
Stream0249_DS 2.0
END DESCRIPTION:
XS GIS Cut Line= 3
      2098375.01     13859625.00      2098525.00     13859625.00
      2098675.00     13859575.00
#Sta/Elev= 30
  4845.8 1198.88  4855.8 1198.53  4875.8 1197.04  4885.8 1195.38  4905.8 1189.19
  4915.8 1187.60  4935.8 1187.54  4945.8 1188.20  4965.8 1188.65  4985.8 1187.70
  4993.3 1186.61  4998.4 1186.61  5006.3 1184.17  5014.9 1182.74  5015.1 1182.24
  5018.6 1182.24  5018.9 1182.74  5027.4 1183.13  5038.0 1186.11  5048.5 1196.13
  5059.0 1201.83  5080.1 1205.62  5090.7 1206.80  5101.2 1208.85  5111.7 1213.25
  5122.3 1215.62  5132.8 1216.91  5143.4 1219.04  5151.3 1220.05  5153.9 1220.05
#Mann=3,-1,0
  4845.8    0.12       0  5014.9    0.05       0  5018.9    0.12       0
Bank Sta=5014.9,5018.9
Exp/Cntr=0.3,0.1

Type RM Length L Ch R = 1,519,185,185,185
BEGIN DESCRIPTION:
Stream0249_DS 1.0
END DESCRIPTION:
XS GIS Cut Line= 3
      2098374.98     13859924.99      2098525.00     13860025.00
      2098725.00     13860025.00
#Sta/Elev= 30
  4815.1 1196.55  4843.7 1194.24  4851.2 1192.40  4858.7 1189.93  4873.7 1187.84
  4879.7 1187.64  4894.7 1184.77  4959.3 1182.50  4987.9 1180.08  4992.4 1178.80
  5003.4 1178.33  5003.7 1177.83  5007.2 1177.83  5007.4 1178.33  5025.4 1179.21
  5035.4 1179.06  5045.4 1180.49  5055.4 1182.95  5065.4 1186.57  5075.4 1191.87
  5085.4 1196.21  5095.4 1199.26  5105.4 1201.53  5125.4 1202.49  5135.4 1204.25
  5155.4 1209.04  5165.4 1212.68  5175.4 1214.73  5185.4 1216.14  5195.4 1216.88
#Mann=3,-1,0
  4815.1    0.12       0  5003.4    0.05       0  5007.4    0.12       0
Bank Sta=5003.4,5007.4
Exp/Cntr=0.3,0.1

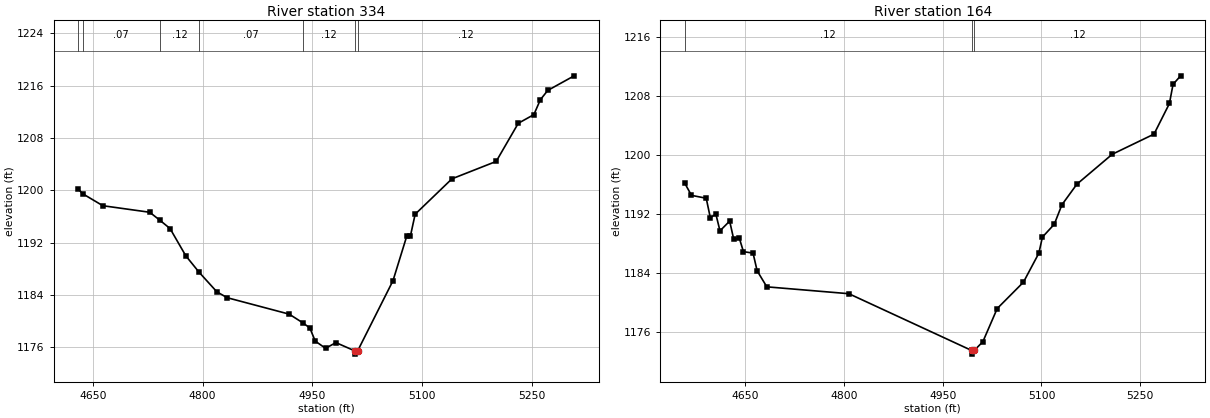
Type RM Length L Ch R = 1,334,170,170,170
BEGIN DESCRIPTION:
Stream0249_DS 0.1
END DESCRIPTION:
XS GIS Cut Line= 3
      2098252.81     13859959.67      2098525.00     13860210.00
      2098830.86     13860172.89
#Sta/Elev= 30
  4630.2 1200.16  4636.0 1199.47  4663.7 1197.63  4727.8 1196.63  4741.7 1195.41
  4755.6 1194.14  4777.1 1189.98  4795.4 1187.45  4819.7 1184.46  4833.8 1183.57
  4918.5 1181.06  4936.9 1179.75  4946.7 1178.95  4954.1 1176.94  4968.2 1175.84
  4982.4 1176.71  5008.1 1175.45  5008.3 1174.95  5012.1 1175.45  5060.4 1186.17
  5079.3 1193.01  5084.3 1193.04  5090.7 1196.33  5141.0 1201.74  5201.5 1204.40
  5231.7 1210.23  5253.0 1211.55  5261.9 1213.83  5272.0 1215.25  5308.1 1217.48
#Mann=7,-1,0
  4630.2    0.12       0  4636.0    0.07       0  4741.7    0.12       0
  4795.4    0.07       0  4936.9    0.12       0  5008.1    0.05       0
  5012.1    0.12       0
Bank Sta=5008.1,5012.1
Exp/Cntr=0.3,0.1

Type RM Length L Ch R = 1,164,0,0,0
BEGIN DESCRIPTION:
Stream0249_DS 0.0
END DESCRIPTION:
XS GIS Cut Line= 4
      2098146.79     13860158.59      2098317.02     13860282.43
      2098521.15     13860381.26      2098810.15     13860255.19
#Sta/Elev= 30
  4558.6 1196.11  4568.7 1194.47  4591.1 1194.08  4597.3 1191.46  4605.8 1191.91
  4612.0 1189.66  4626.7 1190.98  4632.9 1188.50  4641.4 1188.66  4647.6 1186.84
  4662.2 1186.64  4668.4 1184.24  4683.1 1182.07  4807.6 1181.14  4993.9 1173.45
  4994.2 1172.95  4997.9 1173.45  5011.0 1174.63  5032.8 1179.13  5072.6 1182.70
  5096.0 1186.63  5101.4 1188.81  5119.4 1190.55  5131.0 1193.19  5153.7 1195.98
  5207.4 1200.04  5270.8 1202.77  5294.2 1206.92  5299.7 1209.52  5311.2 1210.67
#Mann=3,-1,0
  4558.6    0.12       0  4993.9    0.05       0  4997.9    0.12       0
Bank Sta=4993.9,4997.9
Exp/Cntr=0.3,0.1

Chan Stop Cuts=-1