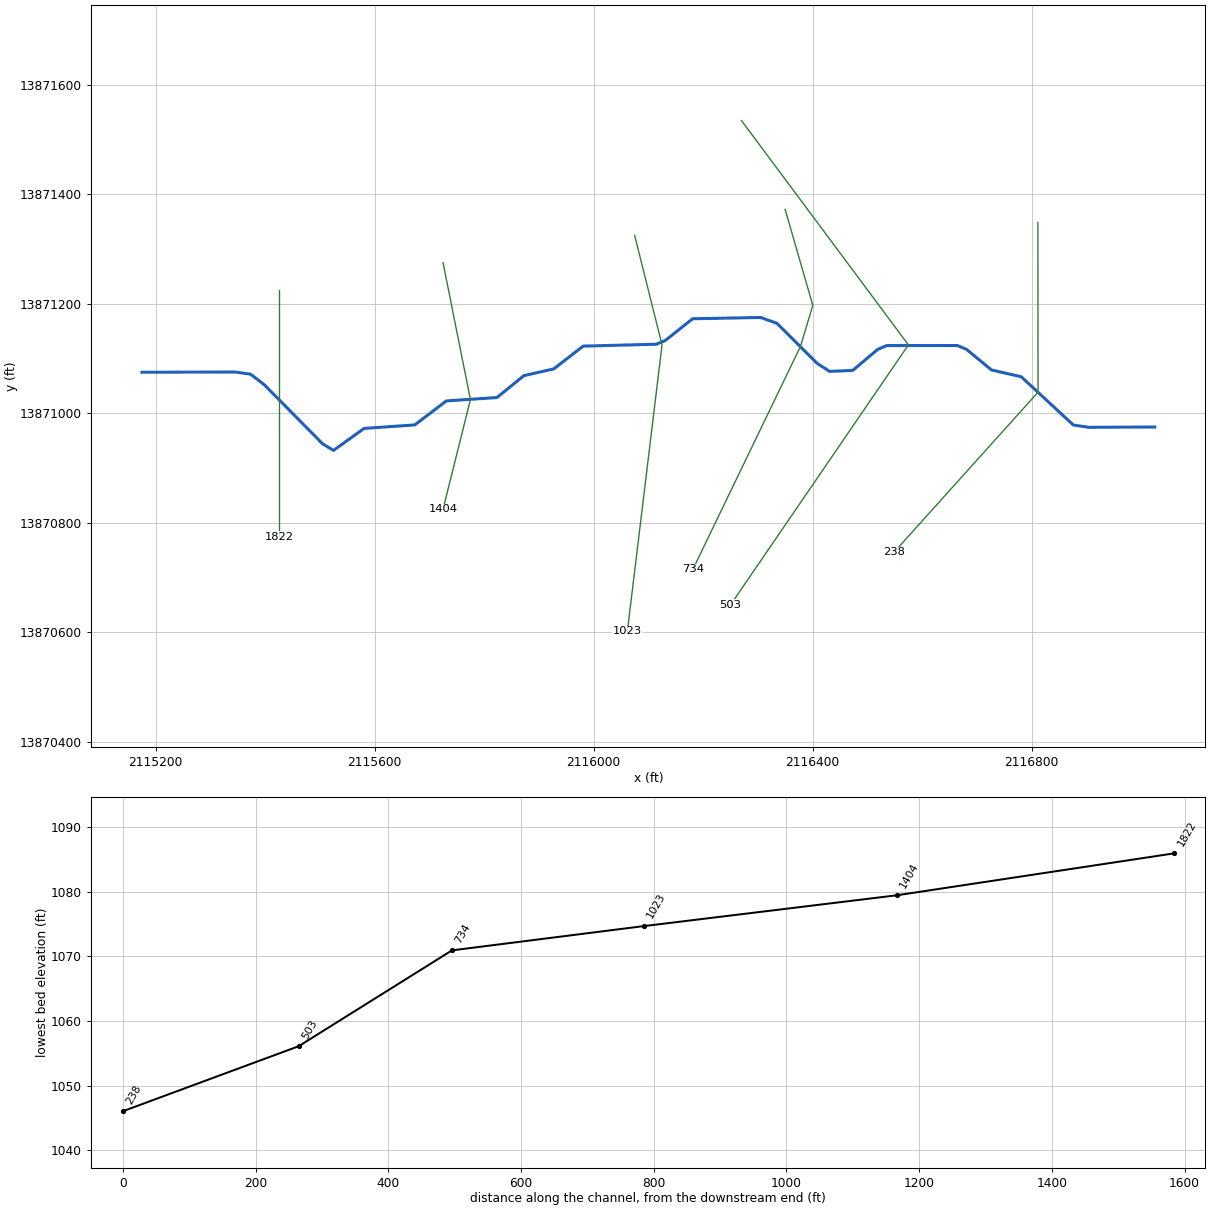
--- Stream0252_DS.prj (project) ---

Proj Title=Stream0252_DS Base Level Engineering
Current Plan=p01
Default Exp/Contr=0.3,0.1
English Units
Geom File=g01
Flow File=f01
Plan File=p01
BEGIN DESCRIPTION:
Stream0252_DS
END DESCRIPTION:

--- Stream0252_DS.p01 (plan) ---

Plan Title=Multiple Run
Short Identifier=Multiple
Geom File=g01
Flow File=f01
Subcritical Flow
K Sum by GR= 0
Std Step Tol= 0.01
Critical Tol= 0.01
Num of Std Step Trials= 20
Max Error Tol= 0.3
Flow Tol Ratio= 0.001
Split Flow NTrial= 30
Split Flow Tol= 0.02
Split Flow Ratio= 0.02
Log Output Level= 0
Friction Slope Method= 1
Unsteady Friction Slope Method= 2
Unsteady Bridges Friction Slope Method= 1
Parabolic Critical Depth
Global Vel Dist=  1 , 1 , 1
Global Log Level= 0
CheckData=True
Encroach Param= -1, 0, 0, 0
BEGIN DESCRIPTION:
Multiple Run
END DESCRIPTION:

--- Stream0252_DS.f01 (steady flow) ---

Flow Title=Multiple
Number of Profiles=7
Profile Names=10-year,25-year,50-year,1pct_min,100-year,1pct_plu,500-year
River Rch & RM= Stream0252_DS,Reach-1,1822
     512     828    1117     733    1462    2917    2471
Boundary for River Rch & Prof#=Stream0252_DS,Reach-1,1
Up Type=0
Dn Type=3
Dn Slope=0.005
Boundary for River Rch & Prof#=Stream0252_DS,Reach-1,2
Up Type=0
Dn Type=3
Dn Slope=0.005
Boundary for River Rch & Prof#=Stream0252_DS,Reach-1,3
Up Type=0
Dn Type=3
Dn Slope=0.005
Boundary for River Rch & Prof#=Stream0252_DS,Reach-1,4
Up Type=0
Dn Type=3
Dn Slope=0.005
Boundary for River Rch & Prof#=Stream0252_DS,Reach-1,5
Up Type=0
Dn Type=3
Dn Slope=0.005
Boundary for River Rch & Prof#=Stream0252_DS,Reach-1,6
Up Type=0
Dn Type=3
Dn Slope=0.005
Boundary for River Rch & Prof#=Stream0252_DS,Reach-1,7
Up Type=0
Dn Type=3
Dn Slope=0.005

--- Stream0252_DS.g01 (geometry) ---

Geom Title=Existing Conditions

River Reach=Stream0252_DS,Reach-1
Reach XY= 30
      2115175.00     13871075.00      2115345.19     13871075.45
      2115373.54     13871071.47      2115398.53     13871052.14
      2115504.97     13870944.29      2115524.90     13870932.31
      2115580.89     13870972.44      2115673.40     13870978.85
      2115730.97     13871022.65      2115823.42     13871028.83
      2115872.82     13871068.89      2115927.18     13871081.12
      2115980.93     13871122.75      2116114.49     13871126.23
      2116131.05     13871133.15      2116180.94     13871172.75
      2116305.01     13871175.06      2116334.79     13871164.50
      2116408.34     13871091.25      2116431.04     13871076.63
      2116473.25     13871078.34      2116518.93     13871116.81
      2116535.50     13871123.77      2116664.50     13871123.81
      2116681.07     13871116.91      2116726.75     13871079.22
      2116781.05     13871066.84      2116876.45     13870978.51
      2116904.79     13870974.49      2117025.00     13870975.00

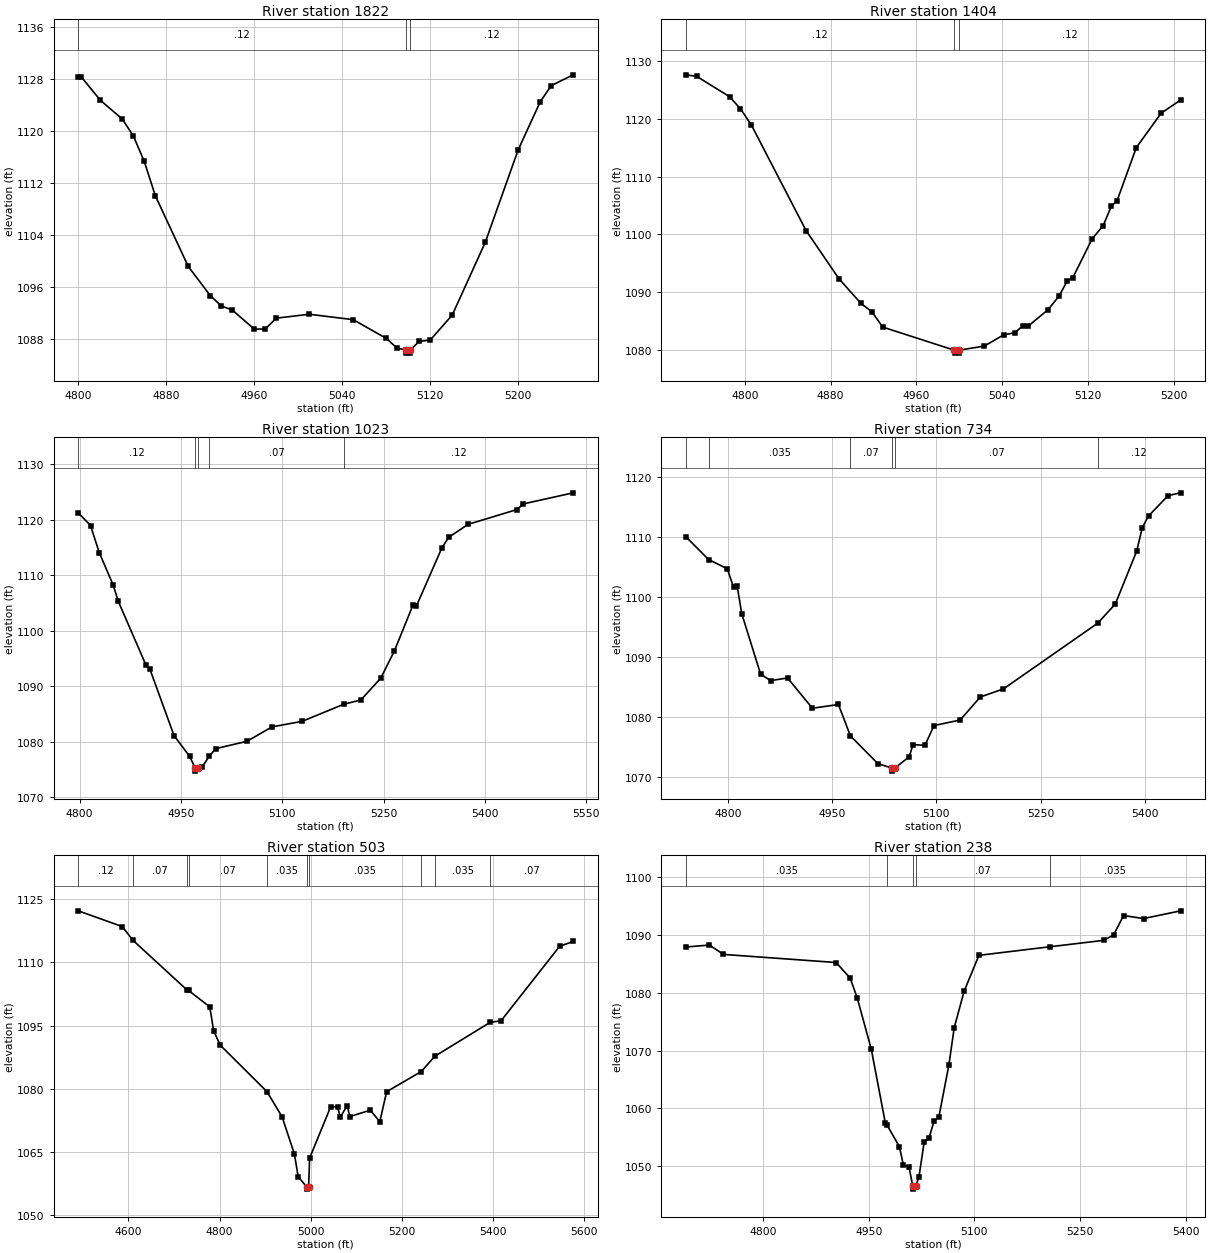
Type RM Length L Ch R = 1,1822,418,418,418
BEGIN DESCRIPTION:
Stream0252_DS 4.0
END DESCRIPTION:
XS GIS Cut Line= 3
      2115425.00     13871224.99      2115425.00     13871025.00
      2115425.00     13870774.99
#Sta/Elev= 30
  4800.4 1128.38  4802.9 1128.38  4820.4 1124.75  4840.4 1121.86  4850.4 1119.28
  4860.4 1115.35  4870.4 1110.09  4900.4 1099.21  4920.4 1094.74  4930.4 1093.15
  4940.4 1092.52  4960.4 1089.59  4970.4 1089.60  4980.4 1091.27  5010.4 1091.87
  5050.4 1091.04  5080.4 1088.16  5090.4 1086.65  5098.4 1086.40  5098.6 1085.90
  5102.1 1085.90  5102.4 1086.40  5110.4 1087.70  5120.4 1087.91  5140.4 1091.75
  5170.4 1102.91  5200.4 1117.15  5220.4 1124.51  5230.4 1127.00  5250.4 1128.65
#Mann=3,-1,0
  4800.4    0.12       0  5098.4    0.05       0  5102.4    0.12       0
Bank Sta=5098.4,5102.4
Exp/Cntr=0.3,0.1

Type RM Length L Ch R = 1,1404,381,381,381
BEGIN DESCRIPTION:
Stream0252_DS 3.0
END DESCRIPTION:
XS GIS Cut Line= 3
      2115724.99     13871275.04      2115775.00     13871025.00
      2115724.99     13870824.95
#Sta/Elev= 30
  4745.0 1127.62  4755.2 1127.36  4785.8 1123.84  4796.0 1121.74  4806.2 1118.92
  4857.2 1100.63  4887.8 1092.30  4908.2 1088.05  4918.4 1086.60  4928.6 1083.93
  4995.4 1079.92  4995.7 1079.42  4999.2 1079.42  4999.4 1079.92  5023.2 1080.64
  5041.2 1082.58  5051.5 1082.95  5059.3 1084.16  5064.4 1084.14  5082.5 1086.92
  5092.8 1089.28  5100.5 1091.93  5105.7 1092.48  5123.7 1099.21  5134.0 1101.51
  5141.7 1104.90  5146.9 1105.80  5164.9 1115.03  5188.1 1121.00  5206.2 1123.26
#Mann=3,-1,0
  4745.0    0.12       0  4995.4    0.05       0  4999.4    0.12       0
Bank Sta=4995.4,4999.4
Exp/Cntr=0.3,0.1

Type RM Length L Ch R = 1,1023,289,289,289
BEGIN DESCRIPTION:
Stream0252_DS 2.0
END DESCRIPTION:
XS GIS Cut Line= 3
      2116074.99     13871325.04      2116125.00     13871125.00
      2116061.71     13870602.11
#Sta/Elev= 30
  4798.0 1121.22  4816.1 1118.93  4829.0 1114.06  4849.6 1108.22  4857.3 1105.24
  4898.5 1093.70  4903.7 1093.15  4939.8 1081.06  4963.0 1077.30  4971.3 1075.16
  4971.5 1074.66  4975.3 1075.16  4981.0 1075.34  4992.0 1077.35  5001.6 1078.72
  5047.7 1080.03  5084.8 1082.63  5129.6 1083.64  5191.0 1086.71  5216.5 1087.49
  5245.9 1091.42  5266.1 1096.33  5293.4 1104.54  5298.4 1104.34  5336.6 1114.96
  5346.7 1116.82  5375.3 1119.14  5447.4 1121.80  5457.2 1122.83  5530.9 1124.82
#Mann=5,-1,0
  4798.0    0.12       0  4971.3    0.05       0  4975.3    0.12       0
  4992.0    0.07       0  5191.0    0.12       0
Bank Sta=4971.3,4975.3
Exp/Cntr=0.3,0.1

Type RM Length L Ch R = 1,734,231,231,231
BEGIN DESCRIPTION:
Stream0252_DS 1.5
END DESCRIPTION:
XS GIS Cut Line= 4
      2116349.81     13871372.53      2116400.40     13871197.25
      2116377.80     13871122.10      2116181.43     13870715.21
#Sta/Elev= 30
  4739.1 1110.05  4772.0 1106.22  4799.0 1104.68  4808.0 1101.57  4813.2 1101.78
  4819.8 1097.17  4846.9 1087.10  4861.4 1086.01  4885.7 1086.46  4921.5 1081.40
  4959.0 1082.03  4976.2 1076.80  5015.7 1072.17  5036.3 1071.41  5036.6 1070.91
  5040.3 1071.41  5060.9 1073.32  5066.5 1075.34  5083.5 1075.20  5096.7 1078.52
  5134.3 1079.44  5163.3 1083.28  5196.6 1084.63  5332.4 1095.60  5357.7 1098.80
  5388.5 1107.63  5396.5 1111.55  5405.6 1113.50  5433.7 1116.89  5451.8 1117.35
#Mann=6,-1,0
  4739.1    0.07       0  4772.0   0.035       0  4976.2    0.07       0
  5036.3    0.05       0  5040.3    0.07       0  5332.4    0.12       0
Bank Sta=5036.3,5040.3
Exp/Cntr=0.3,0.1

Type RM Length L Ch R = 1,503,265,265,265
BEGIN DESCRIPTION:
Stream0252_DS 1.0
END DESCRIPTION:
XS GIS Cut Line= 3
      2116270.07     13871534.78      2116575.00     13871125.00
      2116250.02     13870650.02
#Sta/Elev= 30
  4489.8 1122.27  4586.6 1118.51  4609.5 1115.29  4729.4 1103.35  4731.7 1103.34
  4778.4 1099.43  4786.8 1093.80  4801.1 1090.35  4903.9 1079.27  4937.0 1073.31
  4964.1 1064.45  4972.4 1059.07  4991.3 1056.59  4991.5 1056.09  4995.3 1056.59
  4997.5 1063.46  5043.9 1075.72  5058.8 1075.64  5064.9 1073.18  5079.8 1075.97
  5085.9 1073.35  5130.6 1074.86  5151.6 1072.14  5166.5 1079.25  5242.6 1084.06
  5272.5 1087.70  5393.9 1095.76  5417.7 1096.12  5546.3 1113.85  5576.1 1114.98
#Mann=10,-1,0
  4489.8    0.12       0  4609.5    0.07       0  4729.4   0.035       0
  4731.7    0.07       0  4903.9   0.035       0  4991.3   0.035       0
  4995.3   0.035       0  5242.6    0.07       0  5272.5   0.035       0
  5393.9    0.07       0
Bank Sta=4991.3,4995.3
Exp/Cntr=0.3,0.1

Type RM Length L Ch R = 1,238,0,0,0
BEGIN DESCRIPTION:
Stream0252_DS 0.0
END DESCRIPTION:
XS GIS Cut Line= 3
      2116811.47     13871348.57      2116811.76     13871038.57
      2116548.79     13870746.38
#Sta/Elev= 30
  4690.0 1087.92  4723.6 1088.26  4743.6 1086.64  4903.6 1085.24  4923.6 1082.55
  4933.6 1079.13  4953.6 1070.25  4973.6 1057.45  4976.2 1057.06  4993.6 1053.39
  4999.3 1050.13  5007.1 1049.93  5012.6 1046.54  5012.8 1046.04  5016.6 1046.54
  5021.3 1048.13  5028.8 1054.23  5035.5 1054.89  5043.0 1057.85  5049.7 1058.59
  5063.9 1067.56  5071.4 1073.96  5085.5 1080.28  5106.5 1086.48  5207.7 1087.97
  5283.6 1089.07  5297.8 1090.01  5312.0 1093.37  5340.4 1092.84  5393.1 1094.18
#Mann=5,-1,0
  4690.0   0.035       0  4976.2    0.07       0  5012.6    0.05       0
  5016.6    0.07       0  5207.7   0.035       0
Bank Sta=5012.6,5016.6
Exp/Cntr=0.3,0.1

Chan Stop Cuts=-1