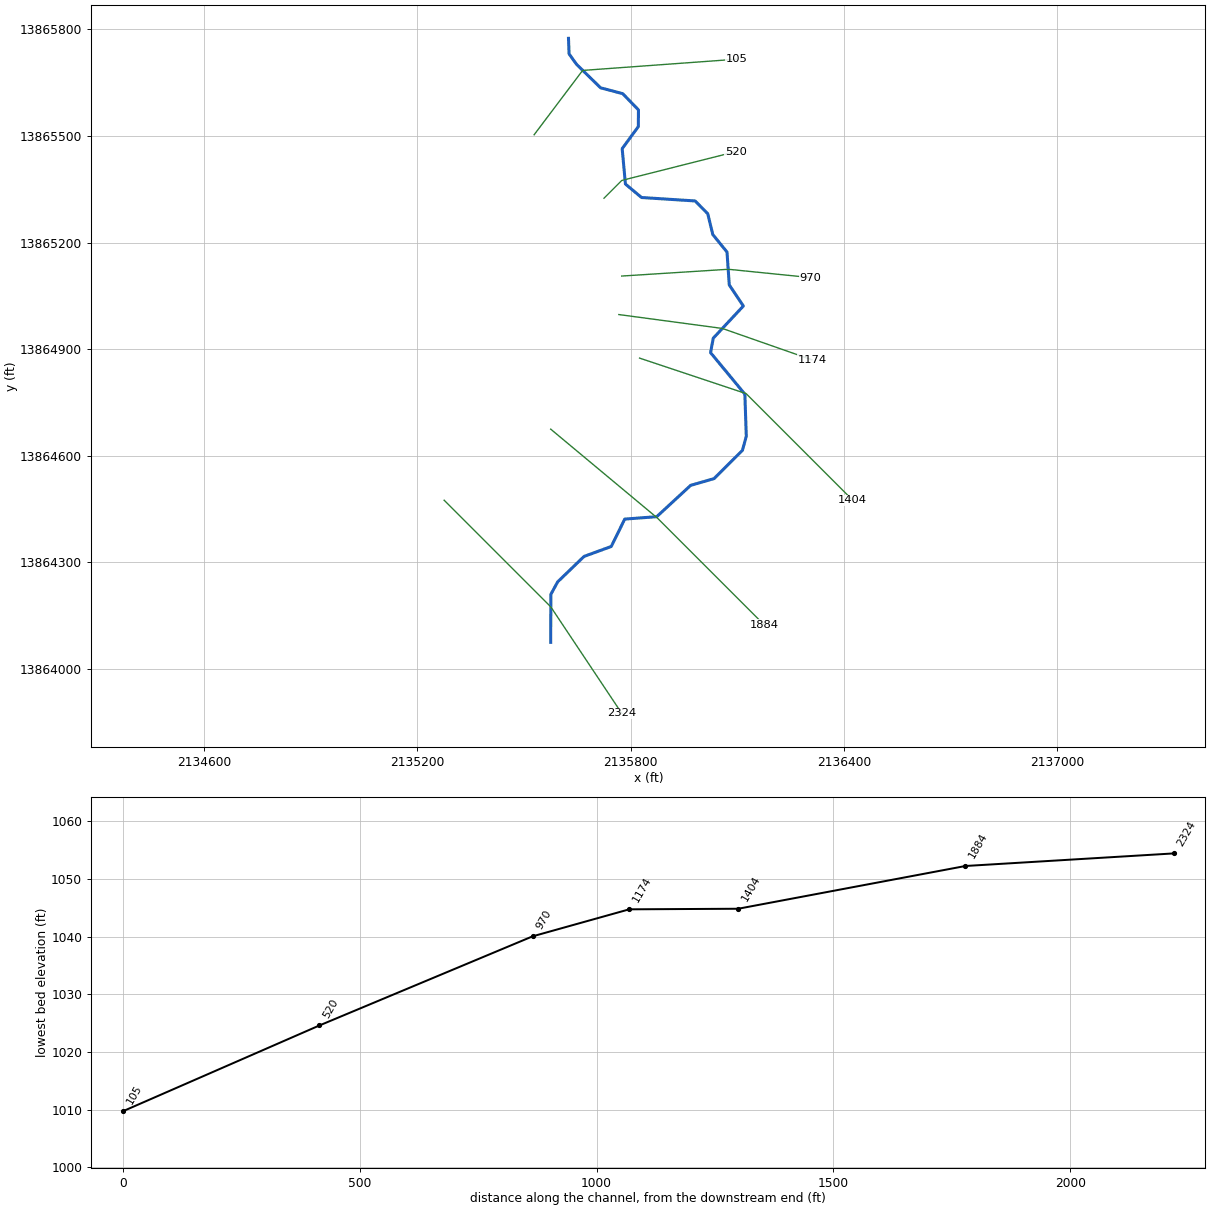
--- Stream0259_DS.prj (project) ---

Proj Title=Stream0259_DS Base Level Engineering
Current Plan=p01
Default Exp/Contr=0.3,0.1
English Units
Geom File=g01
Flow File=f01
Plan File=p01
BEGIN DESCRIPTION:
Stream0259_DS
END DESCRIPTION:

--- Stream0259_DS.p01 (plan) ---

Plan Title=Multiple Run
Short Identifier=Multiple
Geom File=g01
Flow File=f01
Subcritical Flow
K Sum by GR= 0
Std Step Tol= 0.01
Critical Tol= 0.01
Num of Std Step Trials= 20
Max Error Tol= 0.3
Flow Tol Ratio= 0.001
Split Flow NTrial= 30
Split Flow Tol= 0.02
Split Flow Ratio= 0.02
Log Output Level= 0
Friction Slope Method= 1
Unsteady Friction Slope Method= 2
Unsteady Bridges Friction Slope Method= 1
Parabolic Critical Depth
Global Vel Dist=  1 , 1 , 1
Global Log Level= 0
CheckData=True
Encroach Param= -1, 0, 0, 0
BEGIN DESCRIPTION:
Multiple Run
END DESCRIPTION:

--- Stream0259_DS.f01 (steady flow) ---

Flow Title=Multiple
Number of Profiles=7
Profile Names=10-year,25-year,50-year,1pct_min,100-year,1pct_plu,500-year
River Rch & RM= Stream0259_DS,Reach-1,2324
     427     682     913     595    1186    2367    1975
Boundary for River Rch & Prof#=Stream0259_DS,Reach-1,1
Up Type=0
Dn Type=3
Dn Slope=0.005
Boundary for River Rch & Prof#=Stream0259_DS,Reach-1,2
Up Type=0
Dn Type=3
Dn Slope=0.005
Boundary for River Rch & Prof#=Stream0259_DS,Reach-1,3
Up Type=0
Dn Type=3
Dn Slope=0.005
Boundary for River Rch & Prof#=Stream0259_DS,Reach-1,4
Up Type=0
Dn Type=3
Dn Slope=0.005
Boundary for River Rch & Prof#=Stream0259_DS,Reach-1,5
Up Type=0
Dn Type=3
Dn Slope=0.005
Boundary for River Rch & Prof#=Stream0259_DS,Reach-1,6
Up Type=0
Dn Type=3
Dn Slope=0.005
Boundary for River Rch & Prof#=Stream0259_DS,Reach-1,7
Up Type=0
Dn Type=3
Dn Slope=0.005

--- Stream0259_DS.g01 (geometry) ---

Geom Title=Existing Conditions

River Reach=Stream0259_DS,Reach-1
Reach XY= 30
      2135575.00     13864075.00      2135575.31     13864209.88
      2135594.59     13864245.21      2135668.95     13864316.84
      2135745.43     13864344.74      2135783.35     13864421.81
      2135873.43     13864428.65      2135968.96     13864516.82
      2136034.70     13864535.77      2136114.54     13864615.18
      2136125.47     13864654.83      2136121.46     13864773.53
      2136024.90     13864890.36      2136032.50     13864931.05
      2136117.19     13865021.59      2136077.56     13865080.89
      2136071.18     13865173.42      2136031.15     13865222.85
      2136017.00     13865281.39      2135981.48     13865317.30
      2135830.65     13865326.98      2135785.28     13865364.84
      2135776.12     13865464.45      2135821.67     13865526.78
      2135821.96     13865573.58      2135777.61     13865619.25
      2135715.32     13865635.77      2135648.02     13865701.48
      2135626.67     13865731.13      2135625.00     13865775.00

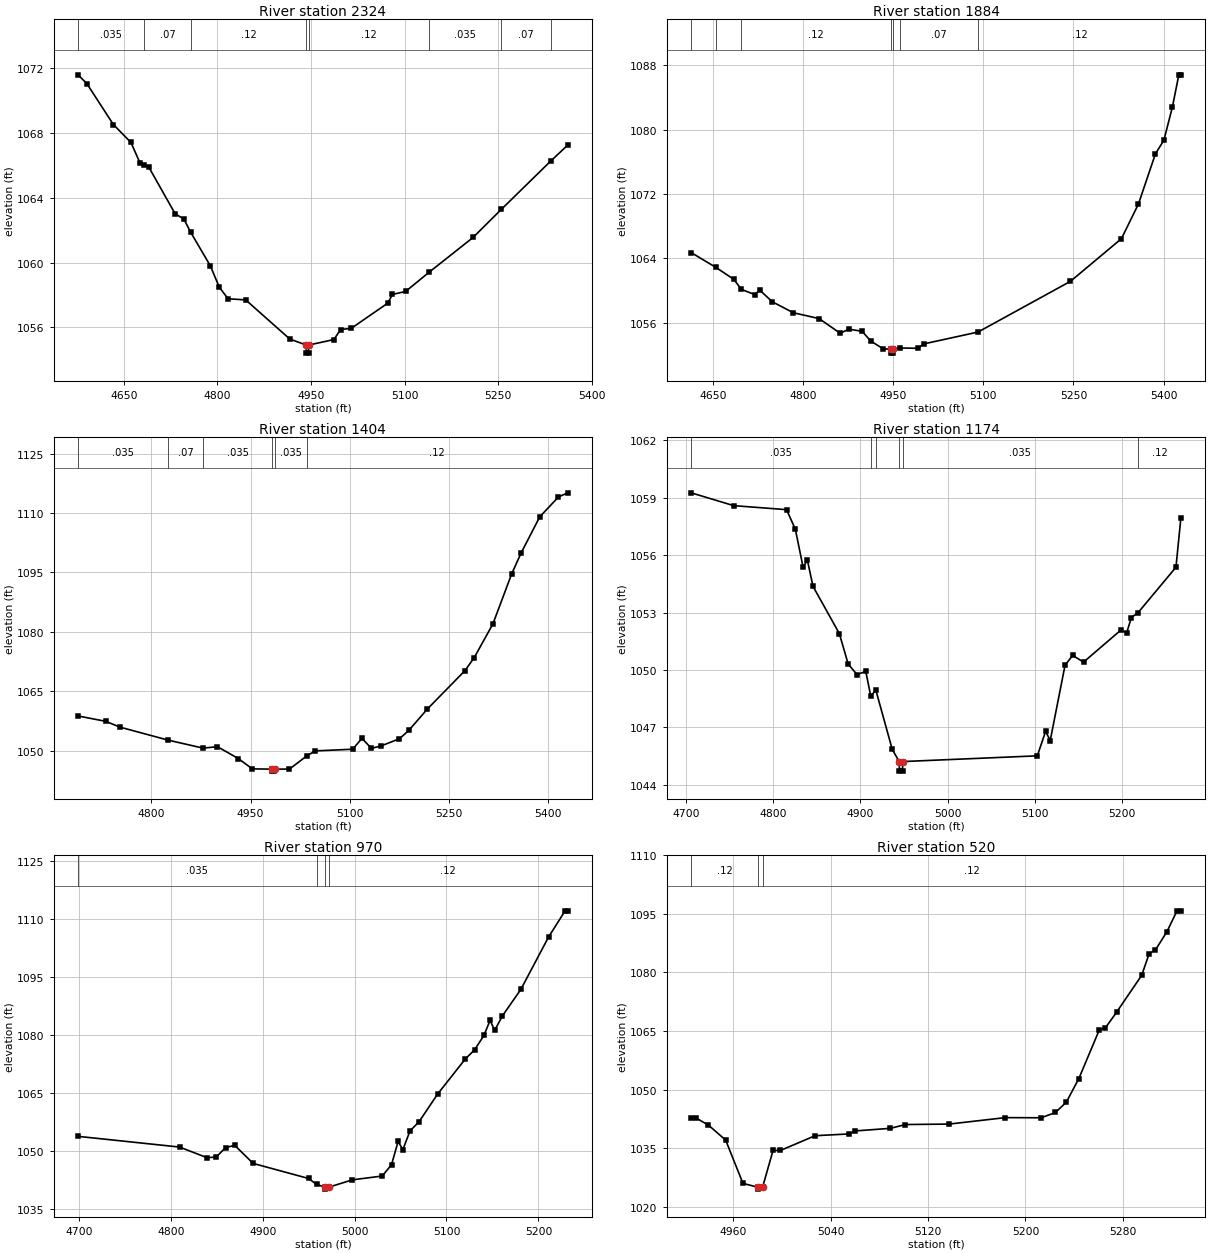
Type RM Length L Ch R = 1,2324,440,440,440
BEGIN DESCRIPTION:
Stream0259_DS 5.0
END DESCRIPTION:
XS GIS Cut Line= 3
      2135275.01     13864474.99      2135575.00     13864175.00
      2135775.00     13863875.00
#Sta/Elev= 30
  4576.5 1071.60  4590.6 1071.06  4633.1 1068.53  4661.3 1067.42  4675.5 1066.18
  4683.0 1066.04  4689.6 1065.92  4732.0 1063.02  4746.2 1062.68  4756.9 1061.88
  4788.6 1059.79  4802.8 1058.48  4816.9 1057.76  4845.2 1057.69  4915.9 1055.27
  4942.2 1054.90  4942.4 1054.40  4945.9 1054.40  4946.2 1054.90  4986.6 1055.24
  4997.2 1055.86  5014.3 1055.93  5072.9 1057.49  5080.4 1058.03  5101.4 1058.21
  5139.1 1059.40  5209.6 1061.55  5255.0 1063.29  5334.0 1066.27  5361.3 1067.26
#Mann=8,-1,0
  4576.5   0.035       0  4683.0    0.07       0  4756.9    0.12       0
  4942.2    0.05       0  4946.2    0.12       0  5139.1   0.035       0
  5255.0    0.07       0  5334.0   0.035       0
Bank Sta=4942.2,4946.2
Exp/Cntr=0.3,0.1

Type RM Length L Ch R = 1,1884,480,480,480
BEGIN DESCRIPTION:
Stream0259_DS 4.0
END DESCRIPTION:
XS GIS Cut Line= 3
      2135575.03     13864674.97      2135875.00     13864425.00
      2136174.98     13864125.02
#Sta/Elev= 30
  4614.2 1064.71  4655.1 1062.88  4685.1 1061.39  4697.7 1060.14  4720.2 1059.49
  4728.1 1060.06  4748.9 1058.61  4784.0 1057.24  4827.0 1056.51  4862.1 1054.69
  4876.5 1055.20  4898.6 1054.93  4912.9 1053.72  4933.7 1052.75  4946.0 1052.72
  4946.3 1052.22  4949.8 1052.22  4950.0 1052.72  4961.0 1052.86  4991.0 1052.82
  5001.4 1053.37  5091.4 1054.84  5245.1 1061.14  5329.9 1066.44  5358.2 1070.74
  5386.5 1076.99  5400.6 1078.68  5414.8 1082.83  5425.4 1086.80  5428.9 1086.80
#Mann=7,-1,0
  4614.2    0.12       0  4655.1    0.07       0  4697.7    0.12       0
  4946.0    0.05       0  4950.0    0.12       0  4961.0    0.07       0
  5091.4    0.12       0
Bank Sta=4946,4950
Exp/Cntr=0.3,0.1

Type RM Length L Ch R = 1,1404,230,230,230
BEGIN DESCRIPTION:
Stream0259_DS 3.0
END DESCRIPTION:
XS GIS Cut Line= 3
      2135825.05     13864874.98      2136125.00     13864775.00
      2136424.97     13864475.03
#Sta/Elev= 30
  4689.2 1058.74  4731.3 1057.38  4752.4 1055.93  4825.4 1052.64  4878.2 1050.62
  4900.0 1050.98  4931.6 1047.98  4952.7 1045.38  4982.3 1045.31  4982.5 1044.81
  4986.0 1044.81  4986.3 1045.31  5008.9 1045.33  5034.8 1048.63  5047.8 1049.92
  5104.4 1050.34  5118.5 1053.08  5132.7 1050.57  5146.8 1051.14  5175.1 1052.98
  5189.2 1055.08  5217.5 1060.52  5274.1 1070.18  5288.2 1073.48  5316.5 1082.01
  5344.8 1094.63  5358.9 1099.85  5387.2 1109.02  5415.5 1114.05  5429.6 1115.10
#Mann=6,-1,0
  4689.2   0.035       0  4825.4    0.07       0  4878.2   0.035       0
  4982.3   0.035       0  4986.3   0.035       0  5034.8    0.12       0
Bank Sta=4982.3,4986.3
Exp/Cntr=0.3,0.1

Type RM Length L Ch R = 1,1174,204,204,204
BEGIN DESCRIPTION:
Stream0259_DS 2.5
END DESCRIPTION:
XS GIS Cut Line= 3
      2135766.68     13864997.54      2136057.98     13864958.49
      2136310.35     13864870.11
#Sta/Elev= 30
  4706.1 1059.26  4754.8 1058.59  4815.4 1058.38  4825.5 1057.35  4834.3 1055.38
  4839.3 1055.73  4845.7 1054.37  4875.9 1051.90  4886.0 1050.31  4896.1 1049.76
  4906.2 1049.92  4911.9 1048.63  4917.7 1048.95  4936.5 1045.85  4944.5 1045.21
  4944.8 1044.71  4948.3 1044.71  4948.5 1045.21  5102.8 1045.51  5112.3 1046.79
  5117.6 1046.31  5134.6 1050.25  5143.3 1050.76  5155.8 1050.41  5198.2 1052.07
  5205.3 1051.95  5210.6 1052.74  5218.0 1052.98  5261.7 1055.37  5267.4 1057.97
#Mann=6,-1,0
  4706.1   0.035       0  4911.9    0.07       0  4917.7   0.035       0
  4944.5   0.035       0  4948.5   0.035       0  5218.0    0.12       0
Bank Sta=4944.5,4948.5
Exp/Cntr=0.3,0.1

Type RM Length L Ch R = 1,970,450,450,450
BEGIN DESCRIPTION:
Stream0259_DS 2.0
END DESCRIPTION:
XS GIS Cut Line= 3
      2135774.85     13865105.92      2136075.00     13865125.00
      2136305.77     13865101.68
#Sta/Elev= 30
  4699.2 1053.69  4809.6 1050.92  4839.6 1048.16  4849.7 1048.37  4859.7 1050.80
  4869.7 1051.35  4889.7 1046.68  4949.9 1042.79  4958.8 1041.23  4967.9 1040.53
  4968.1 1040.03  4971.9 1040.53  4997.5 1042.43  5030.1 1043.42  5040.2 1046.35
  5047.4 1052.39  5052.5 1050.22  5060.3 1055.08  5070.3 1057.52  5090.4 1064.66
  5120.6 1073.75  5130.6 1076.10  5140.7 1079.80  5147.4 1083.72  5152.4 1081.12
  5160.8 1084.86  5180.9 1091.73  5211.0 1105.27  5229.0 1112.06  5231.9 1112.06
#Mann=4,-1,0
  4699.2   0.035       0  4958.8    0.12       0  4967.9    0.05       0
  4971.9    0.12       0
Bank Sta=4967.9,4971.9
Exp/Cntr=0.3,0.1

Type RM Length L Ch R = 1,520,415,415,415
BEGIN DESCRIPTION:
Stream0259_DS 1.0
END DESCRIPTION:
XS GIS Cut Line= 3
      2135724.97     13865324.97      2135775.00     13865375.00
      2136096.25     13865456.16
#Sta/Elev= 30
  4925.6 1042.85  4929.2 1042.85  4939.8 1040.95  4953.9 1037.12  4968.1 1026.06
  4980.2 1025.09  4980.5 1024.59  4984.2 1025.09  4992.8 1034.48  4998.9 1034.48
  5027.3 1038.25  5055.3 1038.71  5060.5 1039.48  5089.2 1040.14  5101.5 1041.11
  5137.4 1041.23  5183.6 1042.88  5213.0 1042.84  5224.7 1044.20  5233.6 1046.83
  5243.9 1052.88  5260.6 1065.26  5265.7 1065.85  5274.8 1069.81  5295.5 1079.28
  5301.6 1084.82  5306.8 1085.78  5316.1 1090.38  5324.5 1095.77  5327.7 1095.77
#Mann=3,-1,0
  4925.6    0.12       0  4980.2    0.05       0  4984.2    0.12       0
Bank Sta=4980.2,4984.2
Exp/Cntr=0.3,0.1

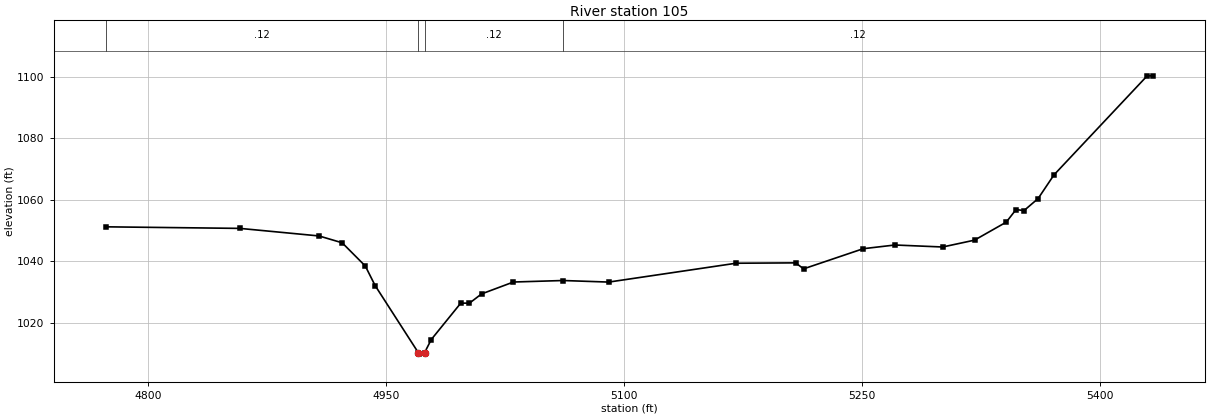
Type RM Length L Ch R = 1,105,0,0,0
BEGIN DESCRIPTION:
Stream0259_DS 0.0
END DESCRIPTION:
XS GIS Cut Line= 3
      2135528.36     13865503.62      2135664.80     13865684.67
      2136097.35     13865716.20
#Sta/Elev= 30
  4773.3 1051.19  4857.8 1050.68  4907.7 1048.22  4922.3 1045.99  4936.9 1038.42
  4943.1 1032.05  4970.3 1010.22  4970.5 1009.72  4974.3 1010.22  4978.5 1014.48
  4997.1 1026.33  5002.6 1026.33  5010.2 1029.33  5030.3 1033.21  5061.6 1033.70
  5090.4 1033.19  5170.7 1039.33  5208.3 1039.45  5213.3 1037.50  5250.9 1044.06
  5270.9 1045.27  5301.0 1044.62  5321.1 1046.85  5341.1 1052.71  5347.3 1056.82
  5352.3 1056.47  5361.2 1060.40  5371.2 1068.10  5430.0 1100.38  5433.7 1100.38
#Mann=4,-1,0
  4773.3    0.12       0  4970.3    0.05       0  4974.3    0.12       0
  5061.6    0.12       0
Bank Sta=4970.3,4974.3
Exp/Cntr=0.3,0.1

Chan Stop Cuts=-1