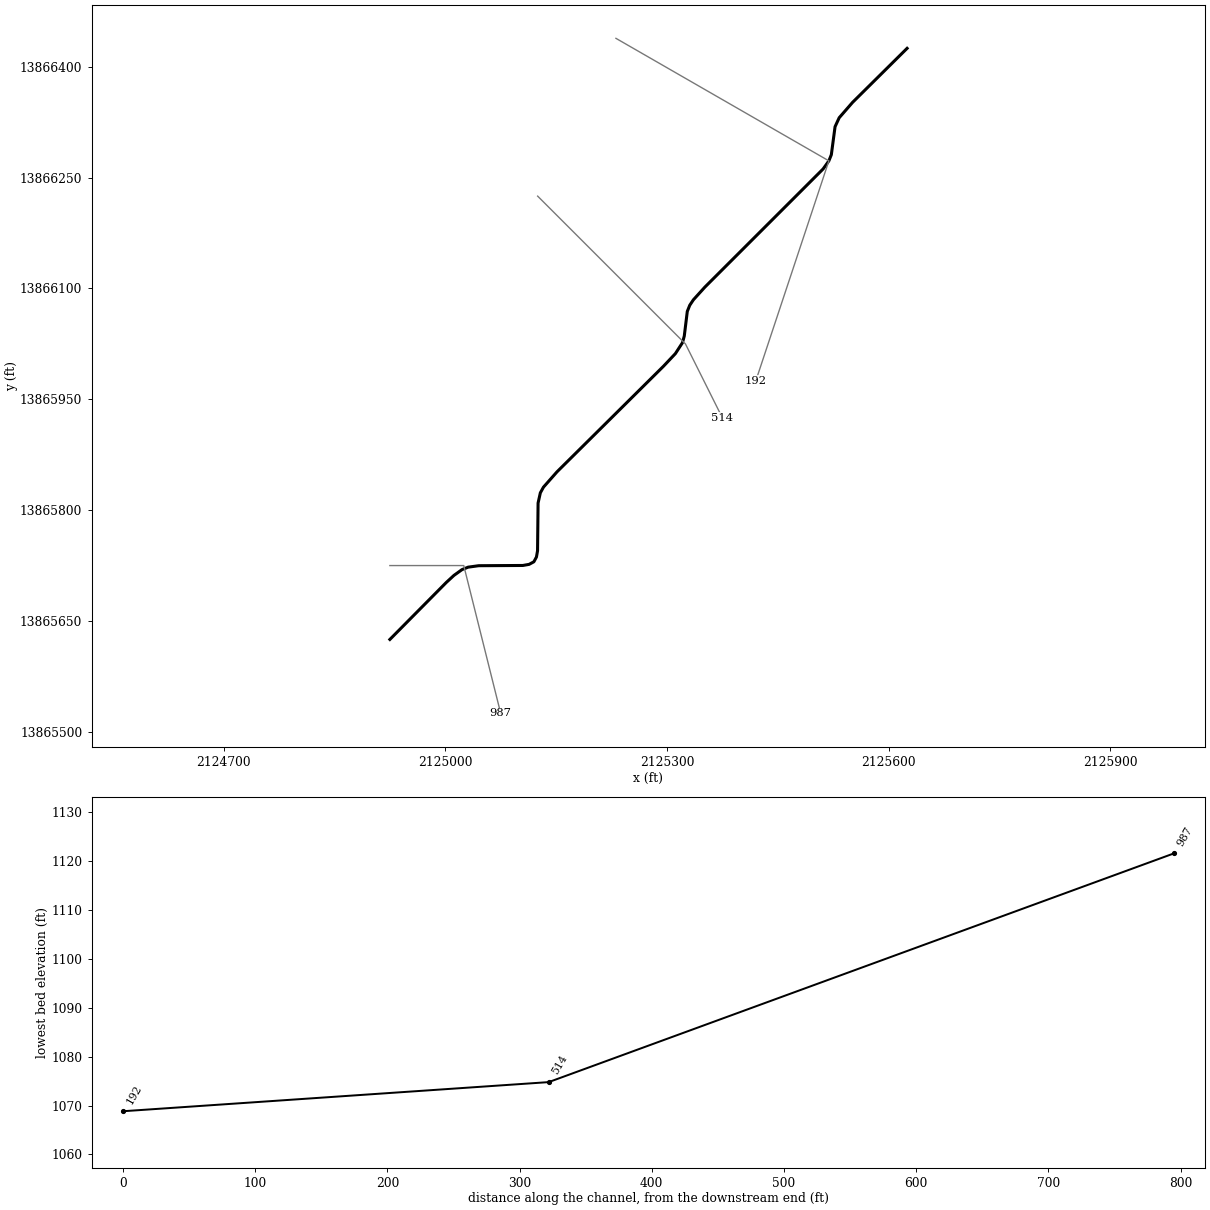
--- Stream0263_DS.prj (project) ---

Proj Title=Stream0263_DS Base Level Engineering
Current Plan=p01
Default Exp/Contr=0.3,0.1
English Units
Geom File=g01
Flow File=f01
Plan File=p01
BEGIN DESCRIPTION:
Stream0263_DS
END DESCRIPTION:

--- Stream0263_DS.p01 (plan) ---

Plan Title=Multiple Run
Short Identifier=Multiple
Geom File=g01
Flow File=f01
Subcritical Flow
K Sum by GR= 0
Std Step Tol= 0.01
Critical Tol= 0.01
Num of Std Step Trials= 20
Max Error Tol= 0.3
Flow Tol Ratio= 0.001
Split Flow NTrial= 30
Split Flow Tol= 0.02
Split Flow Ratio= 0.02
Log Output Level= 0
Friction Slope Method= 1
Unsteady Friction Slope Method= 2
Unsteady Bridges Friction Slope Method= 1
Parabolic Critical Depth
Global Vel Dist=  1 , 1 , 1
Global Log Level= 0
CheckData=True
Encroach Param= -1, 0, 0, 0
BEGIN DESCRIPTION:
Multiple Run
END DESCRIPTION:

--- Stream0263_DS.f01 (steady flow) ---

Flow Title=Multiple
Number of Profiles=7
Profile Names=10-year,25-year,50-year,1pct_min,100-year,1pct_plu,500-year
River Rch & RM= Stream0263_DS,Reach-1,987
     260     401     523     334     666    1328    1059
Boundary for River Rch & Prof#=Stream0263_DS,Reach-1,1
Up Type=0
Dn Type=3
Dn Slope=0.005
Boundary for River Rch & Prof#=Stream0263_DS,Reach-1,2
Up Type=0
Dn Type=3
Dn Slope=0.005
Boundary for River Rch & Prof#=Stream0263_DS,Reach-1,3
Up Type=0
Dn Type=3
Dn Slope=0.005
Boundary for River Rch & Prof#=Stream0263_DS,Reach-1,4
Up Type=0
Dn Type=3
Dn Slope=0.005
Boundary for River Rch & Prof#=Stream0263_DS,Reach-1,5
Up Type=0
Dn Type=3
Dn Slope=0.005
Boundary for River Rch & Prof#=Stream0263_DS,Reach-1,6
Up Type=0
Dn Type=3
Dn Slope=0.005
Boundary for River Rch & Prof#=Stream0263_DS,Reach-1,7
Up Type=0
Dn Type=3
Dn Slope=0.005

--- Stream0263_DS.g01 (geometry) ---

Geom Title=Existing Conditions

River Reach=Stream0263_DS,Reach-1
Reach XY= 30
      2124925.00     13865625.00      2125001.45     13865702.22
      2125011.70     13865711.67      2125022.62     13865719.51
      2125030.98     13865722.84      2125045.23     13865724.80
      2125104.96     13865725.12      2125113.42     13865726.62
      2125119.89     13865730.11      2125123.38     13865736.58
      2125124.87     13865745.04      2125125.59     13865809.64
      2125128.65     13865823.42      2125132.88     13865831.12
      2125151.19     13865851.85      2125295.38     13865994.84
      2125311.37     13866011.79      2125321.02     13866026.65
      2125323.45     13866035.64      2125327.53     13866068.95
      2125330.86     13866077.29      2125335.78     13866084.68
      2125351.30     13866101.82      2125511.37     13866261.79
      2125519.15     13866272.71      2125522.48     13866281.04
      2125527.52     13866318.96      2125533.11     13866331.07
      2125551.20     13866351.86      2125625.00     13866425.00

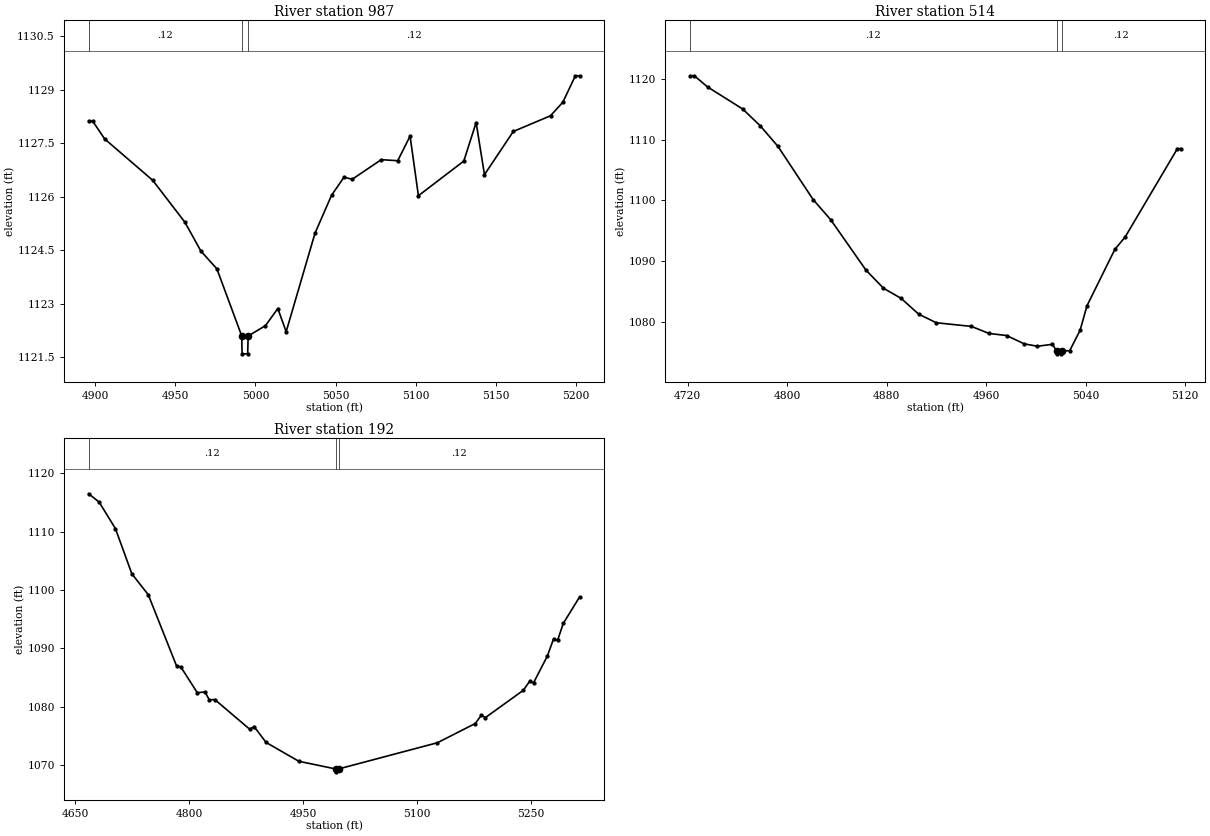
Type RM Length L Ch R = 1,987,473,473,473
BEGIN DESCRIPTION:
Stream0263_DS 2.0
END DESCRIPTION:
XS GIS Cut Line= 3
      2124925.00     13865725.00      2125025.00     13865725.00
      2125075.01     13865524.95
#Sta/Elev= 30
  4896.0 1128.12  4898.5 1128.12  4906.0 1127.62  4936.0 1126.46  4956.0 1125.29
  4966.0 1124.48  4976.0 1123.98  4991.5 1122.10  4991.7 1121.60  4995.2 1121.60
  4995.5 1122.10  5006.3 1122.39  5014.0 1122.87  5019.2 1122.22  5037.2 1124.98
  5047.5 1126.04  5055.3 1126.55  5060.4 1126.49  5078.5 1127.04  5088.8 1127.01
  5096.5 1127.70  5101.7 1126.03  5130.0 1127.00  5137.7 1128.08  5142.9 1126.62
  5160.9 1127.83  5184.1 1128.27  5191.8 1128.65  5199.6 1129.39  5202.2 1129.39
#Mann=3,-1,0
  4896.0    0.12       0  4991.5    0.05       0  4995.5    0.12       0
Bank Sta=4991.5,4995.5
Exp/Cntr=0.3,0.1

Type RM Length L Ch R = 1,514,322,322,322
BEGIN DESCRIPTION:
Stream0263_DS 1.0
END DESCRIPTION:
XS GIS Cut Line= 3
      2125125.02     13866224.98      2125325.00     13866025.00
      2125374.99     13865925.01
#Sta/Elev= 30
  4722.0 1120.50  4725.5 1120.50  4736.1 1118.67  4764.4 1115.03  4778.5 1112.27
  4792.7 1108.90  4821.0 1100.15  4835.1 1096.84  4863.4 1088.57  4877.5 1085.58
  4891.7 1083.91  4905.8 1081.32  4920.0 1079.90  4948.2 1079.30  4962.4 1078.14
  4976.5 1077.80  4990.7 1076.43  5001.3 1076.04  5013.2 1076.35  5016.8 1075.29
  5017.0 1074.79  5020.5 1074.79  5020.8 1075.29  5027.2 1075.29  5035.6 1078.66
  5041.1 1082.68  5063.5 1091.95  5071.9 1094.03  5113.8 1108.52  5116.6 1108.52
#Mann=3,-1,0
  4722.0    0.12       0  5016.8    0.05       0  5020.8    0.12       0
Bank Sta=5016.8,5020.8
Exp/Cntr=0.3,0.1

Type RM Length L Ch R = 1,192,0,0,0
BEGIN DESCRIPTION:
Stream0263_DS 0.0
END DESCRIPTION:
XS GIS Cut Line= 3
      2125230.96     13866438.54      2125519.15     13866272.71
      2125420.17     13865974.72
#Sta/Elev= 30
  4667.5 1116.52  4681.3 1115.10  4702.8 1110.54  4724.4 1102.79  4746.0 1099.21
  4783.3 1086.99  4789.1 1086.78  4810.6 1082.40  4820.7 1082.53  4826.4 1081.18
  4833.7 1081.22  4879.6 1076.14  4885.4 1076.59  4901.2 1073.87  4944.3 1070.64
  4992.7 1069.33  4993.0 1068.83  4996.7 1069.33  5126.8 1073.82  5176.7 1077.12
  5184.8 1078.56  5190.1 1078.14  5239.9 1082.81  5248.2 1084.34  5253.4 1084.08
  5271.6 1088.69  5279.8 1091.63  5285.1 1091.38  5292.6 1094.29  5314.0 1098.81
#Mann=3,-1,0
  4667.5    0.12       0  4992.7    0.05       0  4996.7    0.12       0
Bank Sta=4992.7,4996.7
Exp/Cntr=0.3,0.1

Chan Stop Cuts=-1