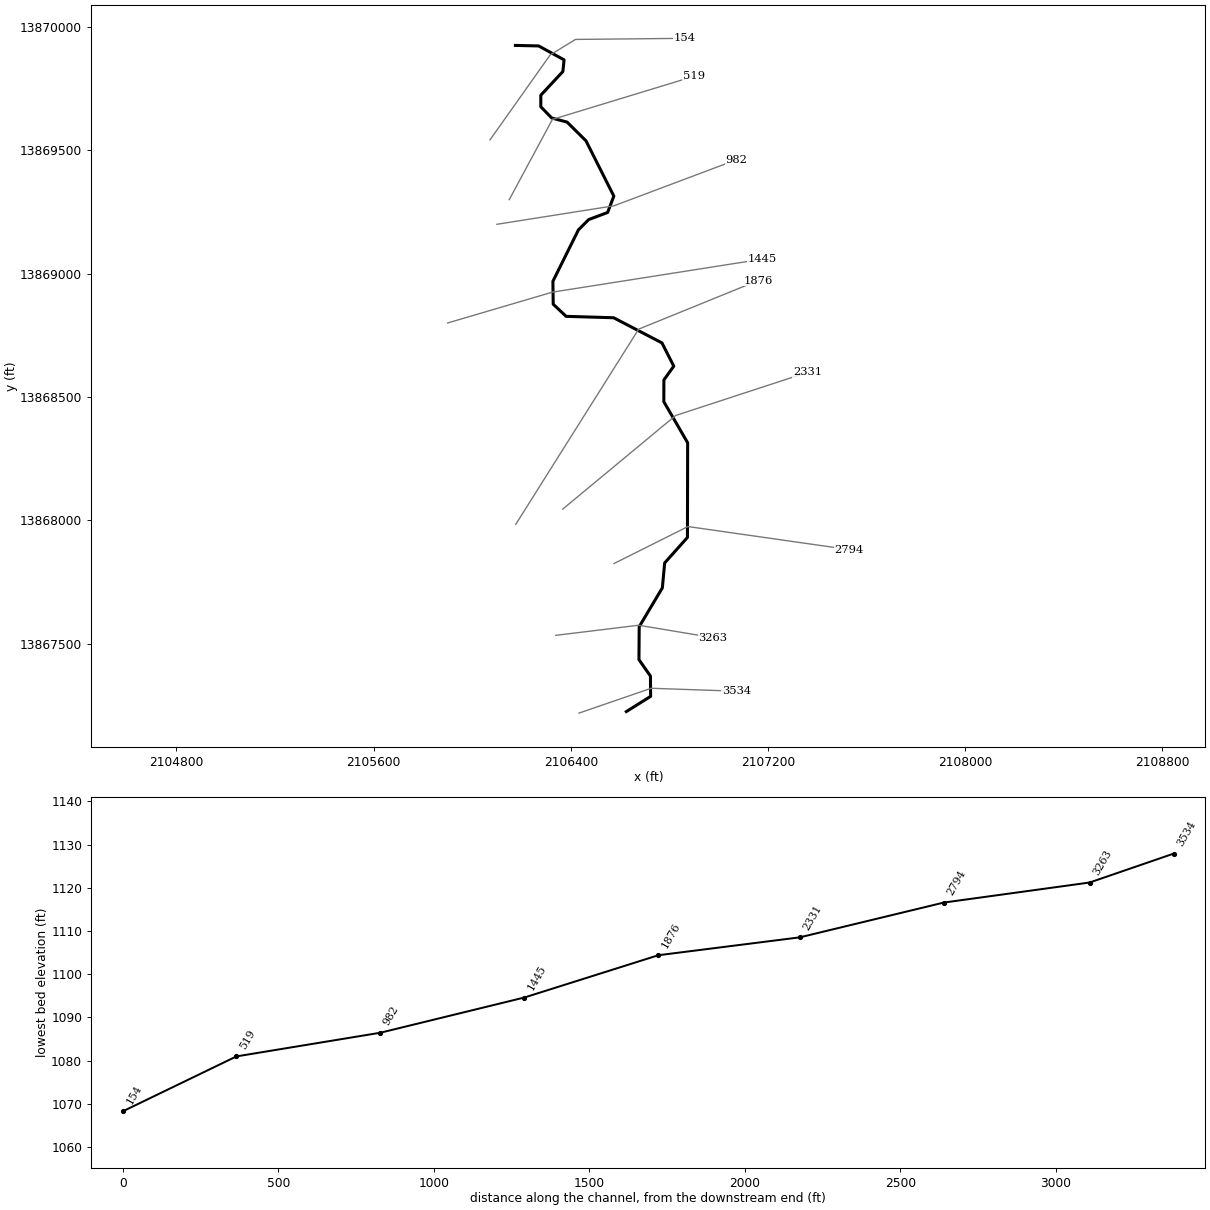
--- Stream0264_DS.prj (project) ---

Proj Title=Stream0264_DS Base Level Engineering
Current Plan=p01
Default Exp/Contr=0.3,0.1
English Units
Geom File=g01
Flow File=f01
Plan File=p01
BEGIN DESCRIPTION:
Stream0264_DS
END DESCRIPTION:

--- Stream0264_DS.p01 (plan) ---

Plan Title=Multiple Run
Short Identifier=Multiple
Geom File=g01
Flow File=f01
Subcritical Flow
K Sum by GR= 0
Std Step Tol= 0.01
Critical Tol= 0.01
Num of Std Step Trials= 20
Max Error Tol= 0.3
Flow Tol Ratio= 0.001
Split Flow NTrial= 30
Split Flow Tol= 0.02
Split Flow Ratio= 0.02
Log Output Level= 0
Friction Slope Method= 1
Unsteady Friction Slope Method= 2
Unsteady Bridges Friction Slope Method= 1
Parabolic Critical Depth
Global Vel Dist=  1 , 1 , 1
Global Log Level= 0
CheckData=True
Encroach Param= -1, 0, 0, 0
BEGIN DESCRIPTION:
Multiple Run
END DESCRIPTION:

--- Stream0264_DS.f01 (steady flow) ---

Flow Title=Multiple
Number of Profiles=7
Profile Names=10-year,25-year,50-year,1pct_min,100-year,1pct_plu,500-year
River Rch & RM= Stream0264_DS,Reach-1,3534
     235     357     461     291     581    1160     907
River Rch & RM= Stream0264_DS,Reach-1,2794
     830    1380    1895    1263    2521    5029    4404
Boundary for River Rch & Prof#=Stream0264_DS,Reach-1,1
Up Type=0
Dn Type=3
Dn Slope=0.005
Boundary for River Rch & Prof#=Stream0264_DS,Reach-1,2
Up Type=0
Dn Type=3
Dn Slope=0.005
Boundary for River Rch & Prof#=Stream0264_DS,Reach-1,3
Up Type=0
Dn Type=3
Dn Slope=0.005
Boundary for River Rch & Prof#=Stream0264_DS,Reach-1,4
Up Type=0
Dn Type=3
Dn Slope=0.005
Boundary for River Rch & Prof#=Stream0264_DS,Reach-1,5
Up Type=0
Dn Type=3
Dn Slope=0.005
Boundary for River Rch & Prof#=Stream0264_DS,Reach-1,6
Up Type=0
Dn Type=3
Dn Slope=0.005
Boundary for River Rch & Prof#=Stream0264_DS,Reach-1,7
Up Type=0
Dn Type=3
Dn Slope=0.005

--- Stream0264_DS.g01 (geometry) ---

Geom Title=Existing Conditions

River Reach=Stream0264_DS,Reach-1
Reach XY= 30
      2106625.00     13867225.00      2106723.58     13867286.76
      2106722.87     13867368.94      2106676.21     13867435.51
      2106677.23     13867569.07      2106771.17     13867726.59
      2106780.54     13867827.42      2106872.93     13867930.86
      2106873.80     13868314.50      2106777.15     13868480.97
      2106777.37     13868569.11      2106817.48     13868625.04
      2106769.45     13868719.41      2106573.45     13868821.25
      2106380.64     13868826.97      2106328.36     13868876.25
      2106327.14     13868969.03      2106430.73     13869177.55
      2106472.49     13869219.24      2106549.09     13869247.86
      2106574.32     13869314.25      2106461.39     13869538.24
      2106384.68     13869614.22      2106322.39     13869630.75
      2106278.01     13869676.43      2106278.10     13869723.32
      2106367.64     13869819.26      2106372.42     13869866.53
      2106269.17     13869922.94      2106175.00     13869925.00

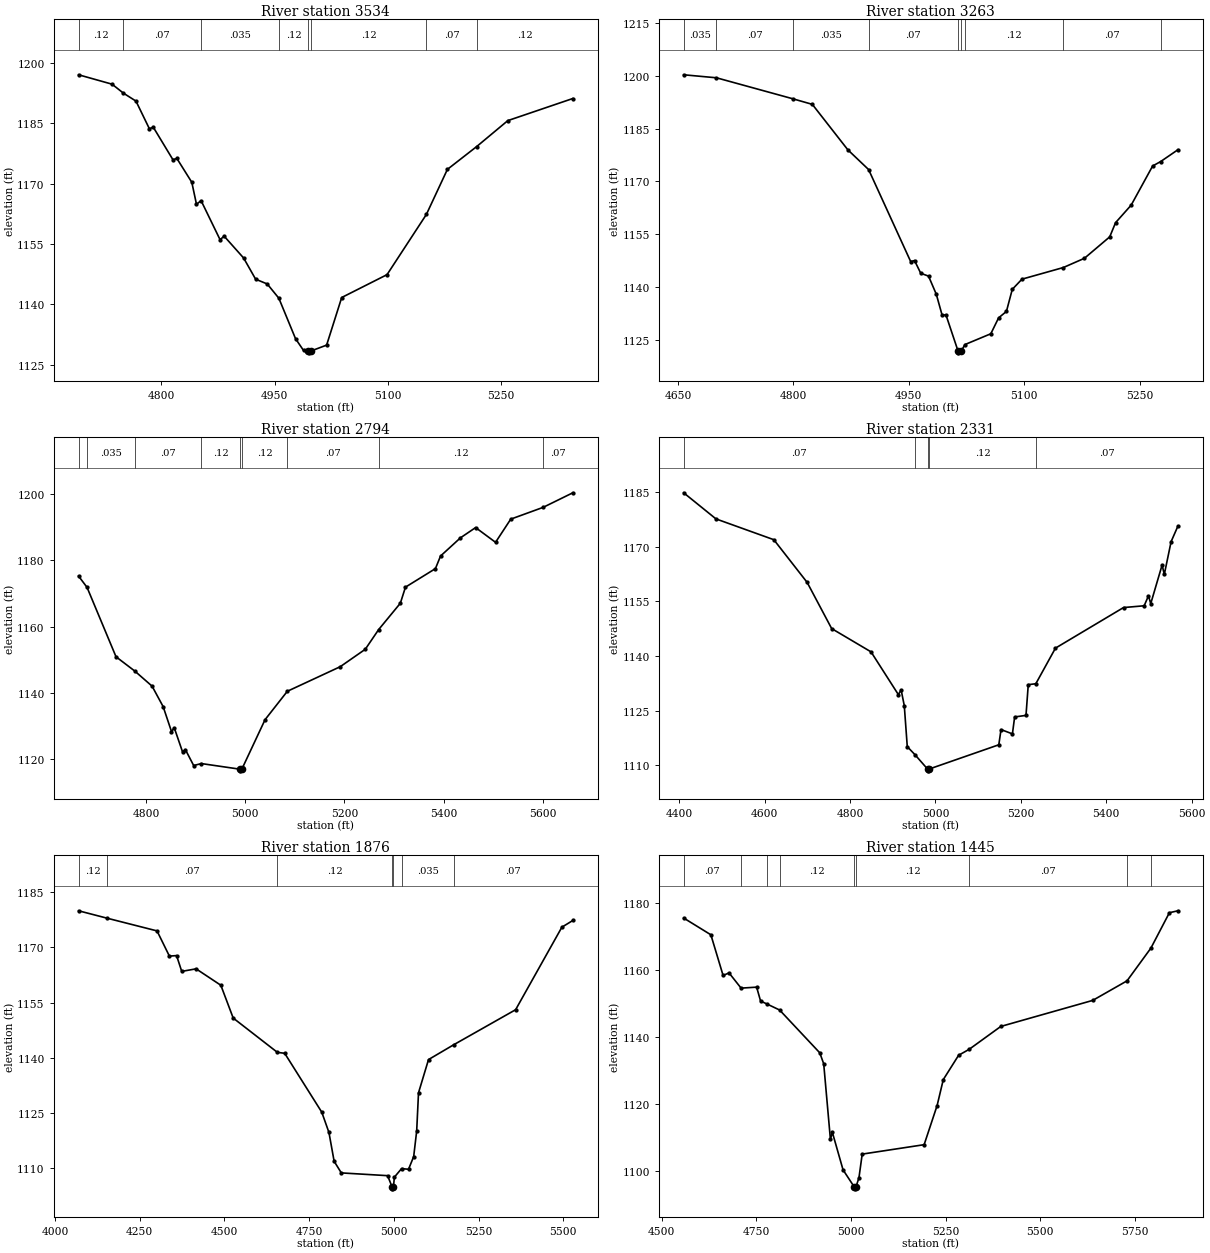
Type RM Length L Ch R = 1,3534,271,271,271
BEGIN DESCRIPTION:
Stream0264_DS 8.0
END DESCRIPTION:
XS GIS Cut Line= 3
      2106433.01     13867218.93      2106726.01     13867319.57
      2107071.20     13867307.56
#Sta/Elev= 30
  4690.2 1197.09  4734.6 1194.75  4749.5 1192.54  4766.3 1190.54  4784.0 1183.69
  4789.3 1184.03  4815.3 1175.96  4820.5 1176.28  4840.3 1170.35  4846.5 1164.88
  4852.6 1165.79  4877.8 1156.06  4883.1 1156.96  4909.0 1151.51  4924.9 1146.25
  4940.3 1145.06  4955.7 1141.51  4977.8 1131.45  4988.4 1128.52  4994.8 1128.43
  4995.1 1127.93  4998.8 1128.43  5019.0 1129.85  5039.0 1141.69  5099.1 1147.38
  5151.2 1162.34  5179.1 1173.56  5218.0 1179.25  5259.2 1185.69  5345.4 1191.19
#Mann=8,-1,0
  4690.2    0.12       0  4749.5    0.07       0  4852.6   0.035       0
  4955.7    0.12       0  4994.8    0.05       0  4998.8    0.12       0
  5151.2    0.07       0  5218.0    0.12       0
Bank Sta=4994.8,4998.8
Exp/Cntr=0.3,0.1

Type RM Length L Ch R = 1,3263,469,469,469
BEGIN DESCRIPTION:
Stream0264_DS 7.0
END DESCRIPTION:
XS GIS Cut Line= 3
      2106338.91     13867534.09      2106675.00     13867575.00
      2106974.99     13867525.00
#Sta/Elev= 30
  4657.2 1200.36  4699.9 1199.50  4798.8 1193.55  4824.5 1191.94  4870.7 1179.00
  4897.7 1173.38  4952.4 1147.19  4957.4 1147.49  4965.5 1143.86  4975.6 1143.06
  4985.7 1137.90  4993.2 1132.00  4998.3 1132.00  5014.0 1121.72  5014.3 1121.22
  5018.0 1121.72  5023.0 1123.58  5056.6 1126.65  5066.7 1131.17  5076.9 1133.01
  5084.5 1139.29  5097.1 1142.19  5150.9 1145.50  5178.3 1148.13  5211.2 1154.23
  5218.8 1158.27  5239.1 1163.26  5267.0 1174.40  5277.5 1175.67  5299.9 1179.03
#Mann=9,-1,0
  4657.2   0.035       0  4699.9    0.07       0  4798.8   0.035       0
  4897.7    0.07       0  5014.0    0.05       0  5018.0    0.07       0
  5023.0    0.12       0  5150.9    0.07       0  5277.5    0.12       0
Bank Sta=5014,5018
Exp/Cntr=0.3,0.1

Type RM Length L Ch R = 1,2794,463,463,463
BEGIN DESCRIPTION:
Stream0264_DS 6.0
END DESCRIPTION:
XS GIS Cut Line= 3
      2106574.96     13867824.98      2106875.00     13867975.00
      2107529.22     13867881.63
#Sta/Elev= 30
  4664.1 1175.23  4681.2 1171.83  4739.6 1150.93  4777.5 1146.62  4812.3 1142.08
  4834.6 1135.91  4851.4 1128.42  4857.0 1129.54  4873.8 1122.23  4879.4 1122.98
  4896.1 1118.18  4911.6 1118.77  4989.2 1117.08  4989.4 1116.58  4993.2 1117.08
  5040.0 1131.99  5084.9 1140.54  5191.5 1147.94  5242.0 1153.19  5269.0 1159.13
  5312.7 1167.06  5323.0 1171.90  5383.4 1177.48  5393.7 1181.27  5433.9 1186.76
  5464.4 1189.84  5504.6 1185.40  5535.2 1192.38  5600.5 1195.93  5660.4 1200.32
#Mann=9,-1,0
  4664.1    0.07       0  4681.2   0.035       0  4777.5    0.07       0
  4911.6    0.12       0  4989.2    0.05       0  4993.2    0.12       0
  5084.9    0.07       0  5269.0    0.12       0  5600.5    0.07       0
Bank Sta=4989.2,4993.2
Exp/Cntr=0.3,0.1

Type RM Length L Ch R = 1,2331,455,455,455
BEGIN DESCRIPTION:
Stream0264_DS 5.0
END DESCRIPTION:
XS GIS Cut Line= 3
      2106366.99     13868045.60      2106825.00     13868425.00
      2107360.19     13868599.94
#Sta/Elev= 30
  4410.1 1184.74  4485.8 1177.58  4621.3 1171.88  4699.4 1160.17  4756.8 1147.52
  4849.0 1141.14  4913.0 1129.43  4919.5 1130.71  4926.9 1126.41  4933.9 1115.16
  4951.9 1112.96  4981.3 1109.03  4981.6 1108.53  4985.3 1109.03  5148.3 1115.67
  5153.5 1119.84  5180.2 1118.66  5185.4 1123.30  5212.0 1123.73  5217.3 1132.15
  5235.0 1132.40  5281.0 1142.16  5440.4 1153.28  5488.8 1153.77  5498.9 1156.50
  5504.2 1154.36  5530.8 1164.93  5536.0 1162.39  5551.9 1171.35  5567.9 1175.62
#Mann=5,-1,0
  4410.1    0.07       0  4951.9    0.12       0  4981.3    0.05       0
  4985.3    0.12       0  5235.0    0.07       0
Bank Sta=4981.3,4985.3
Exp/Cntr=0.3,0.1

Type RM Length L Ch R = 1,1876,431,431,431
BEGIN DESCRIPTION:
Stream0264_DS 4.0
END DESCRIPTION:
XS GIS Cut Line= 3
      2106176.61     13867984.15      2106675.00     13868775.00
      2107160.20     13868972.09
#Sta/Elev= 30
  4069.8 1179.96  4152.9 1177.97  4301.3 1174.49  4337.8 1167.64  4359.0 1167.78
  4374.2 1163.49  4416.6 1164.18  4489.6 1159.72  4526.1 1150.80  4656.5 1141.48
  4678.0 1141.23  4787.4 1125.23  4808.6 1119.71  4823.9 1111.88  4845.1 1108.72
  4981.7 1107.97  4995.0 1104.89  4995.2 1104.39  4999.0 1104.89  5001.6 1107.56
  5022.9 1109.89  5043.4 1109.71  5058.6 1113.14  5067.5 1120.13  5072.9 1130.50
  5102.4 1139.52  5176.2 1143.52  5359.4 1153.07  5495.9 1175.50  5528.3 1177.33
#Mann=7,-1,0
  4069.8    0.12       0  4152.9    0.07       0  4656.5    0.12       0
  4995.0    0.05       0  4999.0    0.12       0  5022.9   0.035       0
  5176.2    0.07       0
Bank Sta=4995,4999
Exp/Cntr=0.3,0.1

Type RM Length L Ch R = 1,1445,463,463,463
BEGIN DESCRIPTION:
Stream0264_DS 3.0
END DESCRIPTION:
XS GIS Cut Line= 3
      2105900.02     13868800.01      2106325.00     13868925.00
      2107177.36     13869058.93
#Sta/Elev= 30
  4557.9 1175.38  4629.8 1170.38  4662.1 1158.25  4677.8 1159.01  4709.6 1154.47
  4750.7 1154.76  4761.1 1150.63  4779.4 1149.66  4811.4 1147.94  4917.5 1135.17
  4927.9 1131.90  4945.6 1109.37  4950.8 1111.44  4979.0 1100.26  5009.0 1095.10
  5009.3 1094.60  5013.0 1095.10  5021.1 1097.97  5029.6 1104.96  5193.2 1107.77
  5227.5 1119.45  5243.8 1127.19  5284.3 1134.44  5312.5 1136.24  5395.7 1143.04
  5638.6 1150.81  5729.2 1156.64  5792.3 1166.41  5841.1 1176.96  5863.7 1177.54
#Mann=9,-1,0
  4557.9    0.07       0  4709.6   0.035       0  4779.4    0.07       0
  4811.4    0.12       0  5009.0    0.05       0  5013.0    0.12       0
  5312.5    0.07       0  5729.2   0.035       0  5792.3    0.07       0
Bank Sta=5009,5013
Exp/Cntr=0.3,0.1

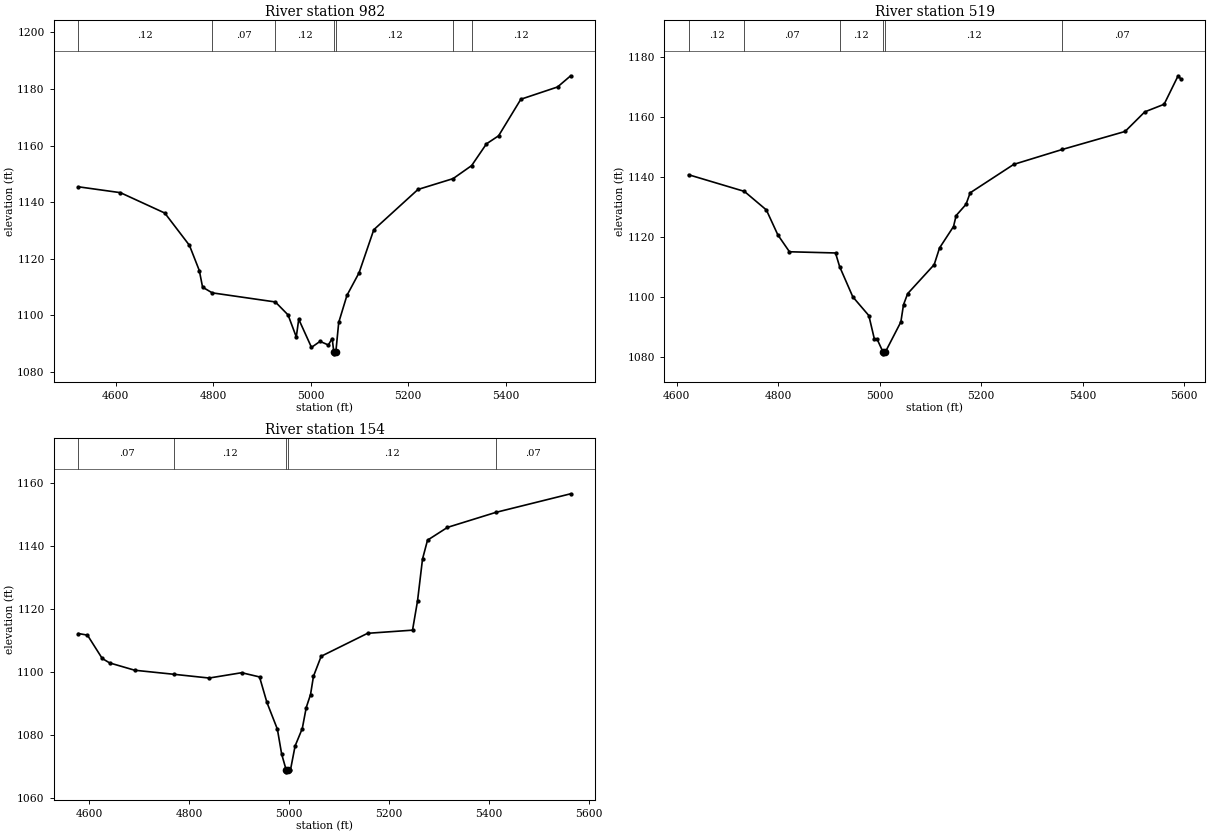
Type RM Length L Ch R = 1,982,463,463,463
BEGIN DESCRIPTION:
Stream0264_DS 2.0
END DESCRIPTION:
XS GIS Cut Line= 3
      2106099.98     13869200.00      2106575.00     13869275.00
      2107070.78     13869461.22
#Sta/Elev= 30
  4523.2 1145.47  4609.3 1143.40  4700.4 1136.20  4751.0 1124.79  4771.3 1115.88
  4778.0 1110.01  4797.8 1108.00  4927.4 1104.78  4953.5 1100.20  4970.4 1092.42
  4975.4 1098.68  5001.6 1088.73  5019.2 1090.86  5036.1 1089.58  5044.1 1091.85
  5047.5 1086.95  5047.7 1086.45  5051.5 1086.95  5057.5 1097.54  5074.4 1107.11
  5099.3 1115.10  5129.5 1130.31  5220.2 1144.53  5292.3 1148.36  5330.4 1152.97
  5360.8 1160.65  5385.7 1163.49  5431.4 1176.41  5506.7 1180.74  5533.7 1184.70
#Mann=7,-1,0
  4523.2    0.12       0  4797.8    0.07       0  4927.4    0.12       0
  5047.5    0.05       0  5051.5    0.12       0  5292.3   0.035       0
  5330.4    0.12       0
Bank Sta=5047.5,5051.5
Exp/Cntr=0.3,0.1

Type RM Length L Ch R = 1,519,365,365,365
BEGIN DESCRIPTION:
Stream0264_DS 1.0
END DESCRIPTION:
XS GIS Cut Line= 3
      2106150.00     13869300.00      2106325.00     13869625.00
      2106900.04     13869800.01
#Sta/Elev= 30
  4623.4 1140.68  4733.3 1135.13  4776.7 1128.94  4799.4 1120.60  4822.2 1115.00
  4913.0 1114.60  4921.1 1110.05  4947.1 1099.96  4978.7 1093.72  4989.7 1085.82
  4995.1 1085.82  5006.9 1081.47  5007.2 1080.97  5010.9 1081.47  5041.8 1091.60
  5047.0 1097.34  5055.2 1101.04  5107.5 1110.71  5118.0 1116.26  5145.6 1123.42
  5150.8 1127.08  5170.2 1130.80  5178.4 1134.65  5264.3 1144.13  5360.3 1149.12
  5483.8 1155.11  5522.6 1161.64  5560.7 1164.17  5588.3 1173.67  5593.6 1172.60
#Mann=6,-1,0
  4623.4    0.12       0  4733.3    0.07       0  4921.1    0.12       0
  5006.9    0.05       0  5010.9    0.12       0  5360.3    0.07       0
Bank Sta=5006.9,5010.9
Exp/Cntr=0.3,0.1

Type RM Length L Ch R = 1,154,0,0,0
BEGIN DESCRIPTION:
Stream0264_DS 0.0
END DESCRIPTION:
XS GIS Cut Line= 4
      2106071.91     13869542.10      2106315.82     13869886.22
      2106418.59     13869949.26      2106861.60     13869953.77
#Sta/Elev= 30
  4578.2 1112.12  4596.2 1111.61  4625.7 1104.23  4640.5 1102.81  4690.9 1100.48
  4770.3 1099.18  4839.8 1098.01  4905.0 1099.70  4940.7 1098.36  4955.5 1090.27
  4976.4 1081.81  4985.0 1073.89  4994.2 1068.77  4994.4 1068.27  4998.2 1068.77
  5002.5 1068.77  5011.9 1076.47  5026.3 1082.01  5034.2 1088.66  5042.8 1092.78
  5048.7 1098.58  5064.1 1104.91  5157.0 1112.19  5247.0 1113.19  5257.0 1122.45
  5267.0 1135.75  5277.0 1141.72  5317.0 1145.78  5413.7 1150.53  5563.6 1156.43
#Mann=5,-1,0
  4578.2    0.07       0  4770.3    0.12       0  4994.2    0.05       0
  4998.2    0.12       0  5413.7    0.07       0
Bank Sta=4994.2,4998.2
Exp/Cntr=0.3,0.1

Chan Stop Cuts=-1