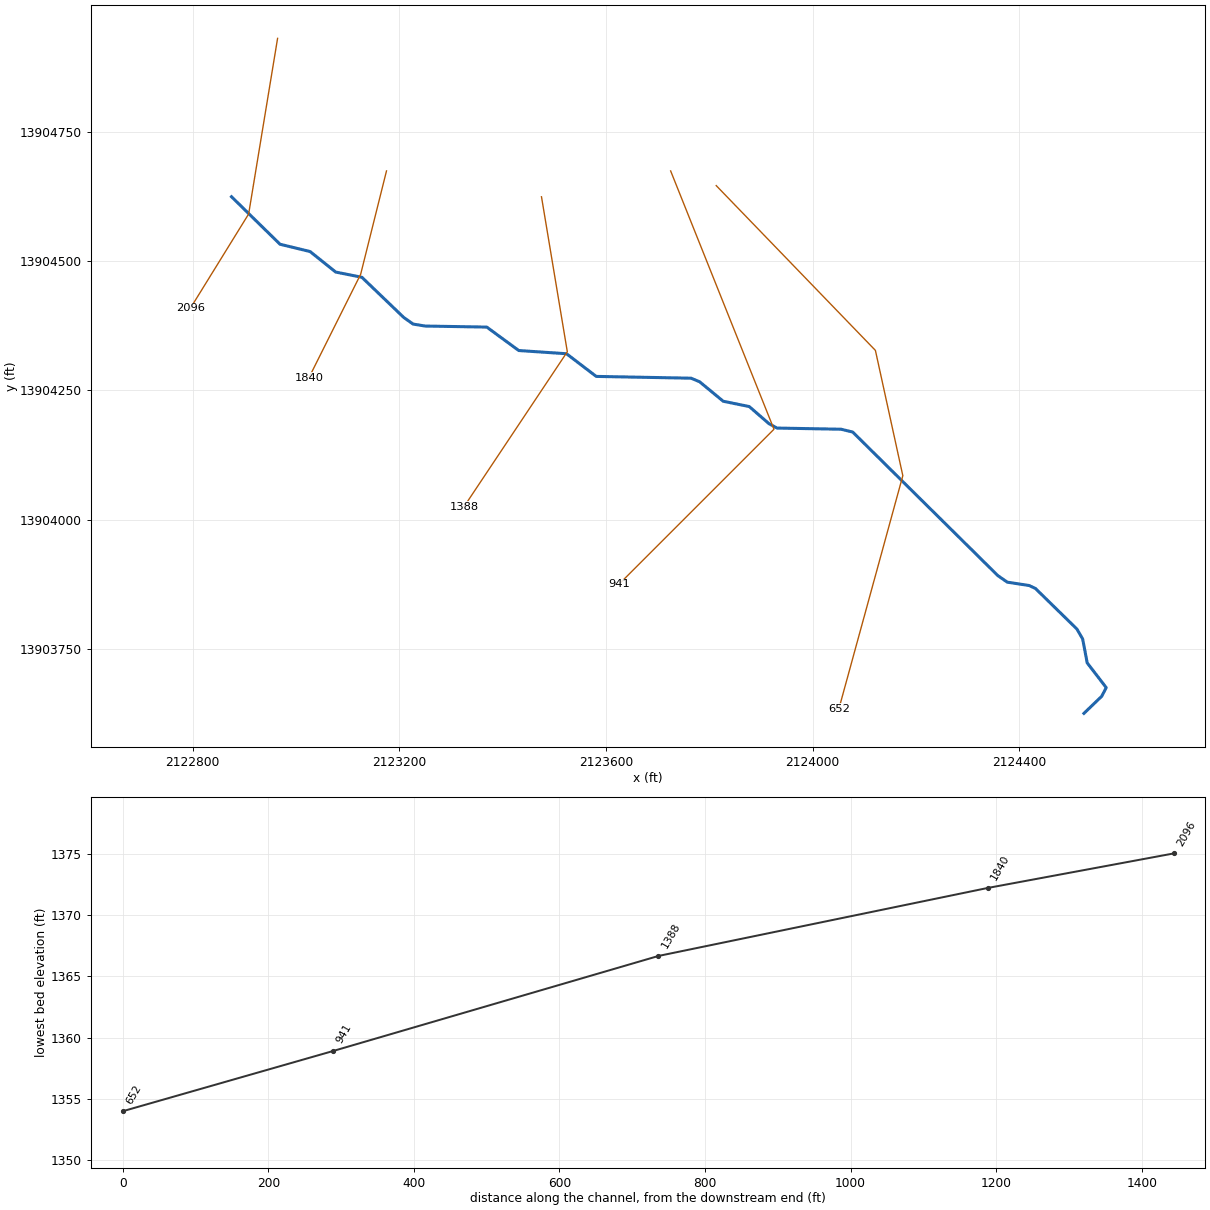
--- Stream0266_DS.prj (project) ---

Proj Title=Stream0266_DS Base Level Engineering
Current Plan=p01
Default Exp/Contr=0.3,0.1
English Units
Geom File=g01
Flow File=f01
Plan File=p01
BEGIN DESCRIPTION:
Stream0266_DS
END DESCRIPTION:

--- Stream0266_DS.p01 (plan) ---

Plan Title=Multiple Run
Short Identifier=Multiple
Geom File=g01
Flow File=f01
Subcritical Flow
K Sum by GR= 0
Std Step Tol= 0.01
Critical Tol= 0.01
Num of Std Step Trials= 20
Max Error Tol= 0.3
Flow Tol Ratio= 0.001
Split Flow NTrial= 30
Split Flow Tol= 0.02
Split Flow Ratio= 0.02
Log Output Level= 0
Friction Slope Method= 1
Unsteady Friction Slope Method= 2
Unsteady Bridges Friction Slope Method= 1
Parabolic Critical Depth
Global Vel Dist=  1 , 1 , 1
Global Log Level= 0
CheckData=True
Encroach Param= -1, 0, 0, 0
BEGIN DESCRIPTION:
Multiple Run
END DESCRIPTION:

--- Stream0266_DS.f01 (steady flow) ---

Flow Title=Multiple
Number of Profiles=7
Profile Names=10-year,25-year,50-year,1pct_min,100-year,1pct_plu,500-year
River Rch & RM= Stream0266_DS,Reach-1,2096
     449     713     948     614    1225    2443    2014
Boundary for River Rch & Prof#=Stream0266_DS,Reach-1,1
Up Type=0
Dn Type=3
Dn Slope=0.005
Boundary for River Rch & Prof#=Stream0266_DS,Reach-1,2
Up Type=0
Dn Type=3
Dn Slope=0.005
Boundary for River Rch & Prof#=Stream0266_DS,Reach-1,3
Up Type=0
Dn Type=3
Dn Slope=0.005
Boundary for River Rch & Prof#=Stream0266_DS,Reach-1,4
Up Type=0
Dn Type=3
Dn Slope=0.005
Boundary for River Rch & Prof#=Stream0266_DS,Reach-1,5
Up Type=0
Dn Type=3
Dn Slope=0.005
Boundary for River Rch & Prof#=Stream0266_DS,Reach-1,6
Up Type=0
Dn Type=3
Dn Slope=0.005
Boundary for River Rch & Prof#=Stream0266_DS,Reach-1,7
Up Type=0
Dn Type=3
Dn Slope=0.005

--- Stream0266_DS.g01 (geometry) ---

Geom Title=Existing Conditions

River Reach=Stream0266_DS,Reach-1
Reach XY= 30
      2122875.00     13904625.00      2122968.92     13904533.09
      2123027.19     13904518.91      2123076.73     13904479.19
      2123127.29     13904469.15      2123208.25     13904391.46
      2123226.47     13904378.55      2123249.89     13904374.73
      2123369.06     13904372.73      2123430.98     13904327.36
      2123523.40     13904321.14      2123580.94     13904277.26
      2123764.50     13904273.80      2123781.07     13904266.90
      2123826.74     13904229.19      2123877.18     13904218.88
      2123915.33     13904185.80      2123930.93     13904177.25
      2124055.01     13904175.02      2124077.45     13904169.53
      2124358.33     13903891.65      2124376.65     13903878.98
      2124418.96     13903872.47      2124431.07     13903866.85
      2124511.41     13903788.24      2124522.55     13903768.97
      2124531.30     13903722.70      2124568.13     13903674.88
      2124559.47     13903658.17      2124525.00     13903625.00

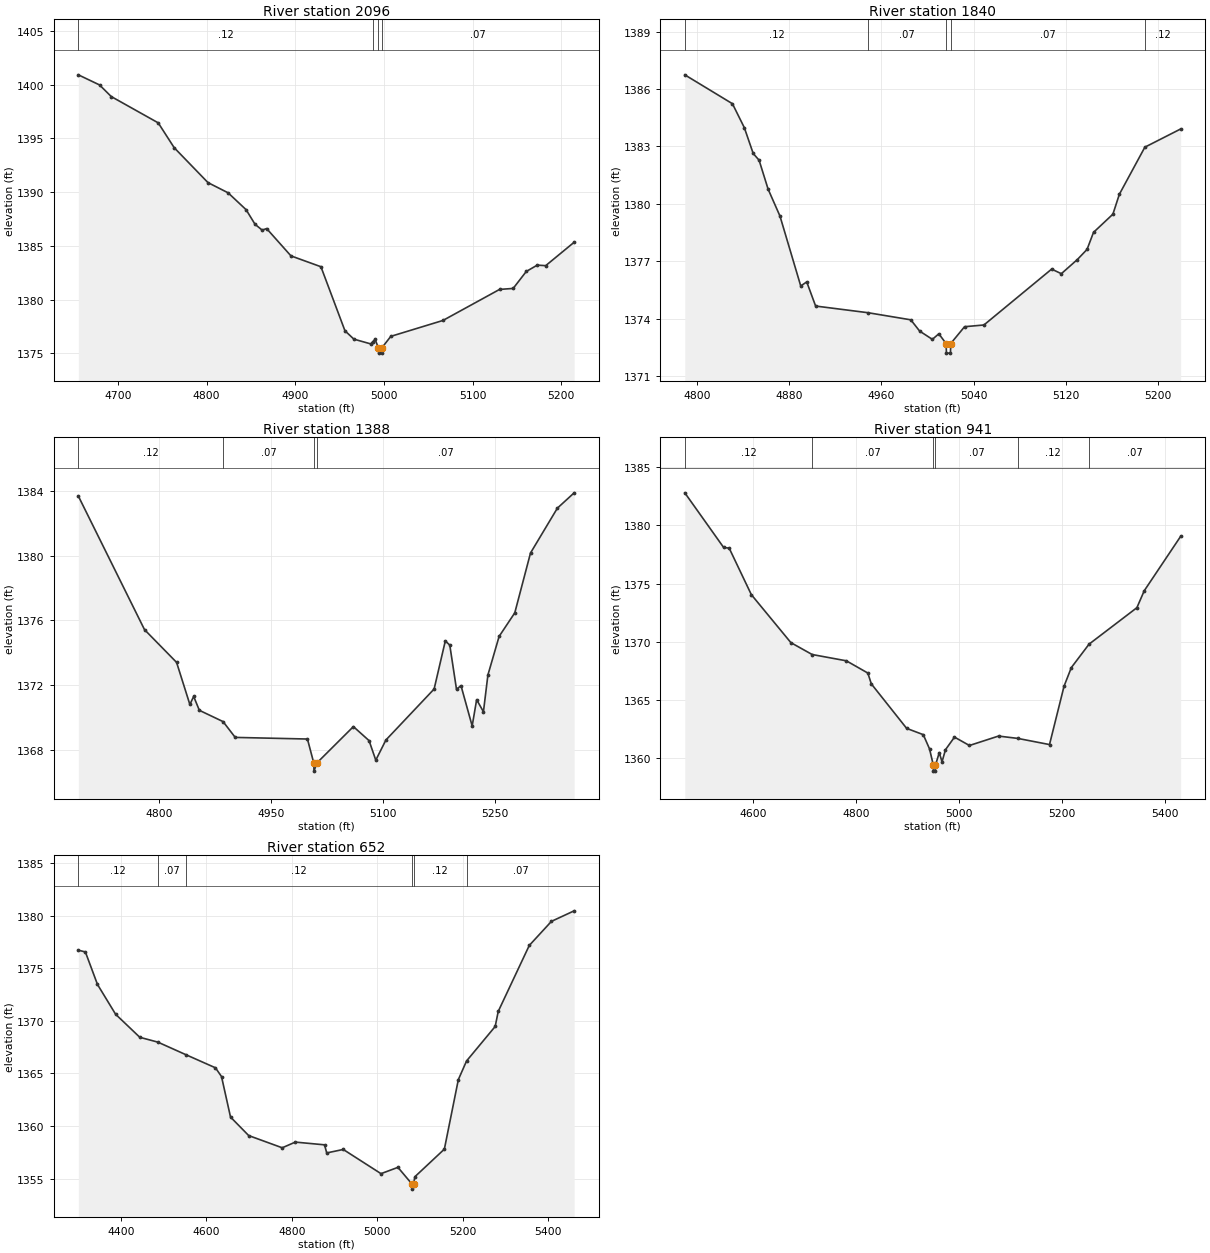
Type RM Length L Ch R = 1,2096,256,256,256
BEGIN DESCRIPTION:
Stream0266_DS 4.0
END DESCRIPTION:
XS GIS Cut Line= 3
      2122964.19     13904931.65      2122908.17     13904591.64
      2122795.35     13904409.09
#Sta/Elev= 30
  4655.4 1400.92  4679.3 1399.98  4692.5 1398.90  4745.5 1396.45  4763.5 1394.14
  4801.6 1390.89  4824.3 1389.94  4844.6 1388.37  4854.7 1387.01  4862.7 1386.47
  4867.8 1386.61  4895.2 1384.07  4929.0 1383.06  4956.1 1377.10  4966.2 1376.32
  4985.1 1375.88  4987.7 1376.10  4990.1 1376.30  4993.8 1375.52  4994.0 1375.02
  4997.5 1375.02  4997.8 1375.52  5007.8 1376.58  5066.6 1378.06  5130.5 1380.95
  5145.8 1381.04  5160.6 1382.62  5173.0 1383.21  5182.5 1383.16  5214.6 1385.34
#Mann=4,-1,0
  4655.4    0.12       0  4987.7    0.07       0  4993.8    0.05       0
  4997.8    0.07       0
Bank Sta=4993.8,4997.8
Exp/Cntr=0.3,0.1

Type RM Length L Ch R = 1,1840,452,452,452
BEGIN DESCRIPTION:
Stream0266_DS 3.0
END DESCRIPTION:
XS GIS Cut Line= 3
      2123175.01     13904675.03      2123125.00     13904475.00
      2123024.99     13904274.99
#Sta/Elev= 30
  4789.5 1386.74  4830.8 1385.23  4841.1 1383.98  4848.8 1382.63  4853.9 1382.28
  4861.7 1380.77  4872.0 1379.36  4890.0 1375.71  4895.2 1375.92  4902.9 1374.66
  4948.5 1374.31  4985.4 1373.94  4993.1 1373.35  5004.1 1372.92  5009.7 1373.21
  5016.0 1372.70  5016.3 1372.20  5019.8 1372.20  5020.0 1372.70  5032.0 1373.58
  5048.8 1373.67  5107.5 1376.59  5115.9 1376.35  5129.8 1377.09  5138.2 1377.62
  5143.8 1378.51  5160.6 1379.46  5166.2 1380.50  5188.3 1382.96  5219.3 1383.91
#Mann=5,-1,0
  4789.5    0.12       0  4948.5    0.07       0  5016.0    0.05       0
  5020.0    0.07       0  5188.3    0.12       0
Bank Sta=5016,5020
Exp/Cntr=0.3,0.1

Type RM Length L Ch R = 1,1388,447,447,447
BEGIN DESCRIPTION:
Stream0266_DS 2.0
END DESCRIPTION:
XS GIS Cut Line= 3
      2123475.01     13904624.95      2123525.00     13904325.00
      2123325.03     13904025.04
#Sta/Elev= 30
  4691.6 1383.71  4780.3 1375.43  4823.3 1373.40  4841.1 1370.79  4846.2 1371.29
  4853.8 1370.43  4885.6 1369.73  4901.9 1368.75  4998.7 1368.65  5007.2 1367.16
  5007.5 1366.66  5011.2 1367.16  5060.3 1369.42  5081.3 1368.55  5090.3 1367.34
  5103.9 1368.59  5168.5 1371.75  5183.5 1374.73  5189.5 1374.47  5198.5 1371.73
  5204.5 1371.96  5219.5 1369.46  5225.5 1371.09  5234.6 1370.34  5240.6 1372.62
  5255.6 1375.01  5276.6 1376.47  5297.7 1380.18  5333.7 1382.96  5356.2 1383.91
#Mann=4,-1,0
  4691.6    0.12       0  4885.6    0.07       0  5007.2    0.05       0
  5011.2    0.07       0
Bank Sta=5007.2,5011.2
Exp/Cntr=0.3,0.1

Type RM Length L Ch R = 1,941,289,289,289
BEGIN DESCRIPTION:
Stream0266_DS 1.0
END DESCRIPTION:
XS GIS Cut Line= 3
      2123725.00     13904675.00      2123925.00     13904175.00
      2123624.98     13903874.98
#Sta/Elev= 30
  4467.6 1382.80  4543.0 1378.11  4553.8 1378.05  4596.8 1374.06  4673.6 1369.94
  4714.9 1368.92  4781.3 1368.38  4823.0 1367.33  4829.8 1366.40  4898.4 1362.58
  4930.7 1362.04  4942.8 1360.82  4950.3 1359.41  4950.5 1358.91  4954.0 1358.91
  4954.3 1359.41  4961.7 1360.50  4967.1 1359.71  4973.8 1360.75  4991.3 1361.83
  5020.3 1361.11  5076.8 1361.92  5114.0 1361.72  5175.8 1361.19  5204.1 1366.21
  5218.2 1367.80  5252.6 1369.81  5345.5 1372.94  5359.7 1374.39  5430.4 1379.06
#Mann=6,-1,0
  4467.6    0.12       0  4714.9    0.07       0  4950.3    0.05       0
  4954.3    0.07       0  5114.0    0.12       0  5252.6    0.07       0
Bank Sta=4950.3,4954.3
Exp/Cntr=0.3,0.1

Type RM Length L Ch R = 1,652,0,0,0
BEGIN DESCRIPTION:
Stream0266_DS 0.0
END DESCRIPTION:
XS GIS Cut Line= 4
      2123813.19     13904646.63      2124121.37     13904327.58
      2124174.42     13904085.08      2124050.65     13903633.76
#Sta/Elev= 30
  4300.5 1376.71  4317.0 1376.54  4345.3 1373.45  4387.7 1370.62  4444.3 1368.43
  4486.6 1367.97  4551.9 1366.78  4621.3 1365.53  4635.4 1364.70  4656.5 1360.85
  4699.0 1359.09  4777.4 1357.93  4808.1 1358.47  4876.4 1358.21  4881.5 1357.44
  4920.2 1357.77  5008.5 1355.47  5048.1 1356.07  5080.6 1354.50  5080.8 1354.00
  5084.6 1354.50  5087.8 1355.18  5156.7 1357.80  5189.4 1364.41  5208.6 1366.18
  5275.6 1369.46  5282.7 1370.89  5355.3 1377.16  5407.2 1379.45  5460.3 1380.45
#Mann=6,-1,0
  4300.5    0.12       0  4486.6    0.07       0  4551.9    0.12       0
  5080.6    0.05       0  5084.6    0.12       0  5208.6    0.07       0
Bank Sta=5080.6,5084.6
Exp/Cntr=0.3,0.1

Chan Stop Cuts=-1