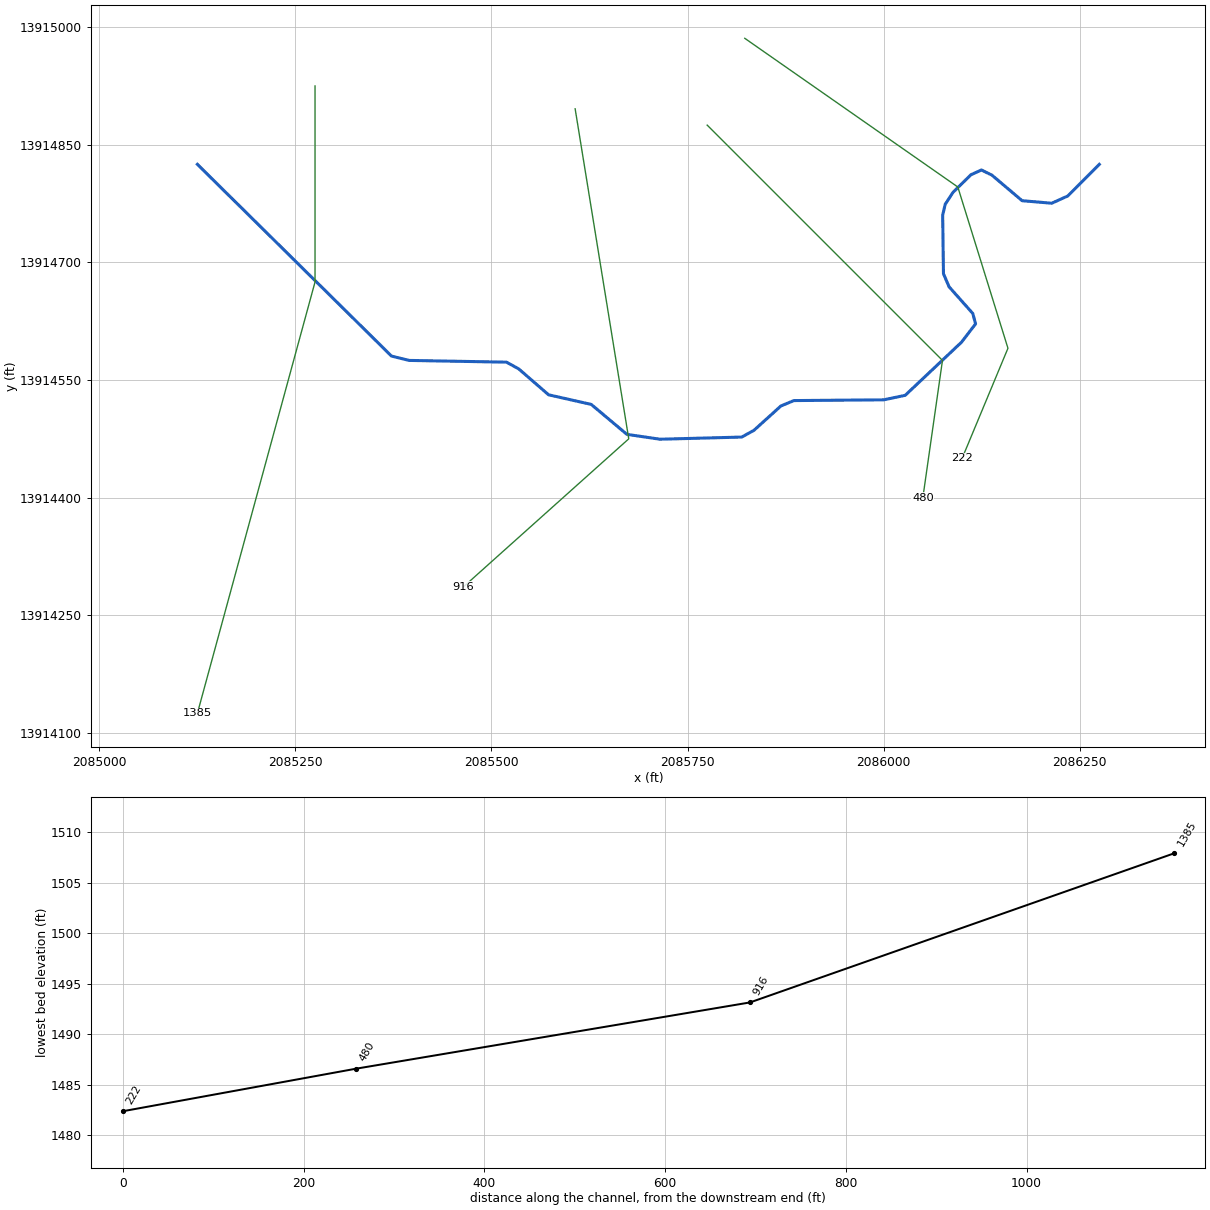
--- Stream0270_DS.prj (project) ---

Proj Title=Stream0270_DS Base Level Engineering
Current Plan=p01
Default Exp/Contr=0.3,0.1
English Units
Geom File=g01
Flow File=f01
Plan File=p01
BEGIN DESCRIPTION:
Stream0270_DS
END DESCRIPTION:

--- Stream0270_DS.p01 (plan) ---

Plan Title=Multiple Run
Short Identifier=Multiple
Geom File=g01
Flow File=f01
Subcritical Flow
K Sum by GR= 0
Std Step Tol= 0.01
Critical Tol= 0.01
Num of Std Step Trials= 20
Max Error Tol= 0.3
Flow Tol Ratio= 0.001
Split Flow NTrial= 30
Split Flow Tol= 0.02
Split Flow Ratio= 0.02
Log Output Level= 0
Friction Slope Method= 1
Unsteady Friction Slope Method= 2
Unsteady Bridges Friction Slope Method= 1
Parabolic Critical Depth
Global Vel Dist=  1 , 1 , 1
Global Log Level= 0
CheckData=True
Encroach Param= -1, 0, 0, 0
BEGIN DESCRIPTION:
Multiple Run
END DESCRIPTION:

--- Stream0270_DS.f01 (steady flow) ---

Flow Title=Multiple
Number of Profiles=7
Profile Names=10-year,25-year,50-year,1pct_min,100-year,1pct_plu,500-year
River Rch & RM= Stream0270_DS,Reach-1,1385
     518     852    1163     774    1545    3083    2692
Boundary for River Rch & Prof#=Stream0270_DS,Reach-1,1
Up Type=0
Dn Type=3
Dn Slope=0.005
Boundary for River Rch & Prof#=Stream0270_DS,Reach-1,2
Up Type=0
Dn Type=3
Dn Slope=0.005
Boundary for River Rch & Prof#=Stream0270_DS,Reach-1,3
Up Type=0
Dn Type=3
Dn Slope=0.005
Boundary for River Rch & Prof#=Stream0270_DS,Reach-1,4
Up Type=0
Dn Type=3
Dn Slope=0.005
Boundary for River Rch & Prof#=Stream0270_DS,Reach-1,5
Up Type=0
Dn Type=3
Dn Slope=0.005
Boundary for River Rch & Prof#=Stream0270_DS,Reach-1,6
Up Type=0
Dn Type=3
Dn Slope=0.005
Boundary for River Rch & Prof#=Stream0270_DS,Reach-1,7
Up Type=0
Dn Type=3
Dn Slope=0.005

--- Stream0270_DS.g01 (geometry) ---

Geom Title=Existing Conditions

River Reach=Stream0270_DS,Reach-1
Reach XY= 30
      2085125.00     13914825.00      2085372.55     13914580.47
      2085394.99     13914574.98      2085519.07     13914572.75
      2085534.67     13914564.20      2085572.82     13914531.12
      2085627.18     13914518.88      2085672.65     13914480.70
      2085714.83     13914474.50      2085819.06     13914477.25
      2085834.65     13914485.85      2085868.95     13914516.85
      2085885.51     13914523.77      2086000.12     13914524.73
      2086027.48     13914530.47      2086099.31     13914598.24
      2086117.21     13914621.57      2086113.67     13914634.84
      2086083.42     13914668.83      2086076.27     13914685.49
      2086075.25     13914760.06      2086078.46     13914773.98
      2086088.33     13914789.12      2086111.19     13914811.64
      2086124.66     13914817.78      2086138.06     13914811.20
      2086176.56     13914778.62      2086214.31     13914775.40
      2086234.79     13914784.65      2086275.00     13914825.00

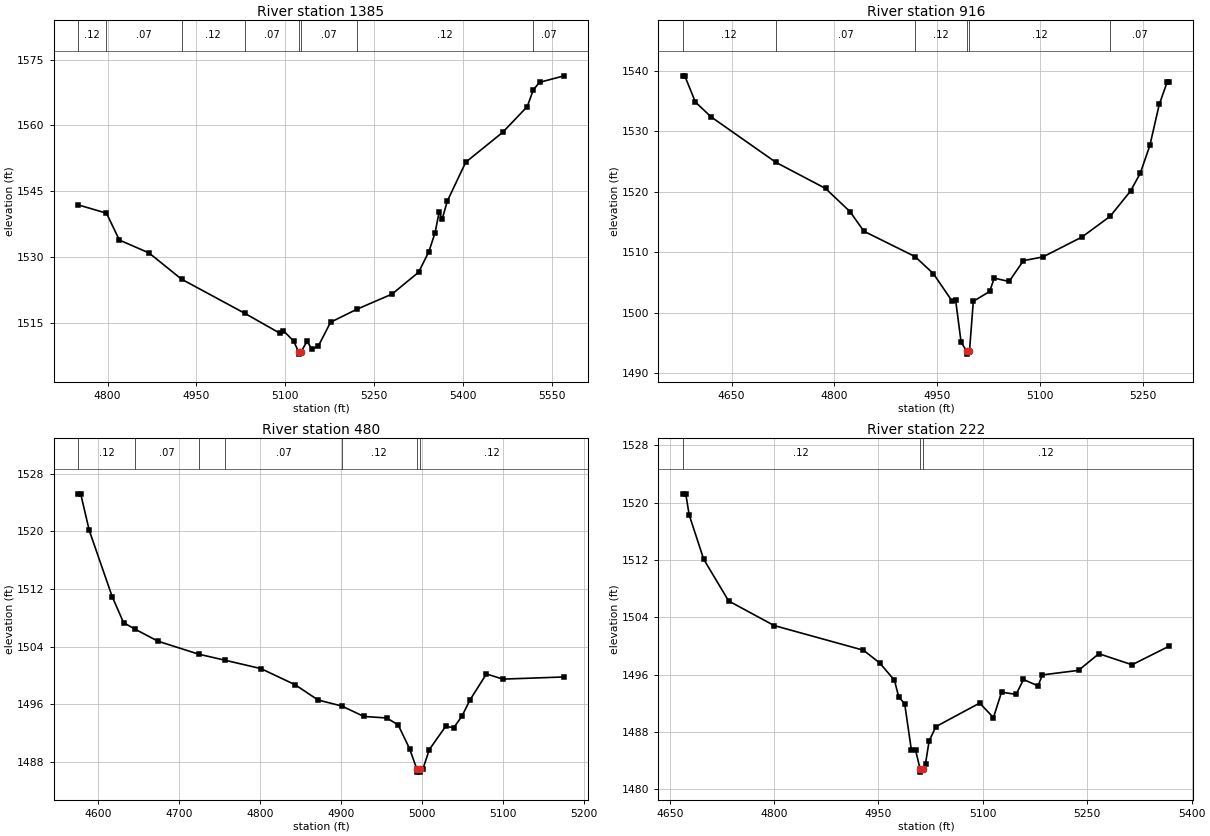
Type RM Length L Ch R = 1,1385,469,469,469
BEGIN DESCRIPTION:
Stream0270_DS 3.0
END DESCRIPTION:
XS GIS Cut Line= 3
      2085275.00     13914924.96      2085275.00     13914675.00
      2085124.99     13914124.95
#Sta/Elev= 30
  4750.0 1541.94  4798.3 1540.02  4820.0 1533.90  4870.0 1530.97  4924.8 1525.00
  5031.6 1517.21  5091.5 1512.62  5096.7 1513.26  5114.0 1510.88  5122.3 1508.42
  5122.6 1507.92  5126.3 1508.42  5136.4 1510.80  5145.1 1509.08  5155.4 1509.71
  5176.2 1515.18  5220.5 1518.14  5279.8 1521.59  5324.7 1526.58  5342.0 1531.27
  5352.4 1535.56  5359.3 1540.27  5364.5 1538.69  5373.1 1542.79  5404.2 1551.64
  5466.4 1558.43  5507.9 1564.30  5518.1 1568.10  5528.6 1569.83  5570.1 1571.31
#Mann=8,-1,0
  4750.0    0.12       0  4798.3    0.07       0  4924.8    0.12       0
  5031.6    0.07       0  5122.3    0.05       0  5126.3    0.07       0
  5220.5    0.12       0  5518.1    0.07       0
Bank Sta=5122.3,5126.3
Exp/Cntr=0.3,0.1

Type RM Length L Ch R = 1,916,436,436,436
BEGIN DESCRIPTION:
Stream0270_DS 2.0
END DESCRIPTION:
XS GIS Cut Line= 3
      2085606.66     13914895.78      2085675.00     13914475.00
      2085464.16     13914286.21
#Sta/Elev= 30
  4578.7 1539.19  4581.6 1539.19  4597.1 1534.85  4620.0 1532.40  4714.6 1524.88
  4786.9 1520.57  4822.6 1516.74  4842.9 1513.49  4917.5 1509.30  4944.2 1506.48
  4971.7 1501.91  4976.7 1502.11  4984.7 1495.12  4992.9 1493.67  4993.1 1493.17
  4996.9 1493.67  5002.5 1501.90  5026.3 1503.53  5033.0 1505.74  5054.7 1505.18
  5075.6 1508.63  5104.0 1509.24  5160.9 1512.53  5202.0 1515.95  5231.9 1520.15
  5246.1 1523.10  5260.0 1527.67  5273.7 1534.45  5285.2 1538.14  5288.0 1538.14
#Mann=6,-1,0
  4578.7    0.12       0  4714.6    0.07       0  4917.5    0.12       0
  4992.9    0.05       0  4996.9    0.12       0  5202.0    0.07       0
Bank Sta=4992.9,4996.9
Exp/Cntr=0.3,0.1

Type RM Length L Ch R = 1,480,258,258,258
BEGIN DESCRIPTION:
Stream0270_DS 1.0
END DESCRIPTION:
XS GIS Cut Line= 3
      2085775.03     13914874.97      2086075.00     13914575.00
      2086050.00     13914400.00
#Sta/Elev= 30
  4574.8 1525.21  4578.3 1525.21  4588.9 1520.13  4617.2 1510.96  4631.3 1507.34
  4645.8 1506.42  4673.8 1504.77  4724.1 1502.97  4757.1 1502.12  4801.0 1500.97
  4843.5 1498.72  4871.7 1496.61  4901.0 1495.78  4928.3 1494.33  4956.6 1494.12
  4970.7 1493.16  4984.9 1489.83  4993.5 1487.11  4993.7 1486.61  4997.2 1486.61
  4997.5 1487.11  5001.5 1487.11  5009.1 1489.72  5029.3 1492.95  5039.4 1492.78
  5049.5 1494.37  5059.6 1496.65  5079.8 1500.23  5100.0 1499.51  5175.8 1499.81
#Mann=7,-1,0
  4574.8    0.12       0  4645.8    0.07       0  4724.1    0.12       0
  4757.1    0.07       0  4901.0    0.12       0  4993.5    0.05       0
  4997.5    0.12       0
Bank Sta=4993.5,4997.5
Exp/Cntr=0.3,0.1

Type RM Length L Ch R = 1,222,0,0,0
BEGIN DESCRIPTION:
Stream0270_DS 0.0
END DESCRIPTION:
XS GIS Cut Line= 4
      2085822.97     13914985.64      2086094.57     13914796.09
      2086158.49     13914590.49      2086100.00     13914449.99
#Sta/Elev= 30
  4668.8 1521.21  4673.1 1521.21  4678.0 1518.27  4698.9 1512.08  4734.7 1506.27
  4800.1 1502.84  4928.4 1499.40  4951.8 1497.62  4972.9 1495.22  4979.0 1492.92
  4987.7 1491.91  4997.2 1485.52  5003.2 1485.52  5009.6 1482.90  5009.9 1482.40
  5013.6 1482.90  5017.6 1483.60  5022.8 1486.76  5032.6 1488.75  5095.4 1492.03
  5115.2 1490.00  5126.8 1493.55  5147.8 1493.24  5158.3 1495.32  5179.2 1494.43
  5185.6 1495.96  5237.4 1496.59  5266.7 1498.91  5314.4 1497.37  5367.5 1499.96
#Mann=3,-1,0
  4668.8    0.12       0  5009.6    0.05       0  5013.6    0.12       0
Bank Sta=5009.6,5013.6
Exp/Cntr=0.3,0.1

Chan Stop Cuts=-1