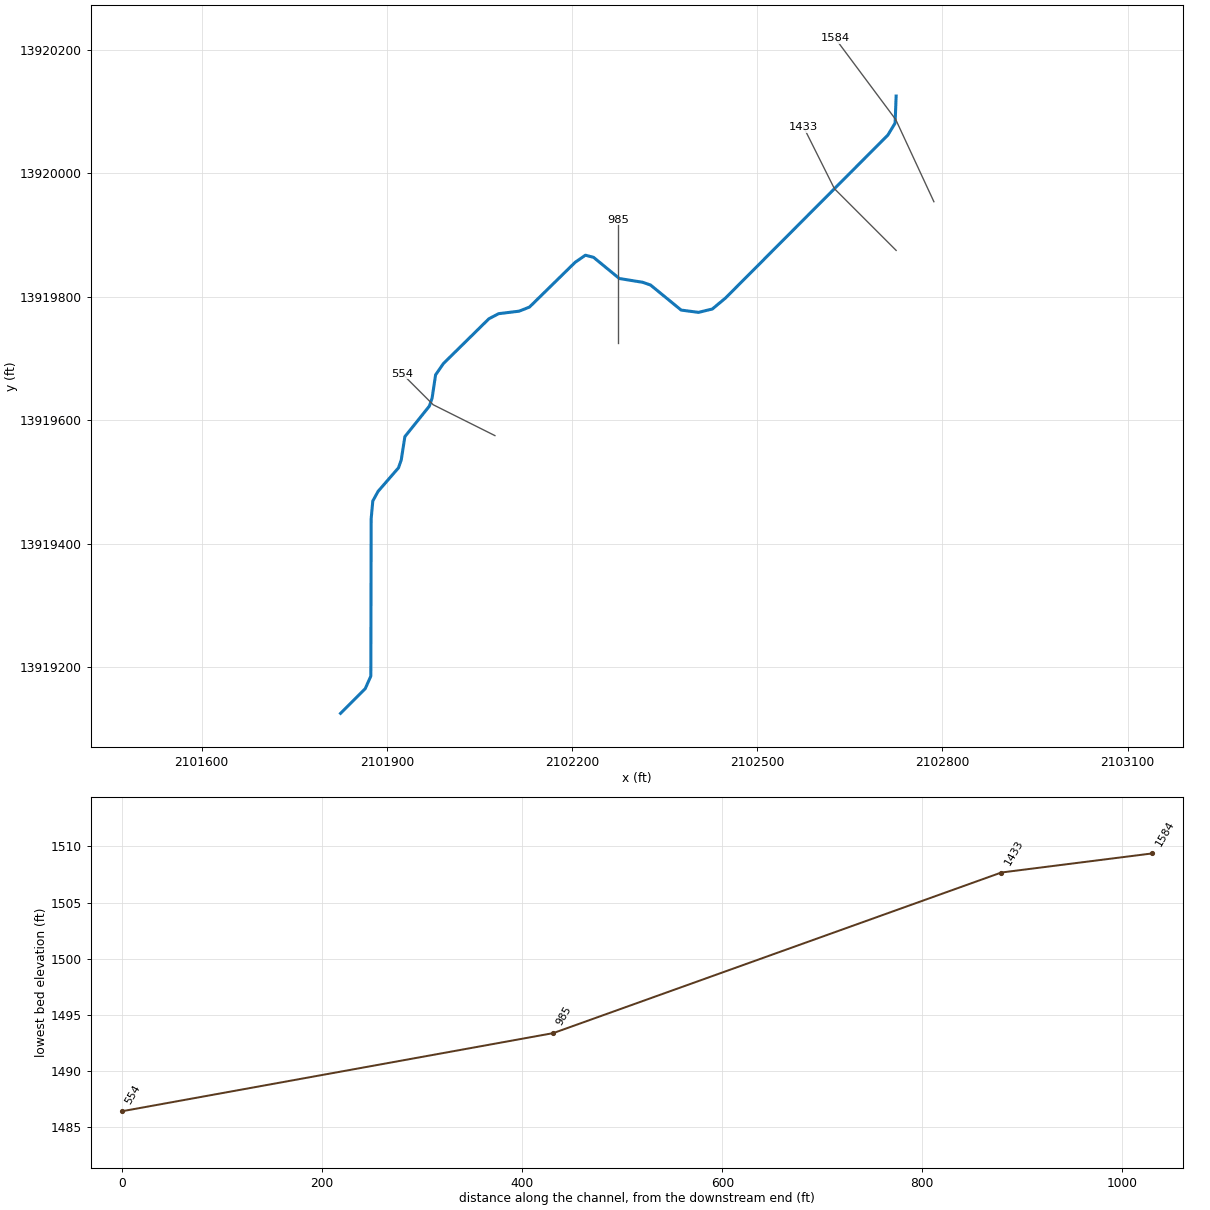
--- Stream0275_DS.prj (project) ---

Proj Title=Stream0275_DS Base Level Engineering
Current Plan=p01
Default Exp/Contr=0.3,0.1
English Units
Geom File=g01
Flow File=f01
Plan File=p01
BEGIN DESCRIPTION:
Stream0275_DS
END DESCRIPTION:

--- Stream0275_DS.p01 (plan) ---

Plan Title=Multiple Run
Short Identifier=Multiple
Geom File=g01
Flow File=f01
Subcritical Flow
K Sum by GR= 0
Std Step Tol= 0.01
Critical Tol= 0.01
Num of Std Step Trials= 20
Max Error Tol= 0.3
Flow Tol Ratio= 0.001
Split Flow NTrial= 30
Split Flow Tol= 0.02
Split Flow Ratio= 0.02
Log Output Level= 0
Friction Slope Method= 1
Unsteady Friction Slope Method= 2
Unsteady Bridges Friction Slope Method= 1
Parabolic Critical Depth
Global Vel Dist=  1 , 1 , 1
Global Log Level= 0
CheckData=True
Encroach Param= -1, 0, 0, 0
BEGIN DESCRIPTION:
Multiple Run
END DESCRIPTION:

--- Stream0275_DS.f01 (steady flow) ---

Flow Title=Multiple
Number of Profiles=7
Profile Names=10-year,25-year,50-year,1pct_min,100-year,1pct_plu,500-year
River Rch & RM= Stream0275_DS,Reach-1,1584
     932    1595    2233    1521    3035    6055    5549
Boundary for River Rch & Prof#=Stream0275_DS,Reach-1,1
Up Type=0
Dn Type=3
Dn Slope=0.005
Boundary for River Rch & Prof#=Stream0275_DS,Reach-1,2
Up Type=0
Dn Type=3
Dn Slope=0.005
Boundary for River Rch & Prof#=Stream0275_DS,Reach-1,3
Up Type=0
Dn Type=3
Dn Slope=0.005
Boundary for River Rch & Prof#=Stream0275_DS,Reach-1,4
Up Type=0
Dn Type=3
Dn Slope=0.005
Boundary for River Rch & Prof#=Stream0275_DS,Reach-1,5
Up Type=0
Dn Type=3
Dn Slope=0.005
Boundary for River Rch & Prof#=Stream0275_DS,Reach-1,6
Up Type=0
Dn Type=3
Dn Slope=0.005
Boundary for River Rch & Prof#=Stream0275_DS,Reach-1,7
Up Type=0
Dn Type=3
Dn Slope=0.005

--- Stream0275_DS.g01 (geometry) ---

Geom Title=Existing Conditions

River Reach=Stream0275_DS,Reach-1
Reach XY= 30
      2102725.00     13920125.00      2102723.32     13920081.14
      2102711.53     13920061.73      2102448.47     13919797.71
      2102427.30     13919780.09      2102404.87     13919774.59
      2102376.74     13919778.31      2102327.19     13919818.87
      2102314.30     13919823.36      2102276.63     13919829.43
      2102234.87     13919863.72      2102221.60     13919867.22
      2102204.99     13919855.68      2102131.05     13919783.20
      2102114.36     13919776.56      2102081.04     13919772.47
      2102065.30     13919764.23      2101991.63     13919691.71
      2101978.94     13919673.38      2101973.30     13919635.71
      2101968.90     13919622.82      2101929.16     13919573.28
      2101923.33     13919535.69      2101918.88     13919522.82
      2101885.80     13919484.67      2101877.24     13919469.07
      2101874.56     13919440.18      2101874.04     13919185.40
      2101864.95     13919165.02      2101825.00     13919125.00

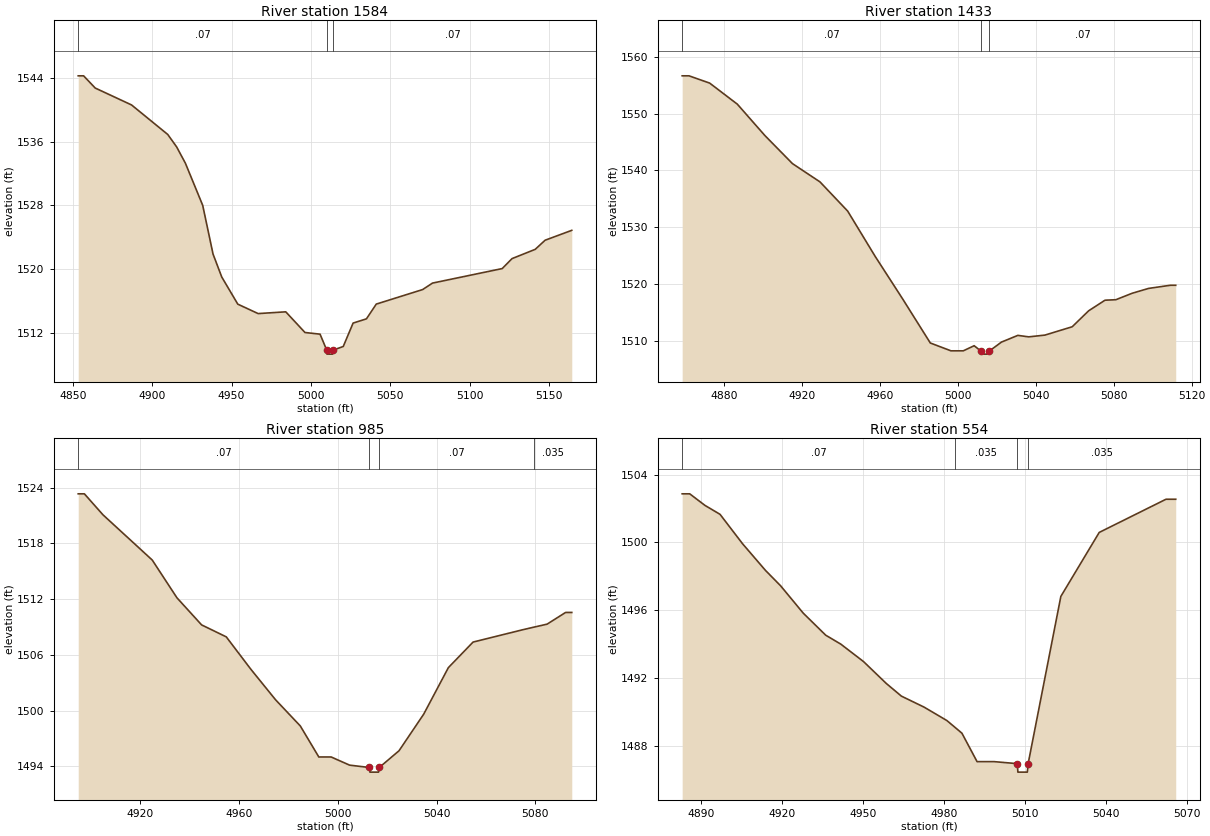
Type RM Length L Ch R = 1,1584,151,151,151
BEGIN DESCRIPTION:
Stream0275_DS 4.0
END DESCRIPTION:
XS GIS Cut Line= 3
      2102786.16     13919953.88      2102724.41     13920086.84
      2102626.32     13920218.53
#Sta/Elev= 30
  4853.4 1544.24  4856.8 1544.24  4864.1 1542.71  4887.0 1540.59  4909.8 1536.89
  4915.4 1535.33  4920.9 1533.29  4931.8 1528.01  4938.3 1521.91  4943.8 1519.03
  4953.9 1515.63  4966.7 1514.45  4984.1 1514.67  4996.2 1512.08  5005.7 1511.87
  5009.9 1509.87  5010.1 1509.37  5013.6 1509.37  5013.9 1509.87  5020.3 1510.33
  5026.5 1513.26  5034.9 1513.79  5041.1 1515.64  5070.3 1517.46  5076.5 1518.27
  5120.4 1520.09  5126.6 1521.34  5141.2 1522.50  5147.4 1523.64  5164.2 1524.88
#Mann=3,-1,0
  4853.4    0.07       0  5009.9    0.05       0  5013.9    0.07       0
Bank Sta=5009.9,5013.9
Exp/Cntr=0.3,0.1

Type RM Length L Ch R = 1,1433,448,448,448
BEGIN DESCRIPTION:
Stream0275_DS 3.0
END DESCRIPTION:
XS GIS Cut Line= 3
      2102725.00     13919875.00      2102625.00     13919975.00
      2102575.01     13920074.97
#Sta/Elev= 30
  4858.6 1556.66  4862.1 1556.66  4872.7 1555.38  4886.9 1551.67  4901.0 1546.16
  4915.2 1541.20  4929.3 1537.99  4943.5 1532.85  4957.6 1524.88  4971.7 1517.39
  4985.9 1509.63  4996.5 1508.25  5002.8 1508.25  5008.4 1509.15  5012.0 1508.17
  5012.3 1507.67  5015.8 1507.67  5016.0 1508.17  5022.4 1509.79  5030.8 1510.97
  5036.4 1510.71  5044.7 1511.02  5058.7 1512.49  5067.1 1515.29  5075.5 1517.16
  5081.1 1517.25  5089.5 1518.39  5097.9 1519.24  5109.0 1519.79  5111.8 1519.79
#Mann=3,-1,0
  4858.6    0.07       0  5012.0    0.05       0  5016.0    0.07       0
Bank Sta=5012,5016
Exp/Cntr=0.3,0.1

Type RM Length L Ch R = 1,985,431,431,431
BEGIN DESCRIPTION:
Stream0275_DS 2.0
END DESCRIPTION:
XS GIS Cut Line= 3
      2102275.00     13919725.05      2102275.00     13919825.00
      2102275.00     13919925.05
#Sta/Elev= 26
  4894.8 1523.34  4897.3 1523.34  4904.8 1521.09  4924.8 1516.21  4934.8 1512.15
  4944.8 1509.23  4954.8 1507.94  4964.8 1504.44  4974.8 1501.16  4984.8 1498.35
  4992.3 1495.01  4997.3 1495.01  5004.8 1494.13  5012.8 1493.88  5013.0 1493.38
  5016.5 1493.38  5016.8 1493.88  5024.8 1495.68  5034.8 1499.62  5044.8 1504.63
  5054.8 1507.38  5074.8 1508.70  5079.5 1508.99  5084.8 1509.31  5092.3 1510.57
  5094.8 1510.57
#Mann=4,-1,0
  4894.8    0.07       0  5012.8    0.05       0  5016.8    0.07       0
  5079.5   0.035       0
Bank Sta=5012.8,5016.8
Exp/Cntr=0.3,0.1

Type RM Length L Ch R = 1,554,0,0,0
BEGIN DESCRIPTION:
Stream0275_DS 1.0
END DESCRIPTION:
XS GIS Cut Line= 3
      2102075.04     13919574.98      2101975.00     13919625.00
      2101924.97     13919675.03
#Sta/Elev= 28
  4883.1 1502.87  4885.9 1502.87  4891.5 1502.19  4897.1 1501.66  4905.5 1499.91
  4913.9 1498.35  4919.5 1497.44  4927.9 1495.82  4936.2 1494.52  4941.8 1493.99
  4950.2 1492.96  4958.6 1491.67  4964.2 1490.92  4972.6 1490.27  4981.0 1489.48
  4984.0 1489.08  4986.6 1488.73  4992.2 1487.05  4994.9 1487.05  4998.5 1487.05
  5007.1 1486.93  5007.3 1486.43  5010.8 1486.43  5011.1 1486.93  5023.2 1496.81
  5037.4 1500.59  5062.1 1502.55  5065.7 1502.55
#Mann=4,-1,0
  4883.1    0.07       0  4984.0   0.035       0  5007.1   0.035       0
  5011.1   0.035       0
Bank Sta=5007.1,5011.1
Exp/Cntr=0.3,0.1

Chan Stop Cuts=-1