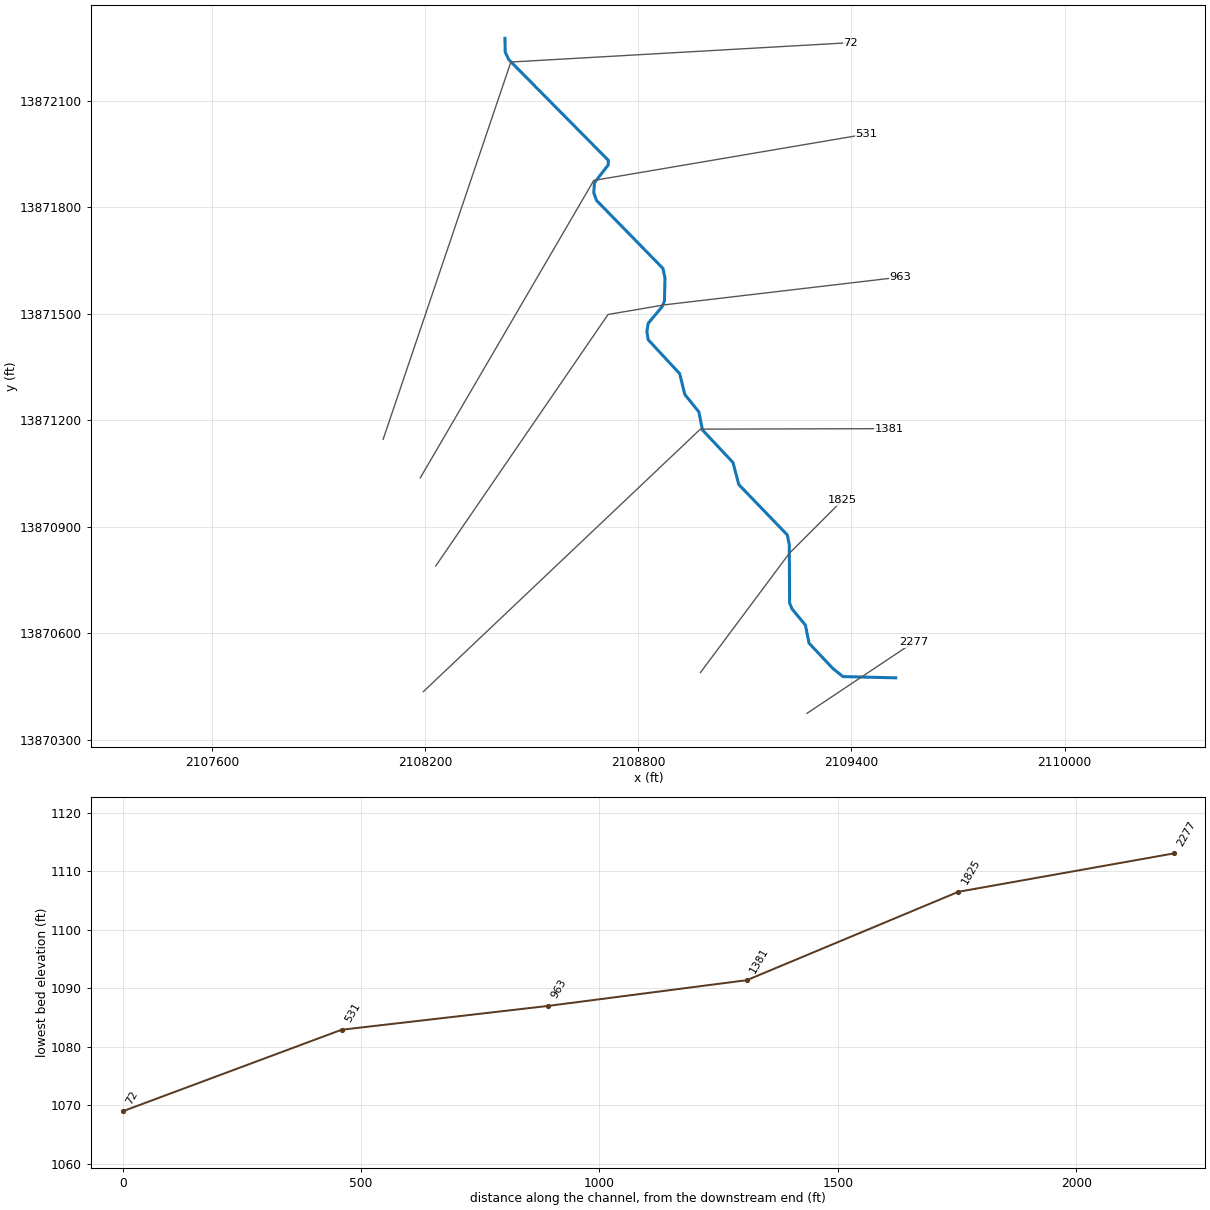
--- Stream0276_DS.prj (project) ---

Proj Title=Stream0276_DS Base Level Engineering
Current Plan=p01
Default Exp/Contr=0.3,0.1
English Units
Geom File=g01
Flow File=f01
Plan File=p01
Y Axis Title=Elevation
X Axis Title(PF)=Main Channel Distance
X Axis Title(XS)=Station
BEGIN DESCRIPTION:
Stream0276_DS
END DESCRIPTION:
DSS Export Rating Curves= 0
DSS Export Rating Curve Sorted= 0
DSS Export Volume Flow Curves= 0
DXF OffsetX= 0
DXF OffsetY= 0
DXF ScaleX= 1
DXF ScaleY= 10

--- Stream0276_DS.p01 (plan) ---

Plan Title=Multiple Run
Short Identifier=Multiple
Geom File=g01
Flow File=f01
Subcritical Flow
K Sum by GR= 0
Std Step Tol= 0.01
Critical Tol= 0.01
Num of Std Step Trials= 20
Max Error Tol= 0.3
Flow Tol Ratio= 0.001
Split Flow NTrial= 30
Split Flow Tol= 0.02
Split Flow Ratio= 0.02
Log Output Level= 0
Friction Slope Method= 1
Unsteady Friction Slope Method= 2
Unsteady Bridges Friction Slope Method= 1
Parabolic Critical Depth
Global Vel Dist=  1 , 1 , 1
Global Log Level= 0
CheckData=True
Encroach Param= -1, 0, 0, 0
BEGIN DESCRIPTION:
Multiple Run
END DESCRIPTION:

--- Stream0276_DS.f01 (steady flow) ---

Flow Title=Multiple
Program Version=4.10
Number of Profiles= 7
Profile Names=10-year,25-year,50-year,1pct_min,100-year,1pct_plu,500-year
River Rch & RM=Stream0276_DS,Reach-1         ,2277
     417     664     887     576    1150    2294    1905
River Rch & RM=Stream0276_DS,Reach-1         ,1825
     641    1051    1429     945    1885    3762    3238
Boundary for River Rch & Prof#=Stream0276_DS,Reach-1         , 1
Up Type= 0
Dn Type= 3
Dn Slope=0.005
Boundary for River Rch & Prof#=Stream0276_DS,Reach-1         , 2
Up Type= 0
Dn Type= 3
Dn Slope=0.005
Boundary for River Rch & Prof#=Stream0276_DS,Reach-1         , 3
Up Type= 0
Dn Type= 3
Dn Slope=0.005
Boundary for River Rch & Prof#=Stream0276_DS,Reach-1         , 4
Up Type= 0
Dn Type= 3
Dn Slope=0.005
Boundary for River Rch & Prof#=Stream0276_DS,Reach-1         , 5
Up Type= 0
Dn Type= 3
Dn Slope=0.005
Boundary for River Rch & Prof#=Stream0276_DS,Reach-1         , 6
Up Type= 0
Dn Type= 3
Dn Slope=0.005
Boundary for River Rch & Prof#=Stream0276_DS,Reach-1         , 7
Up Type= 0
Dn Type= 3
Dn Slope=0.005
DSS Import GetInterval= 0
DSS Import GetPeak= 0
DSS Import FillOption= 0

--- Stream0276_DS.g01 (geometry) ---

Geom Title=Existing Conditions
Program Version=4.10

River Reach=Stream0276_DS   ,Reach-1
Reach XY= 30
        2109525.       13870475.      2109376.44     13870478.49
      2109348.07     13870501.14      2109280.82     13870572.69
      2109270.78     13870623.25      2109233.09     13870668.92
       2109226.2      13870685.5      2109225.29     13870850.12
      2109219.54     13870877.45      2109083.16     13871018.95
      2109066.82     13871081.04      2108980.85     13871172.71
      2108970.81     13871223.27       2108931.1     13871272.81
      2108916.84     13871331.05      2108828.14     13871426.64
      2108824.51     13871449.96      2108828.34     13871473.25
      2108866.86     13871518.95      2108873.88     13871535.55
       2108875.5     13871600.04       2108869.6     13871627.43
       2108682.5     13871818.95      2108675.01     13871840.36
      2108676.99     13871868.95      2108715.67     13871918.45
      2108715.85     13871931.73      2108435.51     13872215.21
      2108425.59     13872236.84        2108425.       13872275.

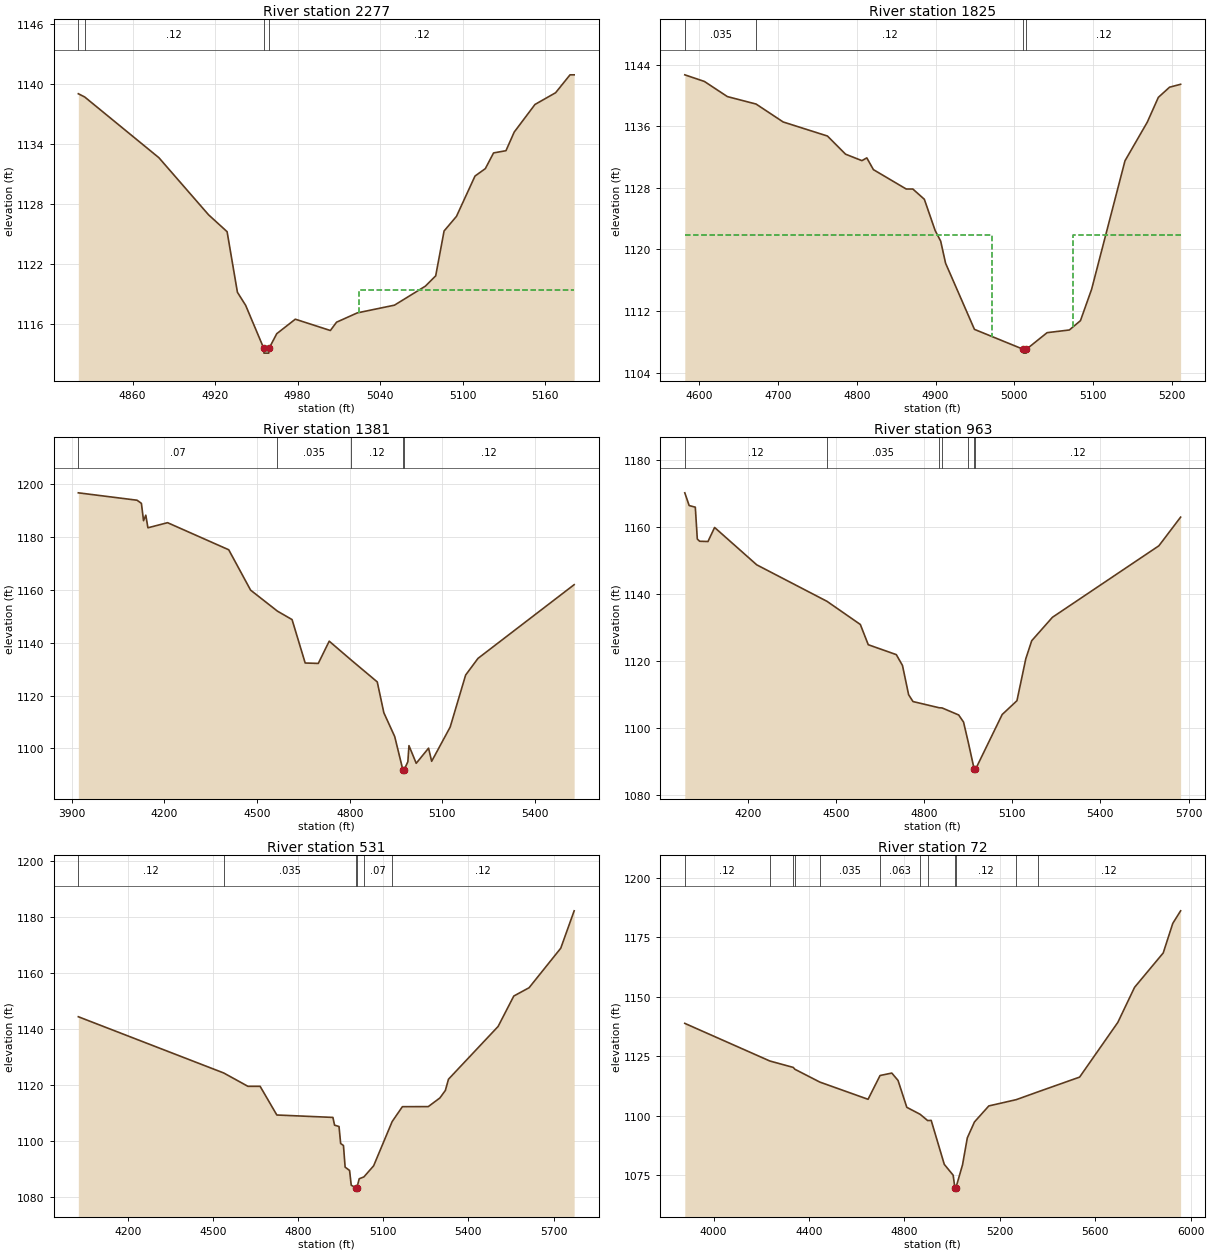
Type RM Length L Ch R = 1 ,2277    ,452,452,452
BEGIN DESCRIPTION:
Stream0276_DS 5.0
END DESCRIPTION:
XS GIS Cut Line= 3
      2109274.96     13870374.97        2109425.       13870475.
        2109575.       13870575.
#Sta/Elev= 30
  4820.6 1138.99  4825.2 1138.67  4879.2  1132.6  4915.3  1126.9  4928.8 1125.21
  4936.3 1119.16  4942.3 1117.85  4955.4 1113.58  4955.6 1113.08  4959.1 1113.08
  4959.4 1113.58  4964.9 1115.02  4978.4 1116.47  5003.9 1115.34  5008.4 1116.17
  5023.5  1117.1  5050.5 1117.87    5073 1119.77  5080.5  1120.8  5086.6 1125.28
  5095.6 1126.74  5109.1 1130.77  5116.6 1131.51  5122.6 1133.08  5131.6  1133.3
  5137.6 1135.16  5152.7 1137.92  5167.7 1139.09  5178.2 1140.88  5181.2 1140.88
#Mann= 4 ,-1 , 0
  4820.6     .07       0  4825.2     .12       0  4955.4     .05       0
  4959.4     .12       0
#XS Ineff= 2 , 0
       0                  5024.6       0  1119.4
Permanent Ineff=
       F       F
Bank Sta=4955.4,4959.4
XS Rating Curve= 0 ,0
Exp/Cntr=0.3,0.1

Type RM Length L Ch R = 1 ,1825    ,444,444,444
BEGIN DESCRIPTION:
Stream0276_DS 4.0
END DESCRIPTION:
XS GIS Cut Line= 3
      2108975.23     13870489.84        2109225.       13870825.
      2109374.99     13870974.99
#Sta/Elev= 30
  4581.4 1142.71  4606.3 1141.85  4635.5 1139.88    4672 1138.91  4706.4 1136.58
  4762.7 1134.75  4785.7 1132.39  4806.5 1131.55  4812.7 1131.91  4821.1 1130.38
  4862.8 1127.86  4871.2 1127.86  4885.8 1126.53  4899.6 1122.45  4906.6 1121.08
  4912.8 1118.21  4949.5 1109.61  5011.5 1107.02  5011.8 1106.52  5015.3 1106.52
  5015.5 1107.02  5041.8 1109.18  5070.1 1109.53  5084.2 1110.74  5098.4 1114.83
  5140.8 1131.53  5169.1 1136.55  5183.2 1139.78  5197.4  1141.1  5211.5 1141.48
#Mann= 4 ,-1 , 0
  4581.4    .035       0    4672     .12       0  5011.5     .05       0
  5015.5     .12       0
#XS Ineff= 2 , 0
       0 4972.04 1121.93 5074.52       0 1121.93
Permanent Ineff=
       F       F
Bank Sta=5011.5,5015.5
XS Rating Curve= 0 ,0
Exp/Cntr=0.3,0.1

Type RM Length L Ch R = 1 ,1381    ,418,418,418
BEGIN DESCRIPTION:
Stream0276_DS 3.0
END DESCRIPTION:
XS GIS Cut Line= 3
      2108195.24     13870436.08        2108975.       13871175.
      2109506.54     13871176.38
#Sta/Elev= 30
    3921 1196.73  4111.2 1193.93  4125.3 1192.74  4132.2 1186.18  4139.5 1188.27
  4146.4  1183.5    4210 1185.43  4408.1 1175.18  4478.9 1159.91  4565.9 1151.95
  4613.2 1148.76  4655.7 1132.33  4698.1 1132.17  4733.5 1140.59  4803.3 1133.59
  4889.1 1125.17  4910.5 1113.49  4945.7 1104.48    4972 1091.91  4972.3 1091.41
    4976 1091.91  4988.2 1094.95  4991.8 1101.06  5015.3 1094.37  5055.3 1100.11
  5065.3 1095.13  5125.3  1108.1  5175.3 1127.76  5215.3 1134.07  5526.8 1161.97
#Mann= 5 ,-1 , 0
    3921     .07       0  4565.9    .035       0  4803.3     .12       0
    4972     .05       0    4976     .12       0
Bank Sta=4972,4976
XS Rating Curve= 0 ,0
Exp/Cntr=0.3,0.1

Type RM Length L Ch R = 1 ,963     ,432,432,432
BEGIN DESCRIPTION:
Stream0276_DS 2.0
END DESCRIPTION:
XS GIS Cut Line= 4
      2108230.12     13870789.89      2108715.15     13871497.74
        2108875.       13871525.      2109538.49     13871602.98
#Sta/Elev= 30
  3984.8 1170.13  3999.7 1166.33  4020.6 1165.84  4027.4 1156.33  4035.5 1155.66
  4063.7 1155.59  4086.3 1159.78  4229.8 1148.62  4468.8 1137.73  4582.5 1130.81
  4609.5 1124.76    4705  1121.8    4726 1118.57    4747 1109.81  4761.9 1107.78
  4850.9 1105.93  4860.8 1105.88  4917.3 1103.78    4934 1101.64  4950.4 1095.47
  4970.4  1087.5  4970.7    1087  4974.4  1087.5  5065.5 1103.91  5115.8 1108.04
    5146 1120.59  5166.1 1125.96  5236.6 1132.95  5599.1 1154.31  5673.1 1162.87
#Mann= 7 ,-1 , 0
  3984.8     .12       0  4468.8    .035       0  4850.9     .12       0
  4860.8    .035       0  4950.4     .12       0  4970.4     .05       0
  4974.4     .12       0
Bank Sta=4970.4,4974.4
XS Rating Curve= 0 ,0
Exp/Cntr=0.3,0.1

Type RM Length L Ch R = 1 ,531     ,459,459,459
BEGIN DESCRIPTION:
Stream0276_DS 1.0
END DESCRIPTION:
XS GIS Cut Line= 3
      2108186.65     13871037.76        2108675.       13871875.
      2109441.54     13872005.35
#Sta/Elev= 30
  4025.8 1144.38  4538.2 1124.33  4623.3 1119.58  4666.3 1119.58  4725.1 1109.36
  4922.7  1108.5  4928.5 1105.74  4944.2 1105.26    4950 1099.21  4959.9 1098.47
  4965.7 1090.78  4981.4 1089.59  4987.2 1084.34  5003.2 1083.44  5003.4 1082.94
  5007.2 1083.44  5015.3 1086.63  5031.9  1087.3  5066.1 1091.24  5131.4 1107.02
  5167.5 1112.33  5258.6 1112.35  5299.4 1115.42  5318.8  1118.1  5329.8 1122.11
  5504.7 1140.92  5559.9 1151.76  5613.8 1154.72  5725.4 1168.81  5772.6 1182.13
#Mann= 6 ,-1 , 0
  4025.8     .12       0  4538.2    .035       0  5003.2    .035       0
  5007.2    .035       0  5031.9     .07       0  5131.4     .12       0
Bank Sta=5003.2,5007.2
XS Rating Curve= 0 ,0
Exp/Cntr=0.3,0.1

Type RM Length L Ch R = 1 ,72      ,0,0,0
BEGIN DESCRIPTION:
Stream0276_DS 0.0
END DESCRIPTION:
XS GIS Cut Line= 3
      2108082.19     13871146.57      2108441.58      13872208.3
      2109397.82     13872262.87
#Sta/Elev= 30
  3879.1 1138.78  4235.7 1122.94  4333.8 1120.24  4340.6 1119.46  4445.6 1114.05
  4647.4 1106.82  4697.7 1116.83    4747 1117.86  4773.1 1114.76  4809.9 1103.44
  4865.4 1100.53  4897.3 1097.87  4912.1 1097.94    4967 1079.43  5004.2 1074.87
  5011.4 1069.51  5011.7 1069.01  5015.4 1069.51  5043.5 1079.26  5063.5 1090.58
  5093.6  1097.3  5153.7 1104.03  5268.7 1106.67  5358.2  1109.9  5534.3 1116.16
  5694.6  1139.2  5764.7 1153.95  5884.9 1168.43  5924.9 1180.87  5957.8 1186.15
#Mann= 12 ,-1 , 0
  3879.1     .12       0  4235.7     .07       0  4333.8     .12       0
  4340.6     .07       0  4445.6    .035       0  4697.7    .063       0
  4865.4    .035       0  4897.3     .12       0  5011.4     .05       0
  5015.4     .12       0  5268.7     .07       0  5358.2     .12       0
Bank Sta=5011.4,5015.4
XS Rating Curve= 0 ,0
Exp/Cntr=0.3,0.1

Chan Stop Cuts=-1
Use User Specified Reach Order=0
Composite Channel Slope=5