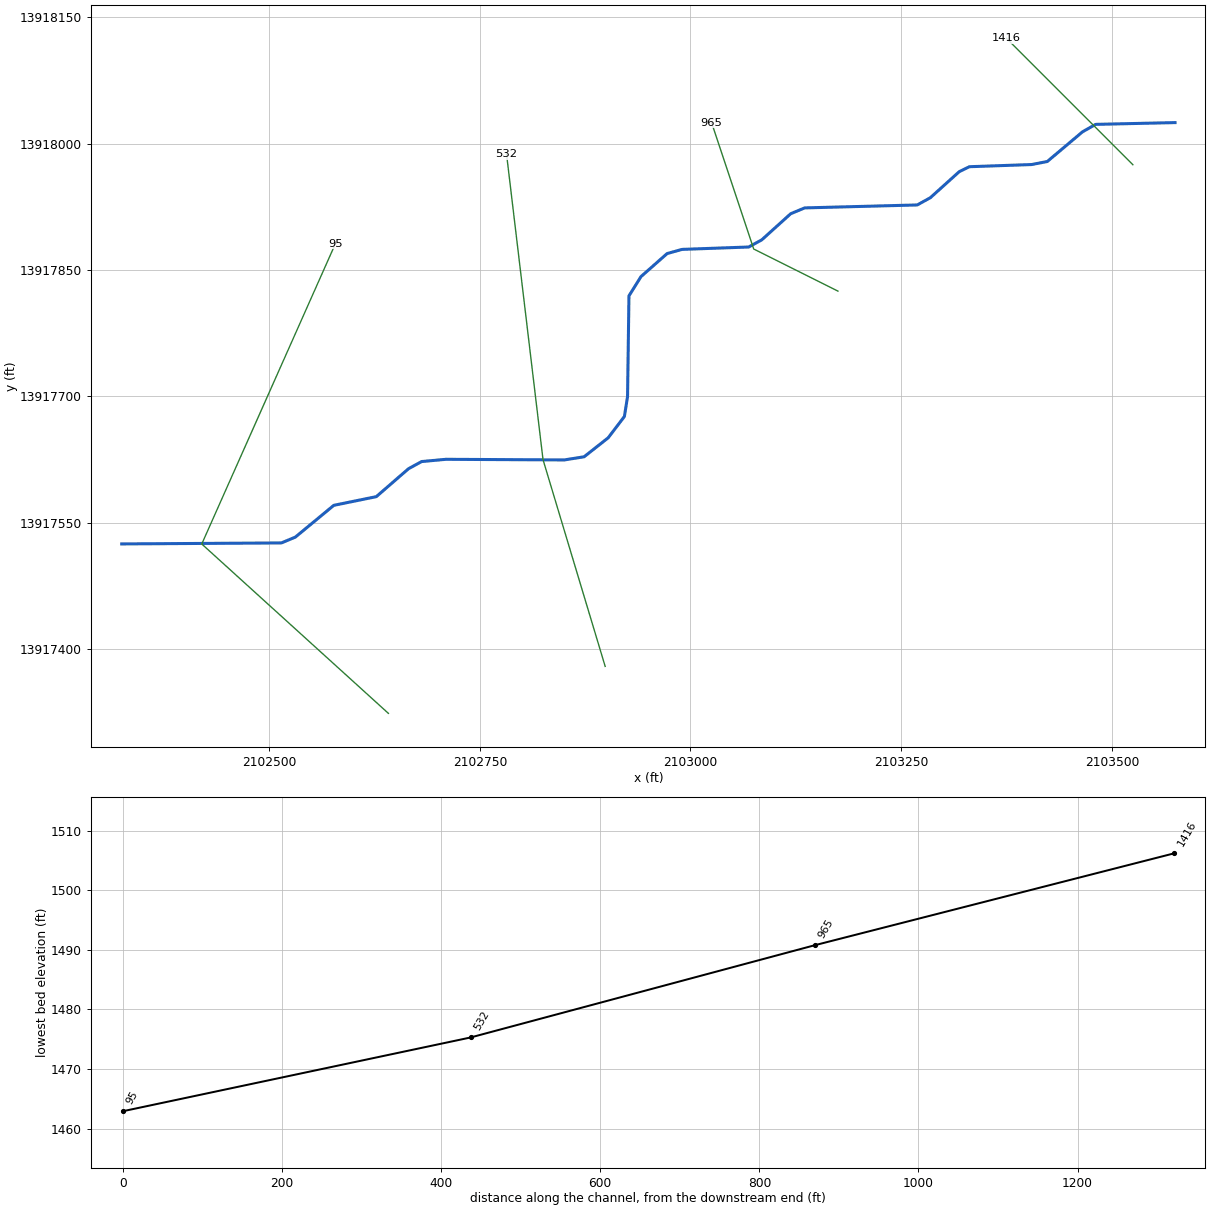
--- Stream0279_DS.prj (project) ---

Proj Title=Stream0279_DS Base Level Engineering
Current Plan=p01
Default Exp/Contr=0.3,0.1
English Units
Geom File=g01
Flow File=f01
Plan File=p01
BEGIN DESCRIPTION:
Stream0279_DS
END DESCRIPTION:

--- Stream0279_DS.p01 (plan) ---

Plan Title=Multiple Run
Short Identifier=Multiple
Geom File=g01
Flow File=f01
Subcritical Flow
K Sum by GR= 0
Std Step Tol= 0.01
Critical Tol= 0.01
Num of Std Step Trials= 20
Max Error Tol= 0.3
Flow Tol Ratio= 0.001
Split Flow NTrial= 30
Split Flow Tol= 0.02
Split Flow Ratio= 0.02
Log Output Level= 0
Friction Slope Method= 1
Unsteady Friction Slope Method= 2
Unsteady Bridges Friction Slope Method= 1
Parabolic Critical Depth
Global Vel Dist=  1 , 1 , 1
Global Log Level= 0
CheckData=True
Encroach Param= -1, 0, 0, 0
BEGIN DESCRIPTION:
Multiple Run
END DESCRIPTION:

--- Stream0279_DS.f01 (steady flow) ---

Flow Title=Multiple
Number of Profiles=7
Profile Names=10-year,25-year,50-year,1pct_min,100-year,1pct_plu,500-year
River Rch & RM= Stream0279_DS,Reach-1,1416
     640    1076    1490    1006    2008    4006    3602
Boundary for River Rch & Prof#=Stream0279_DS,Reach-1,1
Up Type=0
Dn Type=3
Dn Slope=0.005
Boundary for River Rch & Prof#=Stream0279_DS,Reach-1,2
Up Type=0
Dn Type=3
Dn Slope=0.005
Boundary for River Rch & Prof#=Stream0279_DS,Reach-1,3
Up Type=0
Dn Type=3
Dn Slope=0.005
Boundary for River Rch & Prof#=Stream0279_DS,Reach-1,4
Up Type=0
Dn Type=3
Dn Slope=0.005
Boundary for River Rch & Prof#=Stream0279_DS,Reach-1,5
Up Type=0
Dn Type=3
Dn Slope=0.005
Boundary for River Rch & Prof#=Stream0279_DS,Reach-1,6
Up Type=0
Dn Type=3
Dn Slope=0.005
Boundary for River Rch & Prof#=Stream0279_DS,Reach-1,7
Up Type=0
Dn Type=3
Dn Slope=0.005

--- Stream0279_DS.g01 (geometry) ---

Geom Title=Existing Conditions

River Reach=Stream0279_DS,Reach-1
Reach XY= 30
      2103575.00     13918025.00      2103480.87     13918022.90
      2103465.35     13918014.15      2103423.42     13917978.83
      2103404.90     13917975.23      2103330.98     13917972.65
      2103318.97     13917966.81      2103284.65     13917935.85
      2103269.06     13917927.27      2103135.51     13917923.77
      2103118.94     13917916.86      2103084.63     13917885.90
      2103069.02     13917877.36      2102990.07     13917874.54
      2102972.29     13917869.60      2102941.24     13917842.22
      2102926.98     13917819.35      2102925.31     13917699.79
      2102921.56     13917676.22      2102902.35     13917650.97
      2102873.78     13917628.43      2102850.22     13917624.67
      2102709.82     13917625.43      2102680.93     13917622.76
      2102665.33     13917614.20      2102627.18     13917581.12
      2102576.74     13917570.81      2102531.08     13917533.09
      2102514.51     13917526.19      2102325.00     13917525.00

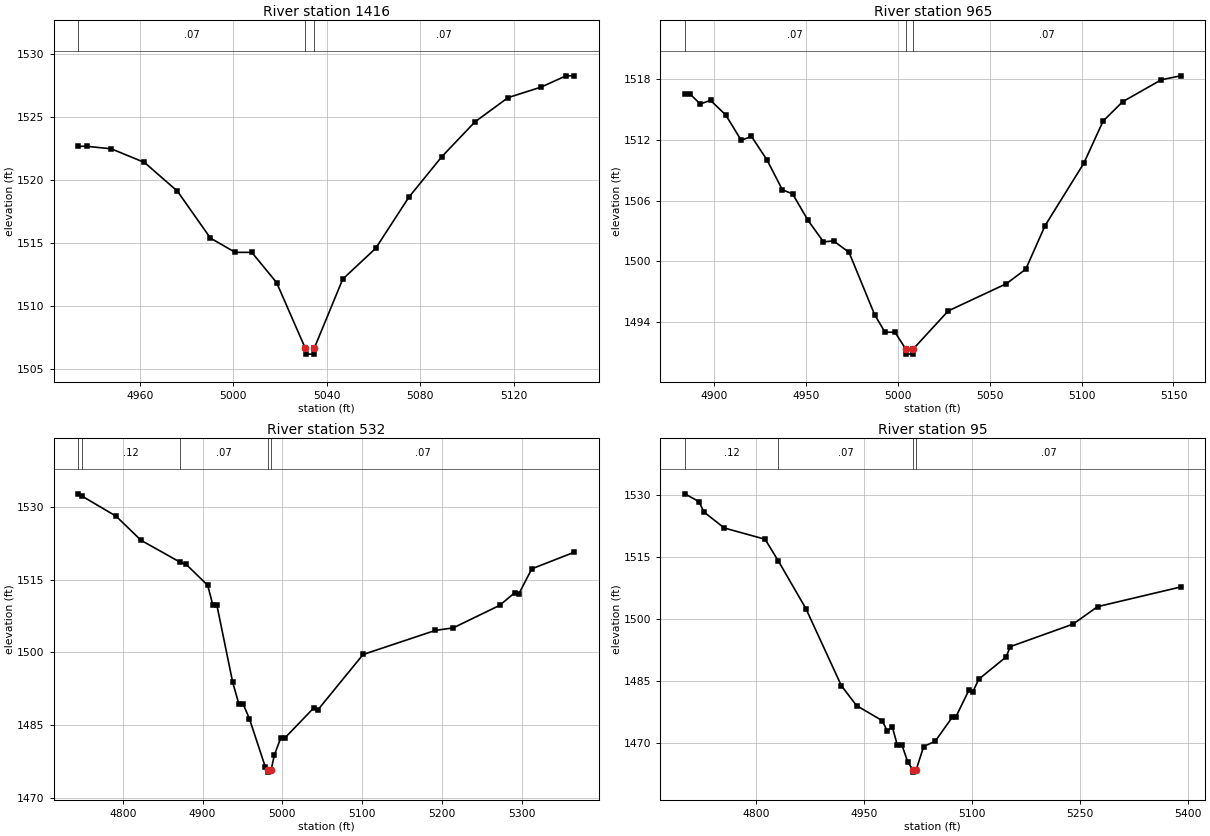
Type RM Length L Ch R = 1,1416,451,451,451
BEGIN DESCRIPTION:
Stream0279_DS 3.0
END DESCRIPTION:
XS GIS Cut Line= 3
      2103524.98     13917975.02      2103475.00     13918025.00
      2103375.00     13918125.00
#Sta/Elev= 22
  4933.7 1522.66  4937.2 1522.66  4947.8 1522.46  4962.0 1521.38  4976.1 1519.10
  4990.2 1515.39  5000.8 1514.26  5007.9 1514.26  5018.5 1511.87  5030.7 1506.70
  5030.9 1506.20  5034.4 1506.20  5034.7 1506.70  5046.8 1512.14  5060.9 1514.58
  5075.1 1518.63  5089.2 1521.84  5103.4 1524.60  5117.5 1526.51  5131.7 1527.35
  5142.3 1528.24  5145.8 1528.24
#Mann=3,-1,0
  4933.7    0.07       0  5030.7    0.05       0  5034.7    0.07       0
Bank Sta=5030.7,5034.7
Exp/Cntr=0.3,0.1

Type RM Length L Ch R = 1,965,433,433,433
BEGIN DESCRIPTION:
Stream0279_DS 2.0
END DESCRIPTION:
XS GIS Cut Line= 3
      2103174.99     13917825.01      2103075.00     13917875.00
      2103025.00     13918025.00
#Sta/Elev= 30
  4884.0 1516.57  4886.8 1516.57  4892.4 1515.57  4898.0 1515.93  4906.3 1514.48
  4914.7 1511.98  4920.3 1512.36  4928.7 1510.04  4937.1 1507.08  4942.7 1506.66
  4951.1 1504.04  4959.5 1501.92  4965.0 1502.01  4973.4 1500.88  4987.4 1494.68
  4993.0 1492.97  4998.4 1492.97  5004.3 1491.30  5004.6 1490.80  5008.1 1490.80
  5008.3 1491.30  5027.4 1495.08  5059.0 1497.77  5069.6 1499.21  5080.1 1503.52
  5101.2 1509.70  5111.7 1513.88  5122.3 1515.79  5143.4 1517.97  5153.9 1518.36
#Mann=3,-1,0
  4884.0    0.07       0  5004.3    0.05       0  5008.3    0.07       0
Bank Sta=5004.3,5008.3
Exp/Cntr=0.3,0.1

Type RM Length L Ch R = 1,532,437,437,437
BEGIN DESCRIPTION:
Stream0279_DS 1.0
END DESCRIPTION:
XS GIS Cut Line= 3
      2102898.76     13917379.68      2102825.00     13917625.00
      2102781.69     13917987.76
#Sta/Elev= 30
  4744.3 1532.72  4749.1 1532.23  4791.6 1528.11  4822.9 1523.13  4871.4 1518.66
  4879.6 1518.14  4906.5 1513.84  4912.7 1509.88  4917.9 1509.80  4937.8 1493.82
  4945.7 1489.26  4950.9 1489.32  4958.7 1486.35  4978.7 1476.34  4982.0 1475.80
  4982.2 1475.30  4986.0 1475.80  4990.0 1478.81  4997.9 1482.31  5003.0 1482.31
  5039.2 1488.52  5044.2 1488.07  5101.2 1499.57  5191.8 1504.54  5214.2 1505.06
  5272.4 1509.71  5291.6 1512.35  5296.6 1512.12  5312.7 1517.25  5365.8 1520.66
#Mann=5,-1,0
  4744.3    0.07       0  4749.1    0.12       0  4871.4    0.07       0
  4982.0    0.05       0  4986.0    0.07       0
Bank Sta=4982,4986
Exp/Cntr=0.3,0.1

Type RM Length L Ch R = 1,95,0,0,0
BEGIN DESCRIPTION:
Stream0279_DS 0.0
END DESCRIPTION:
XS GIS Cut Line= 3
      2102641.52     13917323.92      2102420.03     13917524.93
      2102578.67     13917881.42
#Sta/Elev= 30
  4700.9 1530.37  4720.6 1528.49  4727.4 1525.97  4755.8 1522.09  4812.5 1519.36
  4831.0 1514.08  4869.3 1502.53  4918.6 1483.86  4939.6 1479.06  4975.4 1475.39
  4982.2 1472.95  4989.6 1473.76  4996.3 1469.48  5002.8 1469.48  5011.0 1465.31
  5018.5 1463.42  5018.8 1462.92  5022.5 1463.42  5032.9 1469.10  5049.2 1470.45
  5072.5 1476.17  5077.9 1476.36  5095.7 1482.73  5101.2 1482.31  5109.5 1485.43
  5147.7 1490.86  5153.3 1493.33  5240.6 1498.79  5274.8 1503.03  5390.2 1507.79
#Mann=4,-1,0
  4700.9    0.12       0  4831.0    0.07       0  5018.5    0.05       0
  5022.5    0.07       0
Bank Sta=5018.5,5022.5
Exp/Cntr=0.3,0.1

Chan Stop Cuts=-1