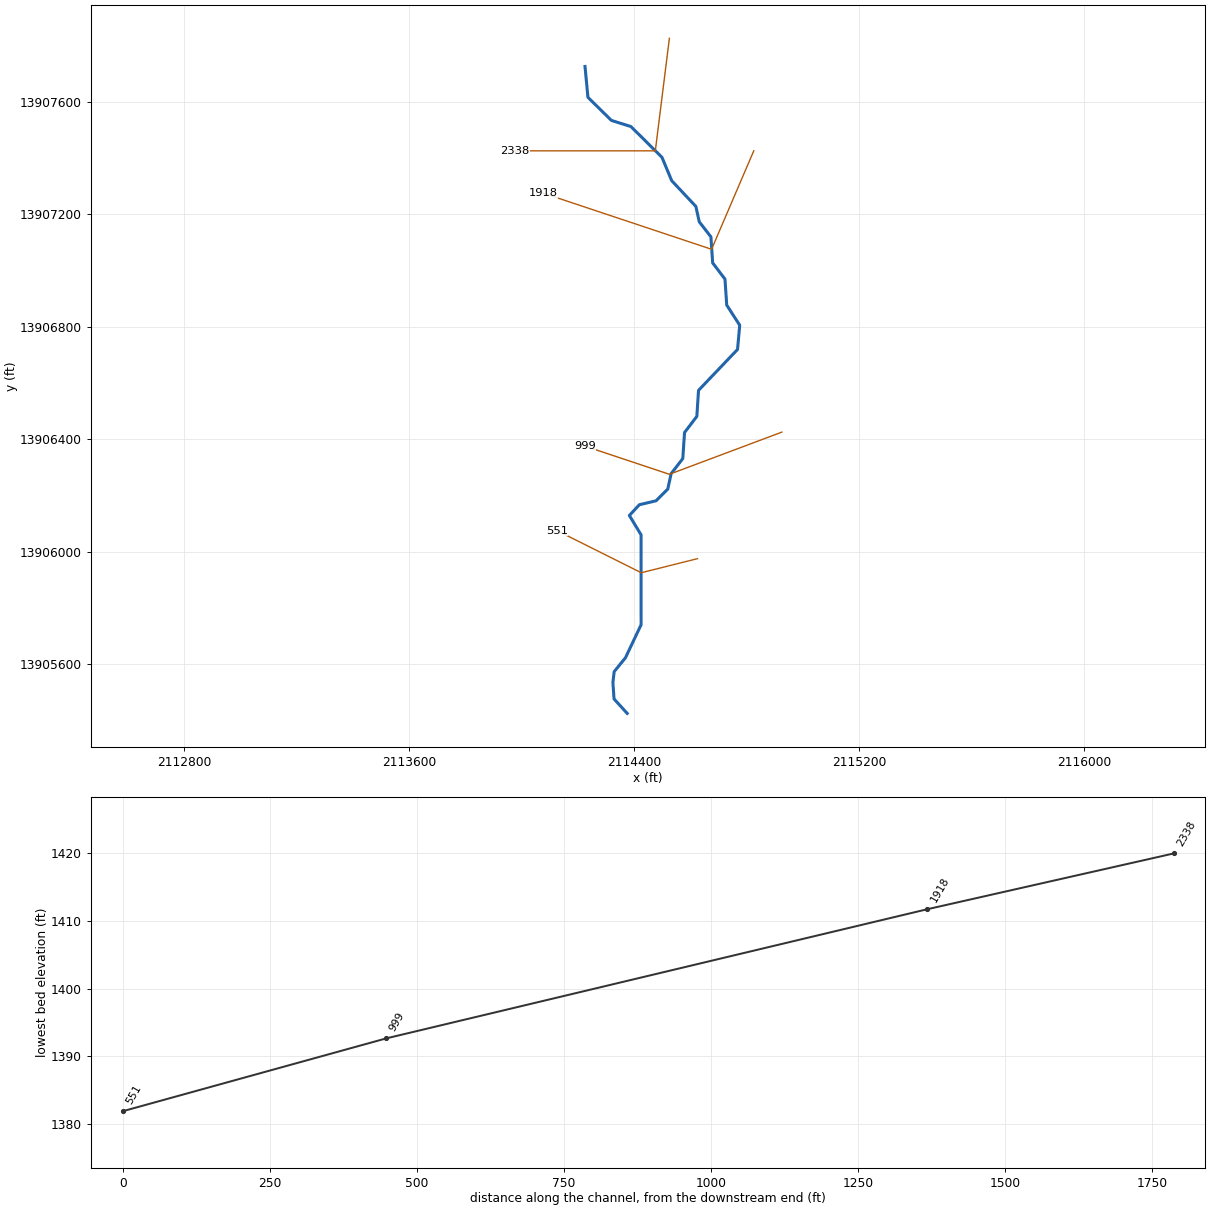
--- Stream0280_DS.prj (project) ---

Proj Title=Stream0280_DS Base Level Engineering
Current Plan=p01
Default Exp/Contr=0.3,0.1
English Units
Geom File=g01
Flow File=f01
Plan File=p01
BEGIN DESCRIPTION:
Stream0280_DS
END DESCRIPTION:

--- Stream0280_DS.p01 (plan) ---

Plan Title=Multiple Run
Short Identifier=Multiple
Geom File=g01
Flow File=f01
Subcritical Flow
K Sum by GR= 0
Std Step Tol= 0.01
Critical Tol= 0.01
Num of Std Step Trials= 20
Max Error Tol= 0.3
Flow Tol Ratio= 0.001
Split Flow NTrial= 30
Split Flow Tol= 0.02
Split Flow Ratio= 0.02
Log Output Level= 0
Friction Slope Method= 1
Unsteady Friction Slope Method= 2
Unsteady Bridges Friction Slope Method= 1
Parabolic Critical Depth
Global Vel Dist=  1 , 1 , 1
Global Log Level= 0
CheckData=True
Encroach Param= -1, 0, 0, 0
BEGIN DESCRIPTION:
Multiple Run
END DESCRIPTION:

--- Stream0280_DS.f01 (steady flow) ---

Flow Title=Multiple
Number of Profiles=7
Profile Names=10-year,25-year,50-year,1pct_min,100-year,1pct_plu,500-year
River Rch & RM= Stream0280_DS,Reach-1,2338
     961    1631    2271    1537    3066    6118    5519
Boundary for River Rch & Prof#=Stream0280_DS,Reach-1,1
Up Type=0
Dn Type=3
Dn Slope=0.005
Boundary for River Rch & Prof#=Stream0280_DS,Reach-1,2
Up Type=0
Dn Type=3
Dn Slope=0.005
Boundary for River Rch & Prof#=Stream0280_DS,Reach-1,3
Up Type=0
Dn Type=3
Dn Slope=0.005
Boundary for River Rch & Prof#=Stream0280_DS,Reach-1,4
Up Type=0
Dn Type=3
Dn Slope=0.005
Boundary for River Rch & Prof#=Stream0280_DS,Reach-1,5
Up Type=0
Dn Type=3
Dn Slope=0.005
Boundary for River Rch & Prof#=Stream0280_DS,Reach-1,6
Up Type=0
Dn Type=3
Dn Slope=0.005
Boundary for River Rch & Prof#=Stream0280_DS,Reach-1,7
Up Type=0
Dn Type=3
Dn Slope=0.005

--- Stream0280_DS.g01 (geometry) ---

Geom Title=Existing Conditions

River Reach=Stream0280_DS,Reach-1
Reach XY= 30
      2114225.00     13907725.00      2114235.42     13907615.16
      2114318.93     13907533.15      2114388.21     13907511.37
      2114498.70     13907401.82      2114533.18     13907318.96
      2114619.16     13907227.29      2114631.14     13907172.83
      2114672.67     13907119.03      2114678.85     13907026.60
      2114722.65     13906969.03      2114728.86     13906876.60
      2114775.10     13906804.90      2114767.24     13906718.83
      2114628.61     13906573.50      2114622.64     13906480.98
      2114578.85     13906423.40      2114572.67     13906330.96
      2114531.15     13906277.15      2114519.27     13906222.45
      2114477.49     13906180.75      2114418.33     13906166.84
      2114382.69     13906128.67      2114424.33     13906059.85
      2114424.49     13905740.21      2114368.88     13905622.82
      2114328.67     13905573.43      2114324.21     13905535.09
      2114328.19     13905476.40      2114375.00     13905425.00

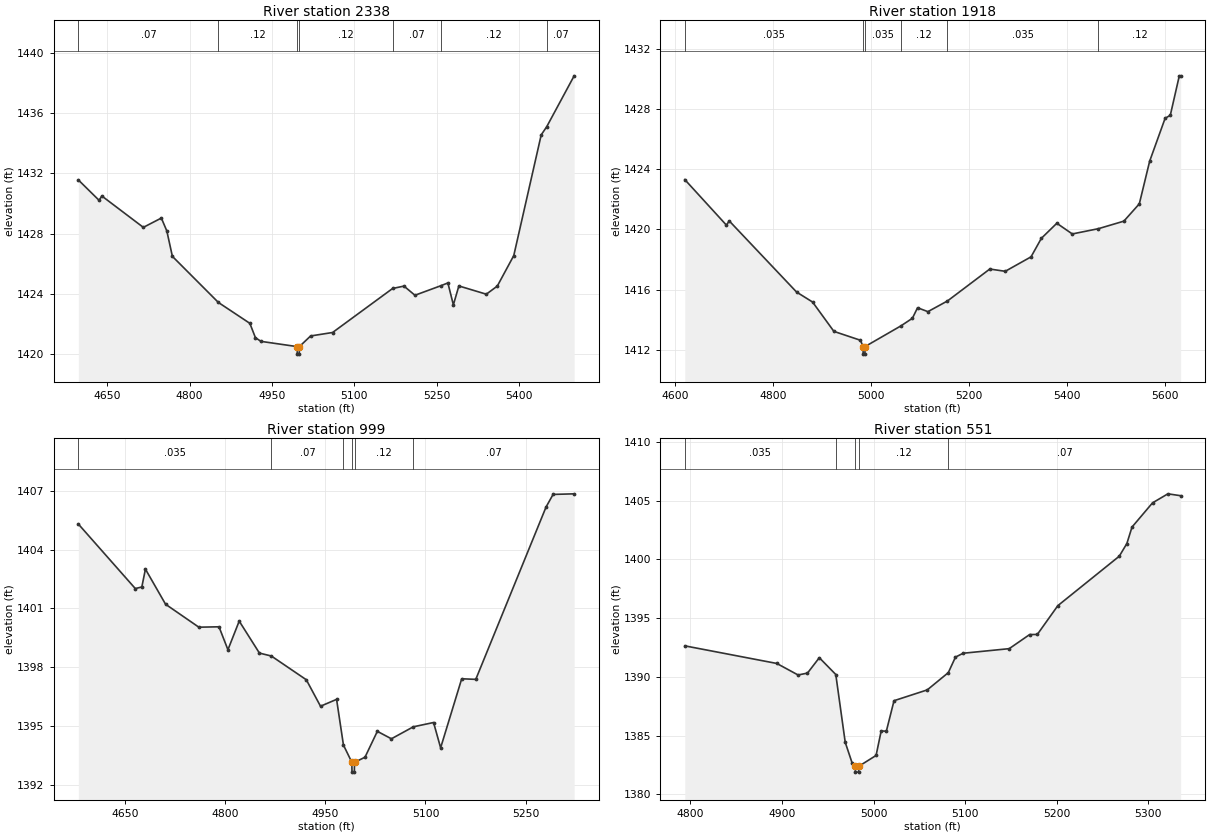
Type RM Length L Ch R = 1,2338,420,420,420
BEGIN DESCRIPTION:
Stream0280_DS 4.0
END DESCRIPTION:
XS GIS Cut Line= 3
      2114525.00     13907824.99      2114475.00     13907425.00
      2113975.00     13907425.00
#Sta/Elev= 30
  4597.2 1431.57  4635.0 1430.21  4640.0 1430.50  4715.6 1428.41  4748.4 1429.03
  4758.4 1428.17  4768.5 1426.48  4852.3 1423.41  4909.6 1422.02  4919.7 1421.07
  4929.8 1420.82  4995.8 1420.47  4996.0 1419.97  4999.5 1419.97  4999.8 1420.47
  5020.3 1421.18  5060.3 1421.41  5169.6 1424.34  5190.3 1424.50  5210.3 1423.89
  5257.9 1424.53  5270.3 1424.71  5280.3 1423.25  5290.3 1424.51  5340.3 1423.96
  5360.3 1424.50  5390.3 1426.53  5440.3 1434.57  5450.3 1435.11  5500.3 1438.50
#Mann=7,-1,0
  4597.2    0.07       0  4852.3    0.12       0  4995.8    0.05       0
  4999.8    0.12       0  5169.6    0.07       0  5257.9    0.12       0
  5450.3    0.07       0
Bank Sta=4995.8,4999.8
Exp/Cntr=0.3,0.1

Type RM Length L Ch R = 1,1918,919,919,919
BEGIN DESCRIPTION:
Stream0280_DS 3.0
END DESCRIPTION:
XS GIS Cut Line= 3
      2114825.01     13907425.02      2114675.00     13907075.00
      2114074.97     13907275.01
#Sta/Elev= 30
  4619.2 1423.30  4704.4 1420.27  4709.9 1420.56  4847.7 1415.83  4880.3 1415.17
  4923.9 1413.22  4978.2 1412.63  4983.5 1412.21  4983.8 1411.71  4987.3 1411.71
  4987.5 1412.21  5061.1 1413.59  5084.3 1414.09  5094.9 1414.79  5116.0 1414.53
  5156.0 1415.24  5242.5 1417.36  5274.1 1417.21  5326.8 1418.17  5347.9 1419.40
  5379.5 1420.40  5411.1 1419.69  5464.5 1420.04  5516.5 1420.54  5548.1 1421.69
  5569.2 1424.52  5600.8 1427.37  5611.4 1427.57  5629.8 1430.19  5632.5 1430.19
#Mann=6,-1,0
  4619.2   0.035       0  4983.5   0.035       0  4987.5   0.035       0
  5061.1    0.12       0  5156.0   0.035       0  5464.5    0.12       0
Bank Sta=4983.5,4987.5
Exp/Cntr=0.3,0.1

Type RM Length L Ch R = 1,999,448,448,448
BEGIN DESCRIPTION:
Stream0280_DS 2.0
END DESCRIPTION:
XS GIS Cut Line= 3
      2114925.00     13906425.00      2114525.00     13906275.00
      2114225.03     13906374.99
#Sta/Elev= 30
  4579.5 1405.30  4664.9 1402.01  4674.7 1402.09  4680.1 1403.00  4710.3 1401.21
  4760.2 1400.04  4790.4 1400.06  4803.8 1398.89  4820.7 1400.35  4851.0 1398.72
  4868.9 1398.57  4921.3 1397.36  4942.6 1396.01  4966.7 1396.36  4977.0 1394.03
  4989.6 1393.15  4989.8 1392.65  4993.3 1392.65  4993.6 1393.15  5009.3 1393.41
  5027.8 1394.73  5048.9 1394.35  5081.7 1394.96  5112.1 1395.18  5122.7 1393.89
  5154.3 1397.41  5175.4 1397.38  5280.8 1406.17  5291.3 1406.81  5322.9 1406.84
#Mann=6,-1,0
  4579.5   0.035       0  4868.9    0.07       0  4977.0    0.12       0
  4989.6    0.05       0  4993.6    0.12       0  5081.7    0.07       0
Bank Sta=4989.6,4993.6
Exp/Cntr=0.3,0.1

Type RM Length L Ch R = 1,551,0,0,0
BEGIN DESCRIPTION:
Stream0280_DS 1.0
END DESCRIPTION:
XS GIS Cut Line= 3
      2114624.98     13905974.99      2114425.00     13905925.00
      2114125.04     13906074.98
#Sta/Elev= 30
  4793.9 1392.64  4894.4 1391.14  4917.6 1390.16  4927.9 1390.32  4940.8 1391.63
  4958.8 1390.20  4969.1 1384.43  4976.8 1382.63  4980.0 1382.39  4980.2 1381.89
  4983.7 1381.89  4984.0 1382.39  5002.8 1383.31  5008.4 1385.40  5014.0 1385.37
  5022.4 1387.97  5058.7 1388.89  5081.7 1390.36  5089.5 1391.68  5097.9 1392.01
  5148.2 1392.40  5170.5 1393.60  5178.9 1393.61  5201.3 1396.06  5268.4 1400.27
  5276.7 1401.35  5282.3 1402.75  5304.7 1404.81  5321.5 1405.58  5335.4 1405.42
#Mann=5,-1,0
  4793.9   0.035       0  4958.8    0.12       0  4980.0    0.05       0
  4984.0    0.12       0  5081.7    0.07       0
Bank Sta=4980,4984
Exp/Cntr=0.3,0.1

Chan Stop Cuts=-1