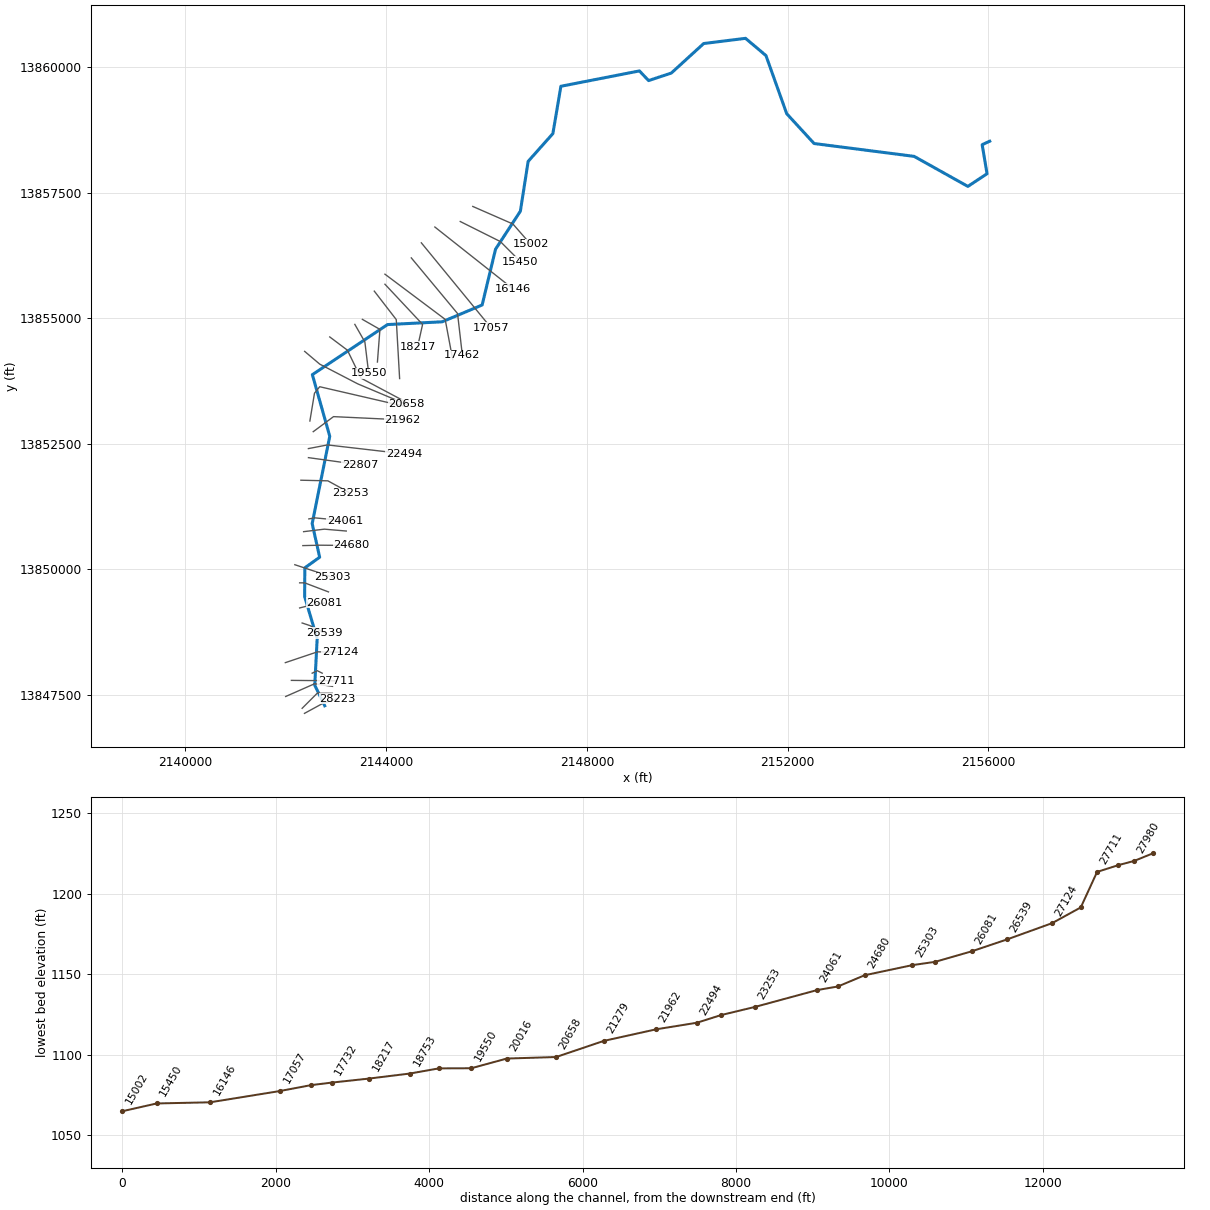
--- Swine Creek.prj (project) ---

Proj Title=Swine Creek Base Level Engineering
Current Plan=p01
Default Exp/Contr=0.3,0.1
English Units
Geom File=g01
Flow File=f01
Plan File=p01
Y Axis Title=Elevation
X Axis Title(PF)=Main Channel Distance
X Axis Title(XS)=Station
BEGIN DESCRIPTION:
Swine Creek
END DESCRIPTION:
DSS Export Rating Curves= 0
DSS Export Rating Curve Sorted= 0
DSS Export Volume Flow Curves= 0
DXF OffsetX= 0
DXF OffsetY= 0
DXF ScaleX= 1
DXF ScaleY= 10

--- Swine Creek.p01 (plan) ---

Plan Title=Multiple Run
Short Identifier=Multiple
Geom File=g01
Flow File=f01
Subcritical Flow
K Sum by GR= 0
Std Step Tol= 0.01
Critical Tol= 0.01
Num of Std Step Trials= 20
Max Error Tol= 0.3
Flow Tol Ratio= 0.001
Split Flow NTrial= 30
Split Flow Tol= 0.02
Split Flow Ratio= 0.02
Log Output Level= 0
Friction Slope Method= 1
Unsteady Friction Slope Method= 2
Unsteady Bridges Friction Slope Method= 1
Parabolic Critical Depth
Global Vel Dist=  1 , 1 , 1
Global Log Level= 0
CheckData=True
Encroach Param= -1, 0, 0, 0
BEGIN DESCRIPTION:
Multiple Run
END DESCRIPTION:

--- Swine Creek.f01 (steady flow) ---

Flow Title=Multiple
Program Version=4.10
Number of Profiles= 7
Profile Names=10-year,25-year,50-year,1pct_min,100-year,1pct_plu,500-year
River Rch & RM=Swine Creek,Reach-1         ,28223
     710    1175    1609    1070    2134    4259    3711
River Rch & RM=Swine Creek,Reach-1         ,26539
     831    1392    1921    1286    2565    5118    4525
River Rch & RM=Swine Creek,Reach-1         ,23253
    1665    2905    4118    2824    5635   11244   10452
River Rch & RM=Swine Creek,Reach-1         ,20658
    3271    5853    8434    5863   11698   23340   22305
River Rch & RM=Swine Creek,Reach-1         ,12248
    4068    7321   10586    7379   14724   29377   28231
River Rch & RM=Swine Creek,Reach-1         ,4415
    5244    9534   13882    9736   19427   38762   37713
Boundary for River Rch & Prof#=Swine Creek,Reach-1         , 1
Up Type= 0
Dn Type= 3
Dn Slope=0.01
Boundary for River Rch & Prof#=Swine Creek,Reach-1         , 2
Up Type= 0
Dn Type= 3
Dn Slope=0.01
Boundary for River Rch & Prof#=Swine Creek,Reach-1         , 3
Up Type= 0
Dn Type= 3
Dn Slope=0.01
Boundary for River Rch & Prof#=Swine Creek,Reach-1         , 4
Up Type= 0
Dn Type= 3
Dn Slope=0.01
Boundary for River Rch & Prof#=Swine Creek,Reach-1         , 5
Up Type= 0
Dn Type= 3
Dn Slope=0.01
Boundary for River Rch & Prof#=Swine Creek,Reach-1         , 6
Up Type= 0
Dn Type= 3
Dn Slope=0.01
Boundary for River Rch & Prof#=Swine Creek,Reach-1         , 7
Up Type= 0
Dn Type= 3
Dn Slope=0.01
DSS Import GetInterval= 0
DSS Import GetPeak= 0
DSS Import FillOption= 0

--- Swine Creek.g01 (geometry) ---

Geom Title=Existing Conditions
Program Version=4.10

River Reach=Swine Creek     ,Reach-1
Reach XY= 30
        2142775.       13847275.      2142576.21     13847685.51
      2142624.46     13848611.14      2142374.71     13849452.15
      2142378.45     13850023.75      2142673.96     13850235.43
      2142525.07     13850904.97      2142875.28     13852645.18
       2142528.6     13853873.51      2144026.58     13854871.18
      2145115.34     13854926.38      2145911.77     13855261.33
      2146178.82     13856373.42       2146673.3     13857130.64
      2146828.53     13858123.55      2147321.18     13858676.58
      2147480.62     13859619.38      2149045.28     13859925.39
      2149228.32      13859732.6      2149681.19     13859882.82
      2150326.55     13860471.25      2151159.84     13860574.61
      2151566.86     13860231.06      2151980.47     13859072.55
      2152526.47     13858478.54      2154519.14     13858222.94
      2155590.06     13857624.29      2155971.87     13857876.63
      2155874.91     13858455.13        2156025.       13858525.

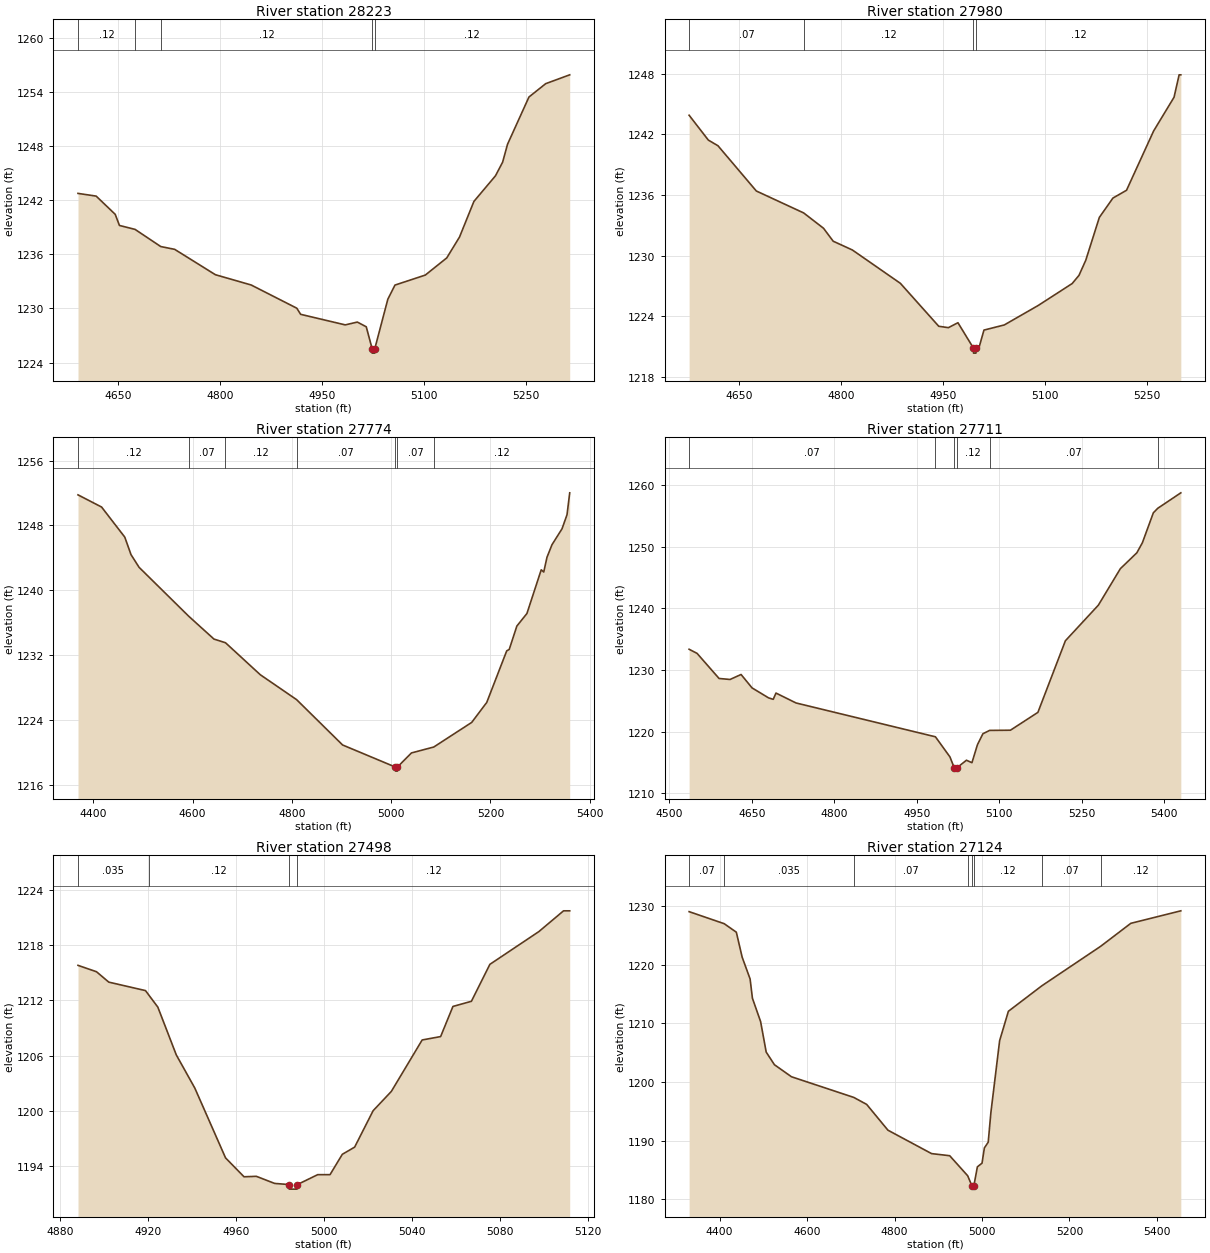
Type RM Length L Ch R = 1 ,28223   ,243,243,243
BEGIN DESCRIPTION:
Swine Creek 58.0
END DESCRIPTION:
XS GIS Cut Line= 3
      2142371.53     13847124.05      2142724.11     13847316.26
      2143028.42     13847418.51
#Sta/Elev= 30
  4591.1 1242.75  4617.8 1242.45  4645.8 1240.43    4652  1239.2    4675 1238.76
  4712.7 1236.86  4733.2 1236.55    4793 1233.74  4845.6  1232.6  4912.6 1230.03
  4918.3 1229.35  4983.8 1228.18  5001.6 1228.49  5014.7 1227.97  5023.3 1225.55
  5023.5 1225.05    5027 1225.05  5027.3 1225.55  5046.4 1231.02  5056.9 1232.59
  5101.5  1233.7    5133  1235.6  5151.8 1237.92  5172.9 1241.86  5204.6  1244.7
  5215.1 1246.21  5222.3 1248.19  5253.8 1253.43  5278.4 1254.91  5313.7 1255.89
#Mann= 5 ,-1 , 0
  4591.1     .12       0    4675     .07       0  4712.7     .12       0
  5023.3     .05       0  5027.3     .12       0
Bank Sta=5023.3,5027.3
XS Rating Curve= 0 ,0
Exp/Cntr=0.3,0.1

Type RM Length L Ch R = 1 ,27980   ,206,206,206
BEGIN DESCRIPTION:
Swine Creek 57.0
END DESCRIPTION:
XS GIS Cut Line= 3
      2142324.96     13847224.96        2142625.       13847525.
      2142924.99       13847525.
#Sta/Elev= 30
  4576.1  1243.9  4604.4 1241.44  4618.6 1240.88  4675.1  1236.4  4744.8 1234.23
  4774.1 1232.71  4788.3 1231.43  4816.6 1230.56  4887.3 1227.26  4943.8 1223.01
    4958 1222.87  4972.1 1223.36  4994.9 1220.85  4995.1 1220.35  4998.6 1220.35
  4998.9 1220.85  5002.9 1220.85  5010.4 1222.63  5040.4 1223.14  5090.4 1225.07
  5140.4 1227.24  5150.4 1228.05  5160.4 1229.55  5180.4 1233.79  5200.4  1235.7
  5220.4 1236.47  5260.4 1242.35  5290.4 1245.68  5297.9  1247.9  5300.4  1247.9
#Mann= 4 ,-1 , 0
  4576.1     .07       0  4744.8     .12       0  4994.9     .05       0
  4998.9     .12       0
Bank Sta=4994.9,4998.9
XS Rating Curve= 0 ,0
Exp/Cntr=0.3,0.1

Type RM Length L Ch R = 1 ,27774   ,276,276,276
BEGIN DESCRIPTION:
Swine Creek 56.5
END DESCRIPTION:
XS GIS Cut Line= 3
      2141997.24     13847460.51       2142574.5     13847714.83
      2142930.32     13847662.12
#Sta/Elev= 30
  4369.2 1251.77  4416.7 1250.27  4463.4 1246.57    4476 1244.41  4492.2 1242.85
  4592.3 1236.82  4643.1 1234.01  4666.3 1233.56  4736.4 1229.62  4809.6 1226.55
  4902.2 1220.97  5008.6 1218.25  5008.9 1217.75  5012.4 1217.75  5012.6 1218.25
  5040.9 1219.99  5085.9 1220.72  5162.3 1223.75  5192.6 1226.21  5232.8 1232.56
  5237.9 1232.74  5253.2 1235.61  5273.5 1237.16  5302.3 1242.54  5307.4 1242.27
  5313.9 1244.08    5324 1245.63  5344.2 1247.59  5354.3 1249.33  5359.7 1252.02
#Mann= 7 ,-1 , 0
  4369.2     .12       0  4592.3     .07       0  4666.3     .12       0
  4809.6     .07       0  5008.6     .05       0  5012.6     .07       0
  5085.9     .12       0
Bank Sta=5008.6,5012.6
XS Rating Curve= 0 ,0
Exp/Cntr=0.3,0.1

Type RM Length L Ch R = 1 ,27711   ,213,213,213
BEGIN DESCRIPTION:
Swine Creek 56.3
END DESCRIPTION:
XS GIS Cut Line= 2
      2142110.54     13847781.39        2143005.     13847773.47
#Sta/Elev= 30
    4536 1233.37  4550.5  1232.7  4590.5 1228.62  4610.5 1228.46  4630.5 1229.27
  4650.5 1227.09  4680.5 1225.47    4689 1225.23    4694 1226.25  4730.5 1224.64
  4984.1 1219.14  5010.5 1215.87  5018.5 1214.06  5018.7 1213.56  5022.5 1214.06
  5040.5 1215.33  5050.5 1214.93  5060.5 1217.85  5070.5 1219.64  5082.7 1220.18
  5120.5 1220.21  5170.5 1223.11  5220.5 1234.75  5280.5 1240.54  5320.5 1246.47
  5350.5 1249.05  5360.5 1250.67  5380.5 1255.55  5388.6 1256.29  5430.5  1258.8
#Mann= 6 ,-1 , 0
    4536     .07       0  4984.1     .12       0  5018.5     .05       0
  5022.5     .12       0  5082.7     .07       0  5388.6     .12       0
Bank Sta=5018.5,5022.5
XS Rating Curve= 0 ,0
Exp/Cntr=0.3,0.1

Type RM Length L Ch R = 1 ,27498   ,374,374,374
BEGIN DESCRIPTION:
Swine Creek 56.0
END DESCRIPTION:
XS GIS Cut Line= 3
        2142525.       13847925.        2142625.       13847975.
        2142725.       13847925.
#Sta/Elev= 30
  4888.1 1215.81  4896.5 1215.12  4902.1 1213.99  4918.8 1213.07  4920.2 1212.62
  4924.4 1211.28  4932.8 1206.09  4941.2  1202.5  4955.2 1194.91  4963.6 1192.86
  4969.2 1192.91  4977.5 1192.14  4983.9 1192.02  4984.2 1191.52  4987.7 1191.52
  4987.9 1192.02  4997.1 1193.09  5002.7 1193.09  5008.3  1195.3  5013.9 1196.08
  5022.3 1200.03  5030.6 1202.13  5044.6 1207.71    5053 1208.08  5058.6 1211.35
    5067 1211.91  5075.4 1215.92  5097.7 1219.48  5108.9 1221.73  5111.7 1221.73
#Mann= 4 ,-1 , 0
  4888.1    .035       0  4920.2     .12       0  4983.9     .05       0
  4987.9     .12       0
Bank Sta=4983.9,4987.9
XS Rating Curve= 0 ,0
Exp/Cntr=0.3,0.1

Type RM Length L Ch R = 1 ,27124   ,585,585,585
BEGIN DESCRIPTION:
Swine Creek 55.0
END DESCRIPTION:
XS GIS Cut Line= 3
      2141990.02     13848134.79      2142630.58     13848350.09
      2143079.37      13848344.3
#Sta/Elev= 30
  4330.1 1229.01  4410.3 1226.96  4438.1 1225.51  4451.4 1221.26  4469.6 1217.54
  4474.9 1214.26  4493.6 1210.29  4506.4 1205.09  4525.2 1202.94  4564.2 1200.89
  4706.7 1197.37  4736.2 1196.18  4784.8 1191.79  4884.6  1187.8  4926.1 1187.44
  4967.3 1184.02  4977.2 1182.25  4977.4 1181.75  4981.2 1182.25  4989.4 1185.55
    5000 1186.17  5005.4 1188.77  5014.2 1189.75  5020.3  1194.8  5040.3 1207.04
  5060.3 1212.04  5136.8 1216.38  5271.4 1223.11  5340.3 1227.02  5454.7 1229.15
#Mann= 8 ,-1 , 0
  4330.1     .07       0  4410.3    .035       0  4706.7     .07       0
  4967.3     .12       0  4977.2     .05       0  4981.2     .12       0
  5136.8     .07       0  5271.4     .12       0
Bank Sta=4977.2,4981.2
XS Rating Curve= 0 ,0
Exp/Cntr=0.3,0.1

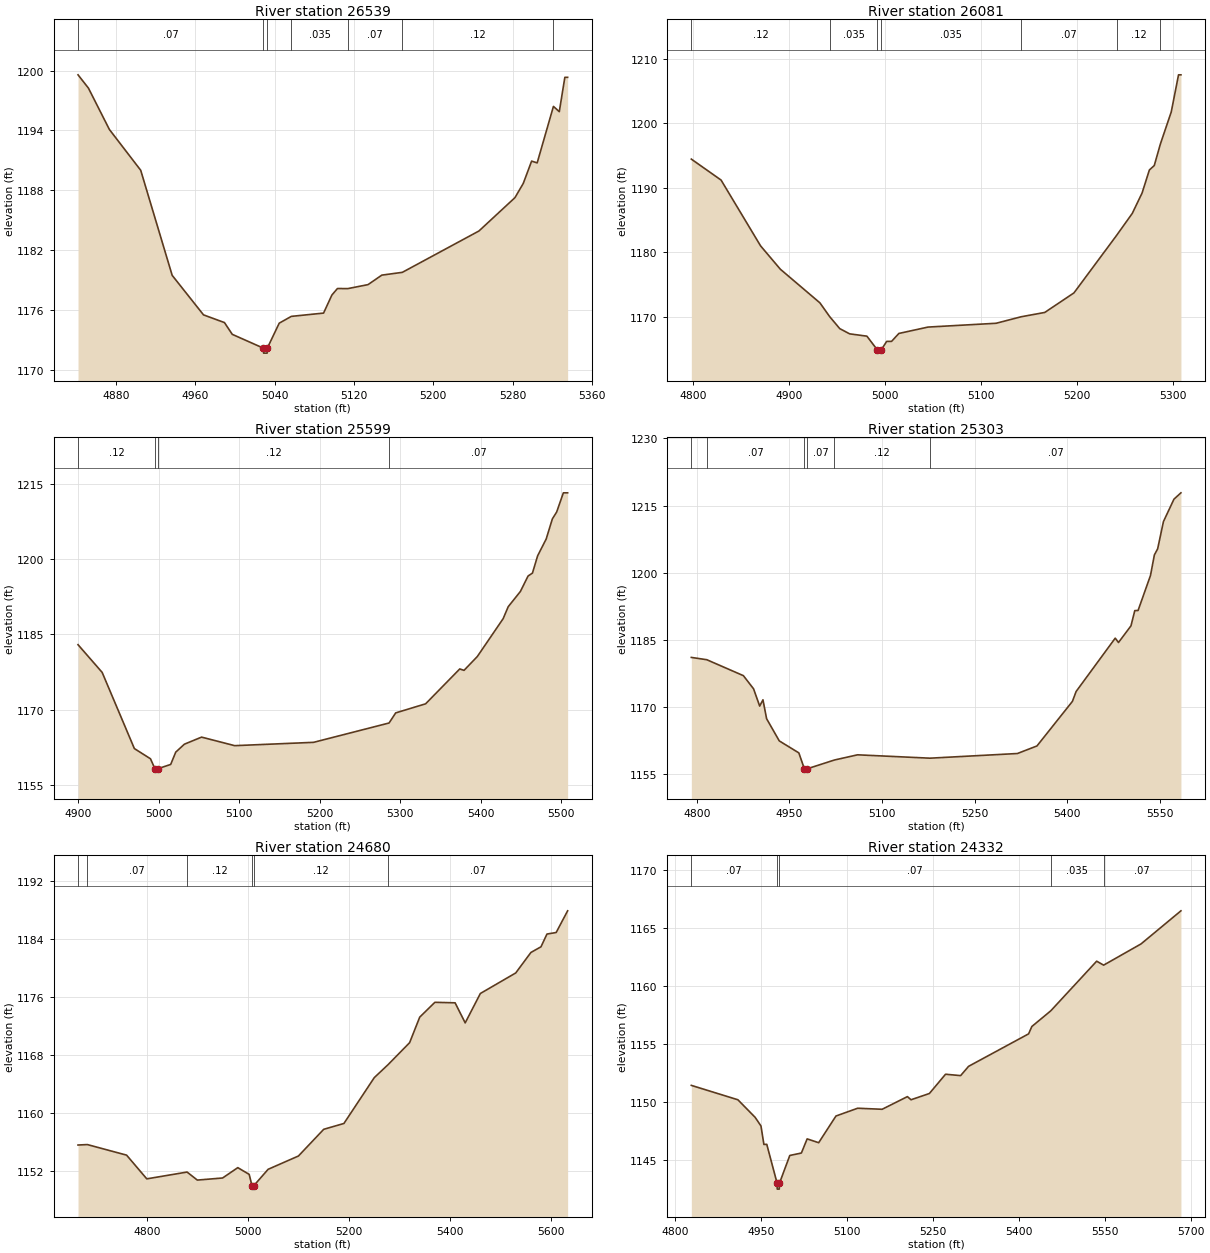
Type RM Length L Ch R = 1 ,26539   ,458,458,458
BEGIN DESCRIPTION:
Swine Creek 54.0
END DESCRIPTION:
XS GIS Cut Line= 3
      2142325.01       13848925.        2142475.       13848875.
      2142774.99       13848725.
#Sta/Elev= 30
  4841.9 1199.57  4852.4 1198.24  4873.5  1194.1  4905.1 1190.01  4936.8 1179.49
  4968.4 1175.53  4989.5 1174.76  4997.4 1173.58  5028.7  1172.2    5029  1171.7
  5032.5  1171.7  5032.7  1172.2  5044.7  1174.7  5056.9 1175.38  5089.4 1175.71
  5097.8 1177.52  5103.4 1178.17  5113.8 1178.16  5134.2 1178.56  5148.1 1179.51
  5168.8 1179.79    5246 1183.93  5282.3 1187.27  5290.7  1188.7  5299.1 1190.93
  5304.7 1190.75  5321.1 1196.41    5327 1195.88  5332.6 1199.32  5335.4 1199.32
#Mann= 7 ,-1 , 0
  4841.9     .07       0  5028.7     .05       0  5032.7     .07       0
  5056.9    .035       0  5113.8     .07       0  5168.8     .12       0
  5321.1     .07       0
Bank Sta=5028.7,5032.7
XS Rating Curve= 0 ,0
Exp/Cntr=0.3,0.1

Type RM Length L Ch R = 1 ,26081   ,482,482,482
BEGIN DESCRIPTION:
Swine Creek 53.0
END DESCRIPTION:
XS GIS Cut Line= 3
      2142274.96     13849224.99        2142475.       13849275.
      2142774.97     13849324.99
#Sta/Elev= 30
  4798.4 1194.44  4829.4 1191.19  4870.6 1180.98  4891.2 1177.36  4932.4 1172.15
  4942.6 1170.01  4953.1 1168.15  4963.4 1167.34  4981.4 1166.98  4992.3 1164.85
  4992.5 1164.35    4996 1164.35  4996.3 1164.85    5002 1166.17  5007.1 1166.17
  5014.7  1167.4  5045.1 1168.39  5116.1 1168.98  5142.2 1169.99  5166.8 1170.66
  5197.2 1173.69  5241.6  1182.6    5258 1186.02  5268.2 1189.18  5275.8 1192.75
  5280.9 1193.44  5287.3 1196.79  5298.6 1201.75  5306.2 1207.51  5308.7 1207.51
#Mann= 7 ,-1 , 0
  4798.4     .12       0  4942.6    .035       0  4992.3    .035       0
  4996.3    .035       0  5142.2     .07       0  5241.6     .12       0
  5287.3     .07       0
Bank Sta=4992.3,4996.3
XS Rating Curve= 0 ,0
Exp/Cntr=0.3,0.1

Type RM Length L Ch R = 1 ,25599   ,296,296,296
BEGIN DESCRIPTION:
Swine Creek 52.0
END DESCRIPTION:
XS GIS Cut Line= 3
      2142274.98       13849725.        2142375.       13849725.
      2142849.88     13849544.06
#Sta/Elev= 30
    4900 1182.92    4930  1177.4    4970 1162.24    4990 1160.21  4995.5 1158.25
  4995.8 1157.75  4999.5 1158.25  5015.1 1159.08  5021.4 1161.53  5032.1 1163.11
  5053.5 1164.52  5094.6 1162.82  5192.6 1163.48  5286.4 1167.33  5294.6 1169.34
  5331.8 1171.15  5374.2 1178.09  5379.5 1177.81    5396 1180.56  5428.1  1188.1
  5434.4 1190.48  5449.5 1193.51  5459.1  1196.6  5464.5 1197.17  5470.9  1200.6
  5481.6 1203.97  5489.2 1207.95  5494.6 1209.34  5502.9 1213.15  5508.2 1213.15
#Mann= 4 ,-1 , 0
    4900     .12       0  4995.5     .05       0  4999.5     .12       0
  5286.4     .07       0
Bank Sta=4995.5,4999.5
XS Rating Curve= 0 ,0
Exp/Cntr=0.3,0.1

Type RM Length L Ch R = 1 ,25303   ,623,623,623
BEGIN DESCRIPTION:
Swine Creek 51.0
END DESCRIPTION:
XS GIS Cut Line= 2
      2142179.29     13850086.28      2142931.82     13849836.82
#Sta/Elev= 30
  4791.3 1181.09  4816.3 1180.58  4875.6 1177.02  4892.1 1174.08    4902 1170.23
  4907.3 1171.63  4913.2 1167.41  4933.7 1162.46  4965.4 1159.78  4974.4 1156.21
  4974.7 1155.71  4978.4 1156.21    5023 1158.19  5060.5 1159.35  5177.7  1158.6
  5319.3 1159.64    5351 1161.33  5408.4 1171.28  5414.4 1173.49  5477.7 1185.39
    5483 1184.42  5503.2 1188.14  5509.4 1191.54  5514.7 1191.57  5534.8 1199.38
  5541.1 1203.97  5546.4 1205.33  5555.8 1211.42  5572.8 1216.41  5584.1 1217.83
#Mann= 6 ,-1 , 0
  4791.3    .035       0  4816.3     .07       0  4974.4     .05       0
  4978.4     .07       0    5023     .12       0  5177.7     .07       0
Bank Sta=4974.4,4978.4
XS Rating Curve= 0 ,0
Exp/Cntr=0.3,0.1

Type RM Length L Ch R = 1 ,24680   ,348,348,348
BEGIN DESCRIPTION:
Swine Creek 50.0
END DESCRIPTION:
XS GIS Cut Line= 3
      2142338.93     13850467.02        2142675.       13850475.
      2143307.72     13850469.63
#Sta/Elev= 30
  4663.4 1155.53  4681.9 1155.59  4759.5 1154.13  4799.5 1150.85  4879.2 1151.79
  4899.5 1150.68  4949.5 1150.97  4979.6  1152.4  5002.1 1151.47  5007.6 1149.93
  5007.8 1149.43  5011.6 1149.93  5039.6 1152.17  5099.6 1154.01  5149.6  1157.7
  5189.6 1158.51  5249.6 1164.84  5276.8 1166.63  5319.6 1169.68  5339.6 1173.21
  5369.6 1175.26  5409.6 1175.19  5429.6 1172.42  5459.6 1176.48  5529.6 1179.32
  5559.6 1182.15  5579.6 1182.94  5591.4  1184.7  5609.6 1184.91  5632.3 1187.91
#Mann= 6 ,-1 , 0
  4663.4    .035       0  4681.9     .07       0  4879.2     .12       0
  5007.6     .05       0  5011.6     .12       0  5276.8     .07       0
Bank Sta=5007.6,5011.6
XS Rating Curve= 0 ,0
Exp/Cntr=0.3,0.1

Type RM Length L Ch R = 1 ,24332   ,271,271,271
BEGIN DESCRIPTION:
Swine Creek 49.0
END DESCRIPTION:
XS GIS Cut Line= 3
      2142354.32     13850744.75      2142766.85     13850794.75
      2143204.39     13850757.25
#Sta/Elev= 30
  4828.2  1151.4  4909.5 1150.16  4939.7 1148.64  4949.8  1147.9  4954.9 1146.31
  4959.9 1146.32    4978 1142.96  4978.2 1142.46  4981.7 1142.46    4982 1142.96
  5000.1 1145.36  5020.3 1145.57  5030.4 1146.79  5050.5 1146.46  5080.7 1148.76
  5118.6 1149.43  5161.3 1149.34  5205.4 1150.43  5211.7 1150.16  5243.8  1150.7
    5272 1152.36  5298.3 1152.24  5312.2 1153.04    5417 1155.84  5422.6 1156.47
  5455.8 1157.83  5535.8  1162.1    5548 1161.76  5613.3 1163.59  5682.9 1166.44
#Mann= 5 ,-1 , 0
  4828.2     .07       0    4978     .05       0    4982     .07       0
  5455.8    .035       0    5548     .07       0
Bank Sta=4978,4982
XS Rating Curve= 0 ,0
Exp/Cntr=0.3,0.1

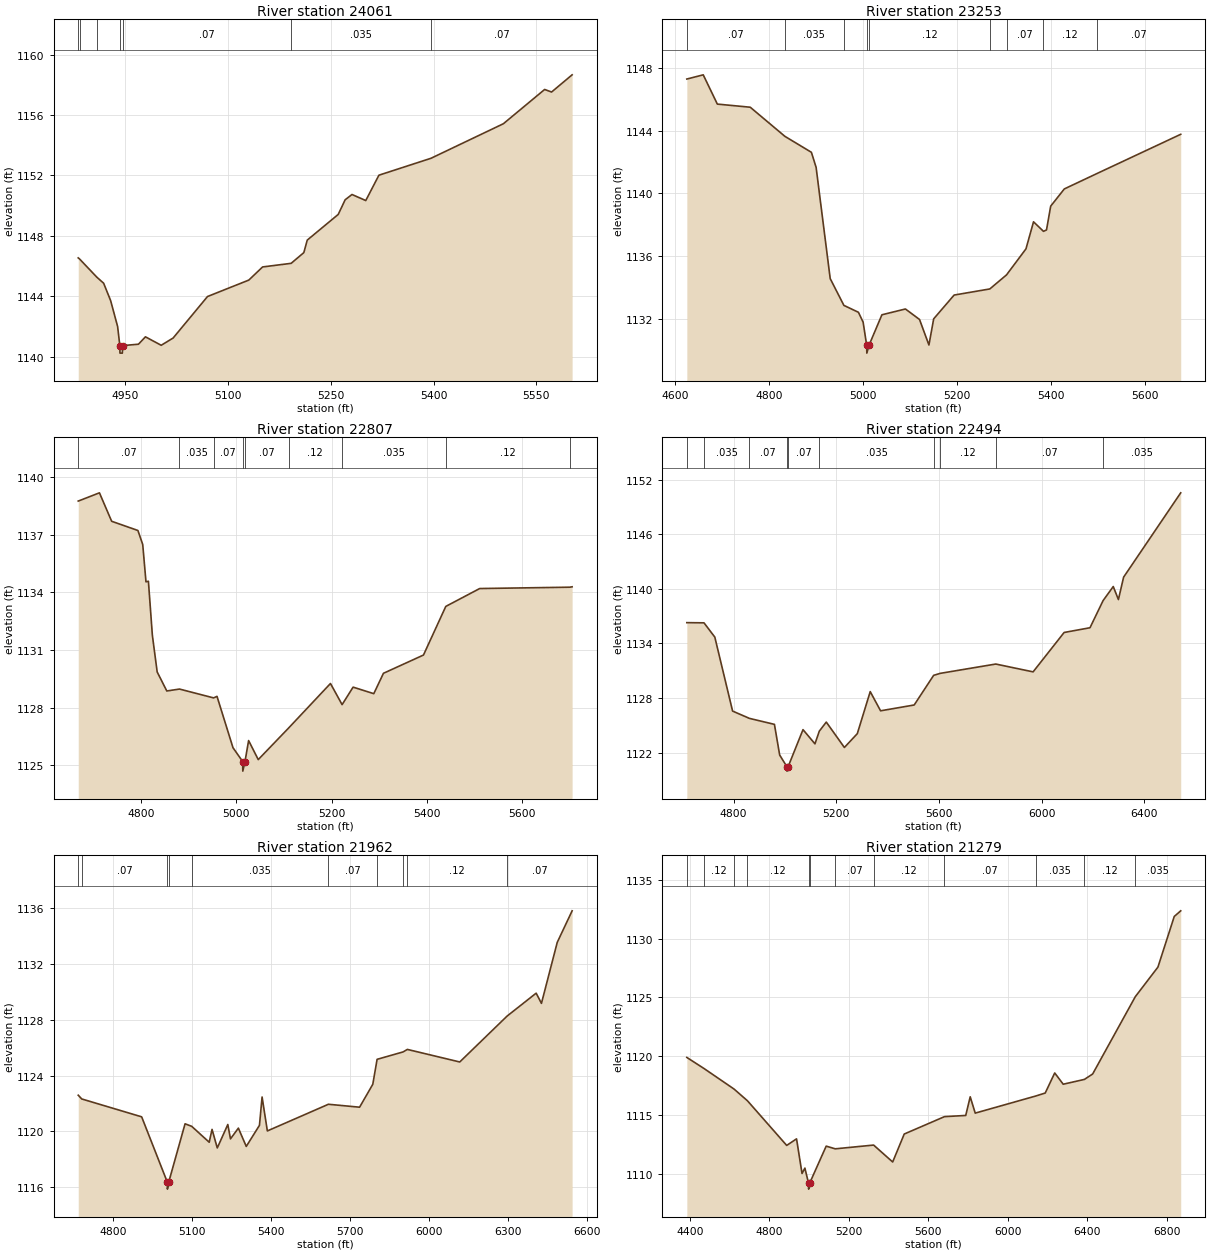
Type RM Length L Ch R = 1 ,24061   ,808,808,808
BEGIN DESCRIPTION:
Swine Creek 48.0
END DESCRIPTION:
XS GIS Cut Line= 3
      2142458.43     13850998.95      2142575.38     13851019.84
      2143174.92     13850964.42
#Sta/Elev= 30
  4881.2 1146.54  4883.1 1146.47  4908.2 1145.27  4918.3 1144.86  4928.5 1143.71
  4938.7 1141.99  4941.9 1140.73  4942.1 1140.23  4945.6 1140.23  4945.9 1140.73
  4969.1 1140.82  4979.3 1141.31  5002.3 1140.75  5019.7 1141.23  5069.9 1143.98
  5130.2 1145.07  5150.3 1145.94    5192 1146.18  5210.5 1146.89  5215.5 1147.72
  5260.7 1149.42  5270.8 1150.39  5280.8 1150.74  5300.9 1150.34  5320.1 1152.02
  5396.1 1153.14  5501.8 1155.43    5562  1157.7  5572.1 1157.53  5602.1 1158.67
#Mann= 7 ,-1 , 0
  4881.2     .07       0  4883.1    .035       0  4908.2     .07       0
  4941.9     .05       0  4945.9     .07       0    5192    .035       0
  5396.1     .07       0
Bank Sta=4941.9,4945.9
XS Rating Curve= 0 ,0
Exp/Cntr=0.3,0.1

Type RM Length L Ch R = 1 ,23253   ,446,446,446
BEGIN DESCRIPTION:
Swine Creek 47.0
END DESCRIPTION:
XS GIS Cut Line= 3
      2142300.09     13851769.93       2142837.7     13851757.43
      2143287.77     13851511.56
#Sta/Elev= 30
  4625.7 1147.31  4660.6 1147.58  4690.6 1145.71  4760.6 1145.51  4834.3 1143.65
  4890.7 1142.63  4900.7 1141.67  4930.7 1134.56  4959.8 1132.85  4990.7 1132.41
  5000.7 1131.78  5008.3  1130.3  5008.6  1129.8  5013.2  1130.3  5040.7 1132.25
  5090.7 1132.62  5120.7 1131.95  5140.7 1130.32  5150.8 1131.99  5194.3 1133.51
  5270.2  1133.9  5305.8  1134.8  5347.1 1136.46  5363.2 1138.19  5384.4 1137.58
  5390.8 1137.67  5399.7 1139.19  5428.7 1140.29  5498.6 1141.28  5676.3 1143.78
#Mann= 9 ,-1 , 0
  4625.7     .07       0  4834.3    .035       0  4959.8     .12       0
  5008.3     .05       0  5013.2     .12       0  5270.2    .035       0
  5305.8     .07       0  5384.4     .12       0  5498.6     .07       0
Bank Sta=5008.3,5013.2
XS Rating Curve= 0 ,0
Exp/Cntr=0.3,0.1

Type RM Length L Ch R = 1 ,22807   ,313,313,313
BEGIN DESCRIPTION:
Swine Creek 46.0
END DESCRIPTION:
XS GIS Cut Line= 3
      2142450.95     13852219.63        2142775.       13852175.
        2143477.      13852076.4
#Sta/Elev= 30
  4668.5 1138.74    4713 1139.17  4738.6 1137.69  4793.7 1137.21  4803.8 1136.48
  4810.6 1134.54  4815.7 1134.57    4824 1131.76  4834.1 1129.85  4854.3 1128.86
  4880.9 1128.96  4952.5  1128.5  4959.6 1128.58  4993.1 1125.91  5013.4 1125.19
  5013.7 1124.69  5018.3 1125.19  5025.9 1126.28  5046.1 1125.29  5109.7 1126.93
  5197.6 1129.25    5222 1128.15  5245.1 1129.06  5288.5 1128.72  5308.7 1129.78
  5392.7 1130.73  5439.5 1133.26  5510.6 1134.19  5699.7 1134.26  5704.5 1134.28
#Mann= 9 ,-1 , 0
  4668.5     .07       0  4880.9    .035       0  4952.5     .07       0
  5013.4     .05       0  5018.3     .07       0  5109.7     .12       0
    5222    .035       0  5439.5     .12       0  5699.7     .07       0
Bank Sta=5013.4,5018.3
XS Rating Curve= 0 ,0
Exp/Cntr=0.3,0.1

Type RM Length L Ch R = 1 ,22494   ,532,532,532
BEGIN DESCRIPTION:
Swine Creek 45.0
END DESCRIPTION:
XS GIS Cut Line= 3
        2142450.       13852400.      2142829.73     13852473.03
      2144355.96     13852296.47
#Sta/Elev= 30
  4618.2 1136.28  4685.1 1136.26  4727.2 1134.69  4796.4 1126.56  4861.8 1125.76
  4959.3  1125.1  4979.7 1121.73  5007.5 1120.46  5007.9 1119.96  5012.8 1120.46
  5070.6 1124.52  5117.1 1122.96    5134 1124.35  5161.2 1125.35  5231.7 1122.56
    5282 1124.08  5332.3  1128.7  5372.6 1126.59  5503.5 1127.23  5579.3 1130.49
  5605.5 1130.71  5821.2 1131.73  5966.5 1130.87  6087.3  1135.2    6188 1135.72
    6239  1138.7  6278.6 1140.25  6298.7 1138.82  6318.9 1141.28  6541.3 1150.55
#Mann= 10 ,-1 , 0
  4618.2     .07       0  4685.1    .035       0  4861.8     .07       0
  5007.5     .05       0  5012.8     .07       0    5134    .035       0
  5579.3     .07       0  5605.5     .12       0  5821.2     .07       0
    6239    .035       0
Bank Sta=5007.5,5012.8
XS Rating Curve= 0 ,0
Exp/Cntr=0.3,0.1

Type RM Length L Ch R = 1 ,21962   ,683,683,683
BEGIN DESCRIPTION:
Swine Creek 44.0
END DESCRIPTION:
XS GIS Cut Line= 3
      2142546.01      13852736.8      2142950.22     13853036.83
      2144321.41     13852972.46
#Sta/Elev= 30
  4666.2  1122.6  4679.6 1122.33  4907.1 1121.05  5004.6 1116.37    5005 1115.87
  5009.9 1116.37    5072 1120.55  5097.2 1120.37  5163.7 1119.23  5174.5 1120.15
  5194.4 1118.82  5234.4  1120.5  5244.5 1119.47  5274.5 1120.24  5304.5 1118.93
  5354.6 1120.44  5364.6 1122.47  5384.6 1120.04  5616.6 1121.95    5735 1121.74
  5785.1 1123.38  5801.5 1125.17  5900.2  1125.7  5916.5 1125.88  6115.4 1124.98
  6295.4 1128.27  6405.7 1129.91  6425.8 1129.18  6485.8 1133.55  6542.3 1135.81
#Mann= 10 ,-1 , 0
  4666.2     .12       0  4679.6     .07       0  5004.6     .05       0
  5009.9     .07       0  5097.2    .035       0  5616.6     .07       0
  5801.5     .12       0  5900.2     .07       0  5916.5     .12       0
  6295.4     .07       0
Bank Sta=5004.6,5009.9
XS Rating Curve= 0 ,0
Exp/Cntr=0.3,0.1

Type RM Length L Ch R = 1 ,21279   ,621,621,621
BEGIN DESCRIPTION:
Swine Creek 43.0
END DESCRIPTION:
XS GIS Cut Line= 4
       2142479.3     13852949.33      2142570.98     13853503.59
      2142675.17     13853632.78      2144386.66     13853237.03
#Sta/Elev= 30
  4384.7 1119.89  4470.9 1118.95  4622.1  1117.2  4689.7  1116.2  4887.1  1112.4
  4936.6 1112.96  4964.2 1110.01  4978.6 1110.47    4997 1109.18  4997.4 1108.68
  5002.4 1109.18  5085.7 1112.34  5131.3 1112.11  5324.3 1112.43  5420.2 1110.99
  5478.3 1113.37  5680.8 1114.85  5787.6 1114.95  5810.2 1116.54  5835.4 1115.15
  6140.7 1116.61  6187.5 1116.86  6235.3 1118.57    6278 1117.61  6384.7 1118.02
  6426.1 1118.48  6640.6 1125.06  6754.5 1127.58  6836.6 1131.89  6869.1 1132.37
#Mann= 12 ,-1 , 0
  4384.7     .07       0  4470.9     .12       0  4622.1     .07       0
  4689.7     .12       0    4997     .05       0  5002.4     .12       0
  5131.3     .07       0  5324.3     .12       0  5680.8     .07       0
  6140.7    .035       0  6384.7     .12       0  6640.6    .035       0
Bank Sta=4997,5002.4
XS Rating Curve= 0 ,0
Exp/Cntr=0.3,0.1

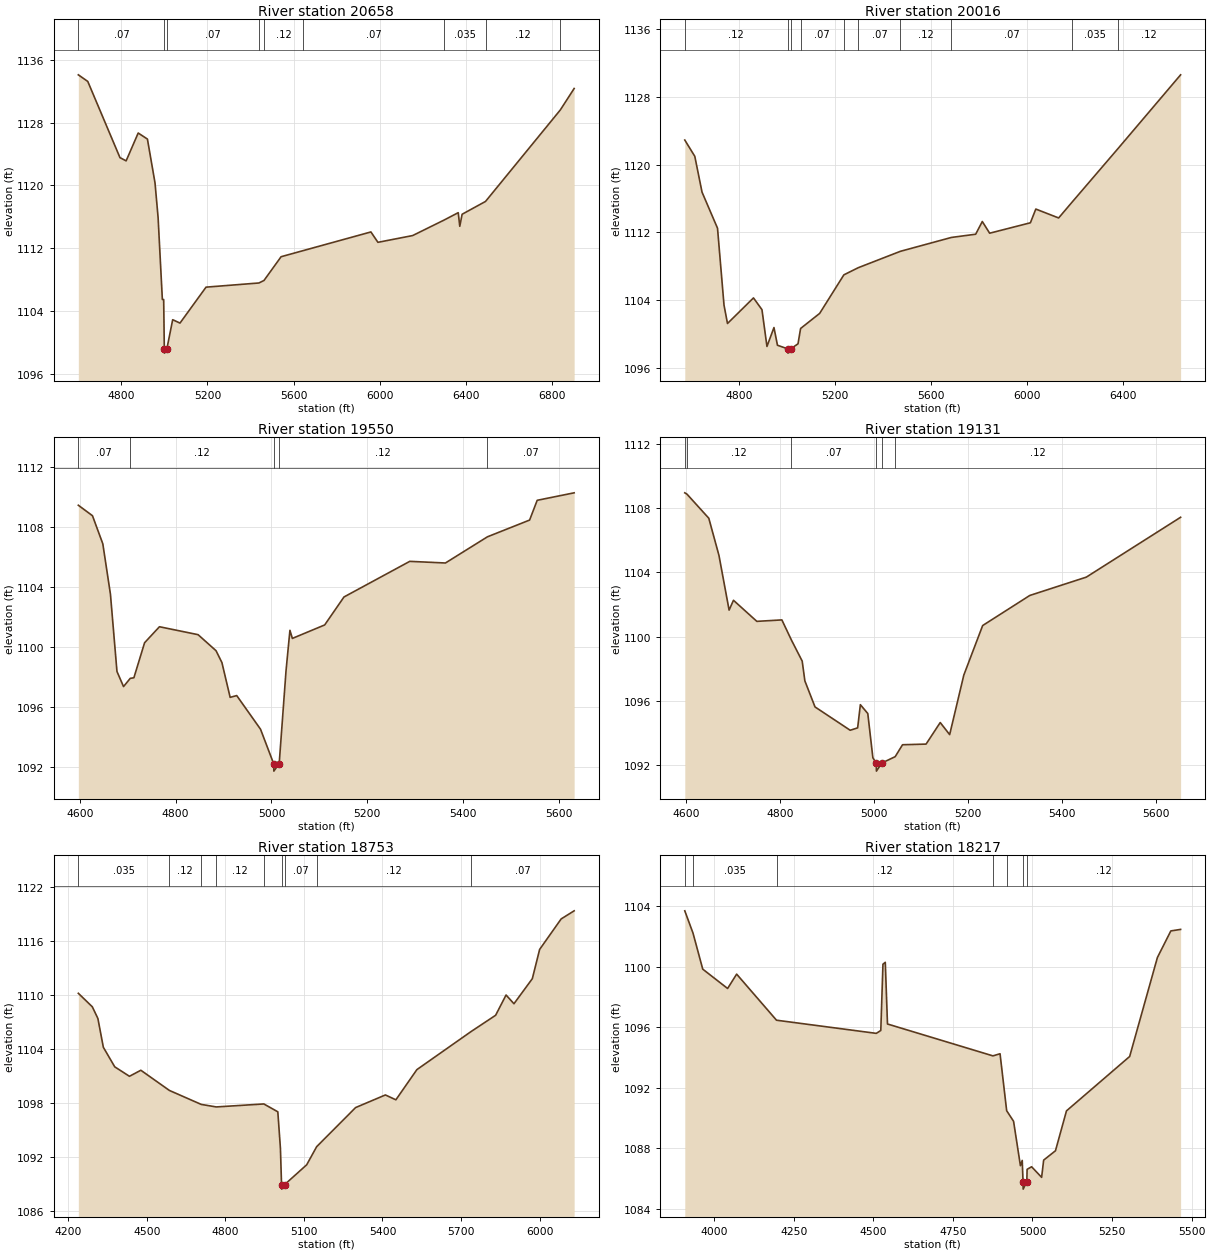
Type RM Length L Ch R = 1 ,20658   ,642,642,642
BEGIN DESCRIPTION:
Swine Creek 42.0
END DESCRIPTION:
XS GIS Cut Line= 4
      2142375.15     13854337.04      2142675.67     13854082.87
      2143434.95     13853688.85      2144404.02     13853280.53
#Sta/Elev= 30
  4601.1 1134.07  4644.9 1133.23  4794.3 1123.54  4822.9 1123.13  4878.9 1126.67
  4921.7  1125.9  4956.9 1120.33  4971.2 1115.94    4991  1105.5  4997.1  1105.5
  5000.1 1099.18  5000.6 1098.68  5011.6 1099.18  5038.9 1102.93  5072.8  1102.5
  5193.7 1107.07  5439.1  1107.6  5462.6 1107.92    5542 1110.94    5645 1111.72
  5958.7 1114.09  5991.2 1112.77  6152.4 1113.63  6298.1  1115.6  6363.9 1116.54
    6371 1114.81  6381.9 1116.34  6490.5 1117.97  6837.4  1129.6  6901.7 1132.33
#Mann= 9 ,-1 , 0
  4601.1     .07       0  5000.1     .05       0  5011.6     .07       0
  5439.1     .07       0  5462.6     .12       0    5645     .07       0
  6298.1    .035       0  6490.5     .12       0  6837.4    .035       0
Bank Sta=5000.1,5011.6
XS Rating Curve= 0 ,0
Exp/Cntr=0.3,0.1

Type RM Length L Ch R = 1 ,20016   ,466,466,466
BEGIN DESCRIPTION:
Swine Creek 41.0
END DESCRIPTION:
XS GIS Cut Line= 4
      2142874.96     13854625.03      2143226.89     13854360.85
        2143497.     13853804.39      2144388.25     13853330.71
#Sta/Elev= 30
  4573.1 1122.89  4614.8 1120.97    4645 1116.74  4709.6 1112.48  4736.7 1103.39
  4751.2 1101.23  4859.6 1104.25    4895 1102.86  4915.8 1098.52    4945 1100.75
  4959.6 1098.66    5003 1098.23  5003.5 1097.73  5014.6 1098.23  5045.3 1098.83
  5056.1 1100.64  5135.6 1102.42  5236.5 1106.97  5296.9 1107.82  5472.2 1109.75
  5685.2 1111.39  5786.3 1111.77  5813.9 1113.27  5844.6 1111.89  6014.5 1113.12
  6037.1 1114.74  6132.3 1113.69  6189.9 1115.61  6378.9 1121.85    6641 1130.59
#Mann= 10 ,-1 , 0
  4573.1     .12       0    5003     .05       0  5014.6     .12       0
  5056.1     .07       0  5236.5     .12       0  5296.9     .07       0
  5472.2     .12       0  5685.2     .07       0  6189.9    .035       0
  6378.9     .12       0
Bank Sta=5003,5014.6
XS Rating Curve= 0 ,0
Exp/Cntr=0.3,0.1

Type RM Length L Ch R = 1 ,19550   ,419,419,419
BEGIN DESCRIPTION:
Swine Creek 40.0
END DESCRIPTION:
XS GIS Cut Line= 3
        2143375.       13854875.        2143575.       13854525.
      2143651.31     13853898.45
#Sta/Elev= 30
  4597.1 1109.47  4626.6 1108.77  4648.2 1106.89  4664.1 1103.52  4677.7 1098.36
  4691.4 1097.35  4705.4  1097.9    4713 1097.94  4735.3 1100.28  4766.3 1101.35
  4846.9 1100.82  4884.3 1099.75  4896.6 1098.96  4913.8 1096.63  4927.5 1096.75
  4977.2  1094.5  5004.5  1092.2    5005  1091.7  5016.1  1092.2  5030.4 1098.42
  5038.5 1101.11  5043.6 1100.57    5111 1101.47  5151.3 1103.34  5288.5 1105.72
  5362.9 1105.61  5450.5 1107.36  5538.5 1108.48  5554.3  1109.8  5631.4  1110.3
#Mann= 5 ,-1 , 0
  4597.1     .07       0  4705.4     .12       0  5004.5     .05       0
  5016.1     .12       0  5450.5     .07       0
Bank Sta=5004.5,5016.1
XS Rating Curve= 0 ,0
Exp/Cntr=0.3,0.1

Type RM Length L Ch R = 1 ,19131   ,378,378,378
BEGIN DESCRIPTION:
Swine Creek 39.0
END DESCRIPTION:
XS GIS Cut Line= 3
      2143525.01       13854975.        2143875.       13854775.
        2143825.     13854125.02
#Sta/Elev= 30
  4596.9 1108.94  4601.5 1108.86    4648 1107.36  4669.6 1105.05  4691.2 1101.65
  4700.5 1102.26  4750.2 1100.95  4803.5 1101.04  4823.6  1099.8  4846.7 1098.48
  4852.4 1097.25    4874 1095.63  4948.9 1094.18  4964.7 1094.33  4970.5 1095.77
  4986.3 1095.22  4997.1 1092.47  5004.2 1092.14  5004.7 1091.64  5015.9 1092.14
  5044.6 1092.54  5060.2 1093.28  5110.3 1093.32  5140.4 1094.66  5160.5 1093.91
  5190.6 1097.61  5230.7 1100.69    5331 1102.56  5451.3  1103.7  5651.9 1107.42
#Mann= 6 ,-1 , 0
  4596.9     .07       0  4601.5     .12       0  4823.6     .07       0
  5004.2     .05       0  5015.9     .07       0  5044.6     .12       0
Bank Sta=5004.2,5015.9
XS Rating Curve= 0 ,0
Exp/Cntr=0.3,0.1

Type RM Length L Ch R = 1 ,18753   ,536,536,536
BEGIN DESCRIPTION:
Swine Creek 38.0
END DESCRIPTION:
XS GIS Cut Line= 3
      2143762.89     13855537.27      2144200.45     13854970.52
      2144267.31     13853795.52
#Sta/Elev= 30
  4238.9 1110.17  4292.3 1108.67  4313.6 1107.37  4334.4 1104.18  4377.9 1102.01
  4434.1 1100.96  4477.6 1101.63  4586.6 1099.39  4708.1 1097.84  4765.7 1097.56
  4947.2 1097.89  5000.5 1097.02  5010.5 1092.93  5014.7 1088.94  5015.2 1088.44
  5026.4 1088.94  5110.7 1091.14  5148.8 1093.15  5297.5 1097.49  5411.2 1098.89
  5451.2 1098.35  5531.4  1101.7  5737.1  1105.9    5832 1107.73  5871.9 1109.98
    5902 1109.01  5972.1 1111.79  6000.1 1115.04  6082.2 1118.42  6131.8 1119.32
#Mann= 9 ,-1 , 0
  4238.9    .035       0  4586.6     .12       0  4708.1     .07       0
  4765.7     .12       0  4947.2     .07       0  5014.7     .05       0
  5026.4     .07       0  5148.8     .12       0  5737.1     .07       0
Bank Sta=5014.7,5026.4
XS Rating Curve= 0 ,0
Exp/Cntr=0.3,0.1

Type RM Length L Ch R = 1 ,18217   ,485,485,485
BEGIN DESCRIPTION:
Swine Creek 37.0
END DESCRIPTION:
XS GIS Cut Line= 3
      2143975.01     13855674.99        2144725.       13854875.
      2144625.01     13854425.05
#Sta/Elev= 30
  3907.9 1103.71  3933.8 1102.23  3964.3 1099.85  4042.4 1098.57  4070.8 1099.52
    4196 1096.47  4509.4  1095.6  4523.6 1095.79  4530.4 1100.18  4537.7  1100.3
  4544.6 1096.22  4875.8 1094.11  4898.2 1094.25    4919 1090.48  4940.7 1089.78
  4962.2 1086.84  4967.9 1087.19  4970.4 1085.79  4970.9 1085.29  4982.3 1085.79
  4983.2  1086.6  4997.4 1086.77  5028.8 1086.07  5035.2 1087.21  5072.3 1087.83
  5106.9 1090.47  5305.4 1094.07  5392.5 1100.62  5434.7 1102.38  5465.4 1102.48
#Mann= 7 ,-1 , 0
  3907.9     .07       0  3933.8    .035       0    4196     .12       0
  4875.8     .07       0    4919     .12       0  4970.4     .05       0
  4982.3     .12       0
Bank Sta=4970.4,4982.3
XS Rating Curve= 0 ,0
Exp/Cntr=0.3,0.1

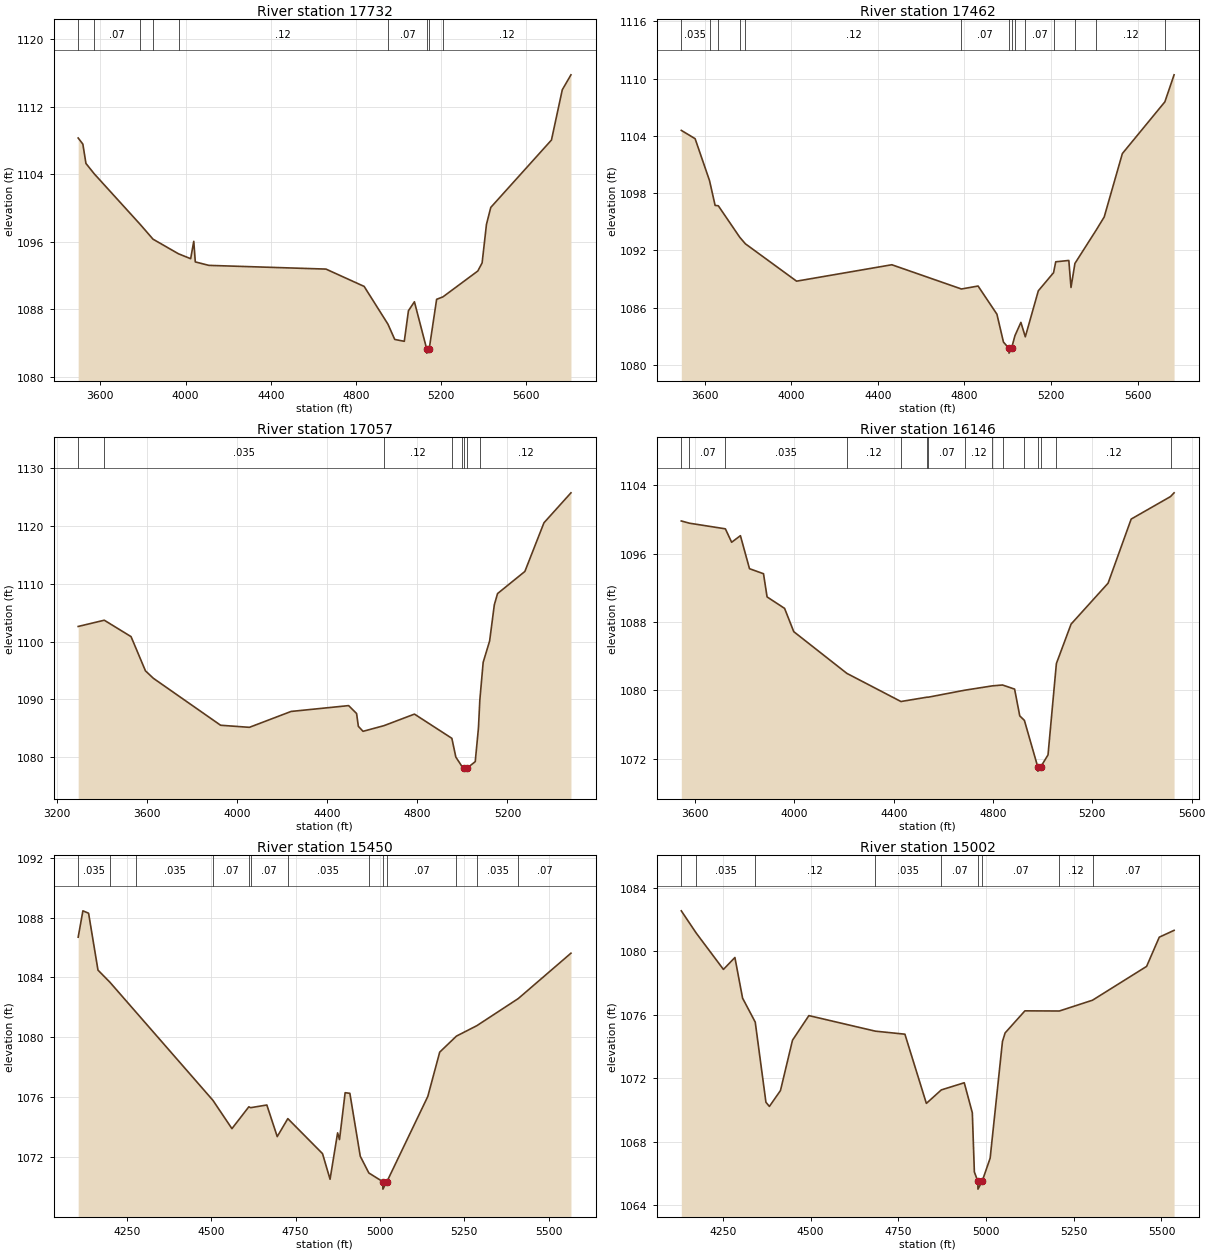
Type RM Length L Ch R = 1 ,17732   ,270,270,270
BEGIN DESCRIPTION:
Swine Creek 36.0
END DESCRIPTION:
XS GIS Cut Line= 3
      2143974.97     13855875.03        2145175.       13854975.
        2145325.     13854174.98
#Sta/Elev= 30
  3495.7 1108.28  3517.6 1107.56  3532.2 1105.27  3571.5 1104.03    3787 1098.05
  3847.2  1096.3  3966.8 1094.57  4023.9 1093.99  4038.5 1096.05  4045.7 1093.61
  4109.3  1093.2  4659.3 1092.76  4838.5 1090.71  4950.3 1086.24  4982.2 1084.43
  5027.1 1084.21  5046.6 1087.83  5074.6 1088.89  5132.2 1083.31  5132.7 1082.81
  5144.1 1083.31  5178.9 1089.18  5208.5 1089.47  5372.2 1092.53  5392.5 1093.49
  5412.9 1098.05  5433.2 1100.06  5718.1 1108.04    5769 1113.99  5809.7 1115.76
#Mann= 9 ,-1 , 0
  3495.7    .035       0  3571.5     .07       0    3787     .12       0
  3847.2    .035       0  3966.8     .12       0  4950.3     .07       0
  5132.2     .05       0  5144.1     .07       0  5208.5     .12       0
Bank Sta=5132.2,5144.1
XS Rating Curve= 0 ,0
Exp/Cntr=0.3,0.1

Type RM Length L Ch R = 1 ,17462   ,405,405,405
BEGIN DESCRIPTION:
Swine Creek 35.0
END DESCRIPTION:
XS GIS Cut Line= 3
      2144500.03     13856199.97      2145421.51     13855091.38
      2145517.36     13854262.06
#Sta/Elev= 30
  3491.9 1104.57  3555.7  1103.7  3622.3 1099.31  3648.1 1096.71  3662.9 1096.67
    3762 1093.37  3787.7 1092.69  4024.4 1088.77  4464.5 1090.49    4786 1087.95
  4862.9 1088.26  4949.9 1085.31  4980.1 1082.39  5005.4 1081.73  5005.9 1081.23
  5017.3 1081.73  5033.4 1083.07  5060.7 1084.45  5081.1 1082.94  5141.2 1087.76
  5211.6 1089.66  5221.7  1090.8  5282.1 1090.94  5292.2 1088.11  5310.3 1090.63
    5409 1094.14  5445.6  1095.5  5529.4 1102.14  5725.8 1107.56  5768.3 1110.39
#Mann= 14 ,-1 , 0
  3491.9    .035       0  3622.3     .07       0  3662.9    .035       0
    3762     .07       0  3787.7     .12       0    4786     .07       0
  5005.4     .05       0  5017.3     .07       0  5033.4    .035       0
  5081.1     .07       0  5211.6     .12       0  5310.3     .07       0
    5409     .12       0  5725.8     .07       0
Bank Sta=5005.4,5017.3
XS Rating Curve= 0 ,0
Exp/Cntr=0.3,0.1

Type RM Length L Ch R = 1 ,17057   ,911,911,911
BEGIN DESCRIPTION:
Swine Creek 34
END DESCRIPTION:
XS GIS Cut Line= 2
      2144699.98     13856500.03      2146087.47       13854809.
#Sta/Elev= 30
  3294.8 1102.61  3410.7 1103.69  3529.5 1100.85  3593.4 1094.93  3628.5 1093.64
  3927.1 1085.51  4054.8 1085.15  4239.9  1087.9  4495.4 1088.91  4530.6 1087.54
  4538.5 1085.32  4559.3 1084.46  4652.2 1085.44  4787.5 1087.44  4953.5 1083.25
  4971.2    1080  4999.5 1078.31  5008.1 1078.07  5008.6 1077.57  5020.3 1078.07
  5057.3 1079.21  5071.6 1085.05  5077.7 1089.87  5092.5  1096.4  5121.2  1100.1
    5142 1106.35  5156.3  1108.3  5277.6 1112.13  5362.3 1120.55  5482.2 1125.74
#Mann= 8 ,-1 , 0
  3294.8     .12       0  3410.7    .035       0  4652.2     .12       0
  4953.5    .035       0  4999.5     .07       0  5008.1     .05       0
  5020.3     .07       0  5077.7     .12       0
Bank Sta=5008.1,5020.3
XS Rating Curve= 0 ,0
Exp/Cntr=0.3,0.1

Type RM Length L Ch R = 1 ,16146   ,696,696,696
BEGIN DESCRIPTION:
Swine Creek 33.0
END DESCRIPTION:
XS GIS Cut Line= 2
      2144969.63     13856814.84      2146525.89     13855583.13
#Sta/Elev= 30
  3544.5 1099.82  3577.2 1099.56  3722.1  1098.9  3747.3 1097.33  3782.6  1098.1
  3819.2 1094.24  3875.6 1093.65    3890 1090.94  3960.5  1089.6  3997.4 1086.88
  4211.3    1082  4429.1 1078.71    4533 1079.21  4540.1 1079.22  4685.7 1080.03
  4797.7 1080.54  4838.3 1080.64  4886.9 1080.16  4907.7 1077.03  4926.4  1076.5
  4980.1 1071.07  4980.6 1070.57  4992.3 1071.07  5021.5 1072.47  5055.2 1083.15
  5114.4 1087.76  5263.5 1092.55  5356.4 1100.04  5514.8 1102.67  5529.2 1103.11
#Mann= 15 ,-1 , 0
  3544.5     .12       0  3577.2     .07       0  3722.1    .035       0
  4211.3     .12       0  4429.1     .07       0    4533     .12       0
  4540.1     .07       0  4685.7     .12       0  4797.7     .07       0
  4838.3    .035       0  4926.4     .07       0  4980.1    .035       0
  4992.3     .07       0  5055.2     .12       0  5514.8    .035       0
Bank Sta=4980.1,4992.3
XS Rating Curve= 0 ,0
Exp/Cntr=0.3,0.1

Type RM Length L Ch R = 1 ,15450   ,448,448,448
BEGIN DESCRIPTION:
Swine Creek 32.0
END DESCRIPTION:
XS GIS Cut Line= 3
      2145474.97     13856925.01        2146275.       13856525.
      2146674.97     13856125.03
#Sta/Elev= 30
  4105.8 1086.69  4119.8 1088.45  4136.6 1088.29  4164.5 1084.49  4199.8 1083.68
    4278 1081.66  4505.1 1075.79  4561.4  1073.9  4611.5 1075.36  4616.9  1075.3
  4664.8 1075.48  4695.6 1073.37    4727 1074.57  4829.8 1072.23  4852.1 1070.52
  4874.5 1073.62  4880.1 1073.17  4896.8  1076.3  4910.8 1076.26  4941.6 1072.06
    4967 1070.94  5008.2 1070.36  5008.7 1069.86  5020.6 1070.36  5141.7 1076.05
    5177 1079.01  5226.5 1080.08  5287.2 1080.78  5409.8 1082.59  5565.9 1085.62
#Mann= 13 ,-1 , 0
  4105.8    .035       0  4199.8     .12       0    4278    .035       0
  4505.1     .07       0  4611.5    .035       0  4616.9     .07       0
    4727    .035       0    4967     .07       0  5008.2     .05       0
  5020.6     .07       0  5226.5     .12       0  5287.2    .035       0
  5409.8     .07       0
Bank Sta=5008.2,5020.6
XS Rating Curve= 0 ,0
Exp/Cntr=0.3,0.1

Type RM Length L Ch R = 1 ,15002   ,331,331,331
BEGIN DESCRIPTION:
Swine Creek 31.0
END DESCRIPTION:
XS GIS Cut Line= 3
      2145724.97     13857225.01        2146525.       13856875.
      2146874.97     13856475.04
#Sta/Elev= 30
  4131.3 1082.56  4173.5 1081.17  4251.4 1078.87  4284.1 1079.62    4306 1077.06
  4342.1 1075.55  4372.6  1070.5  4382.4 1070.24    4414 1071.24  4448.3 1074.41
    4495 1075.96  4684.5 1074.98  4768.7 1074.79  4829.9 1070.43  4872.5 1071.28
  4937.9 1071.73  4960.9 1069.84  4966.7 1066.11  4976.5 1065.53    4977 1065.03
    4989 1065.53  5011.7 1066.98  5046.8 1074.33  5054.4 1074.87  5110.8 1076.26
    5209 1076.25  5303.5 1076.93  5457.7 1079.06  5493.8  1080.9    5536 1081.33
#Mann= 9 ,-1 , 0
  4131.3     .12       0  4173.5    .035       0  4342.1     .12       0
  4684.5    .035       0  4872.5     .07       0  4976.5     .05       0
    4989     .07       0    5209     .12       0  5303.5     .07       0
Bank Sta=4976.5,4989
XS Rating Curve= 0 ,0
Exp/Cntr=0.3,0.1