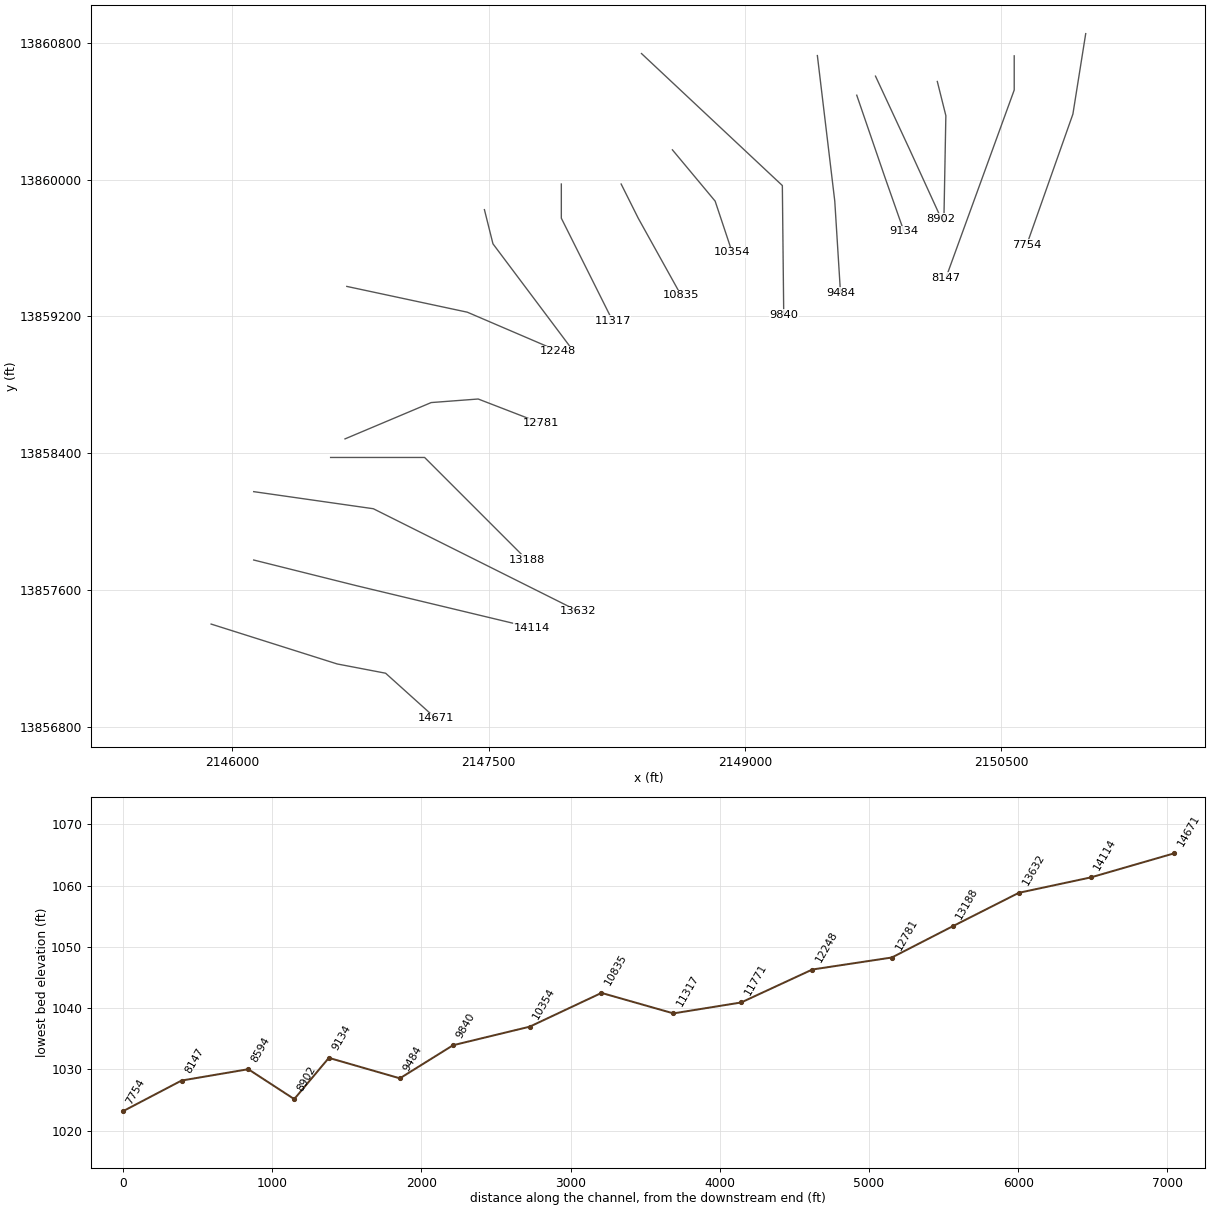
HEC-RAS study Swine Creek.prj: Swine Creek Base Level Engineering

--- Swine Creek.g01 (geometry) --- (continued)

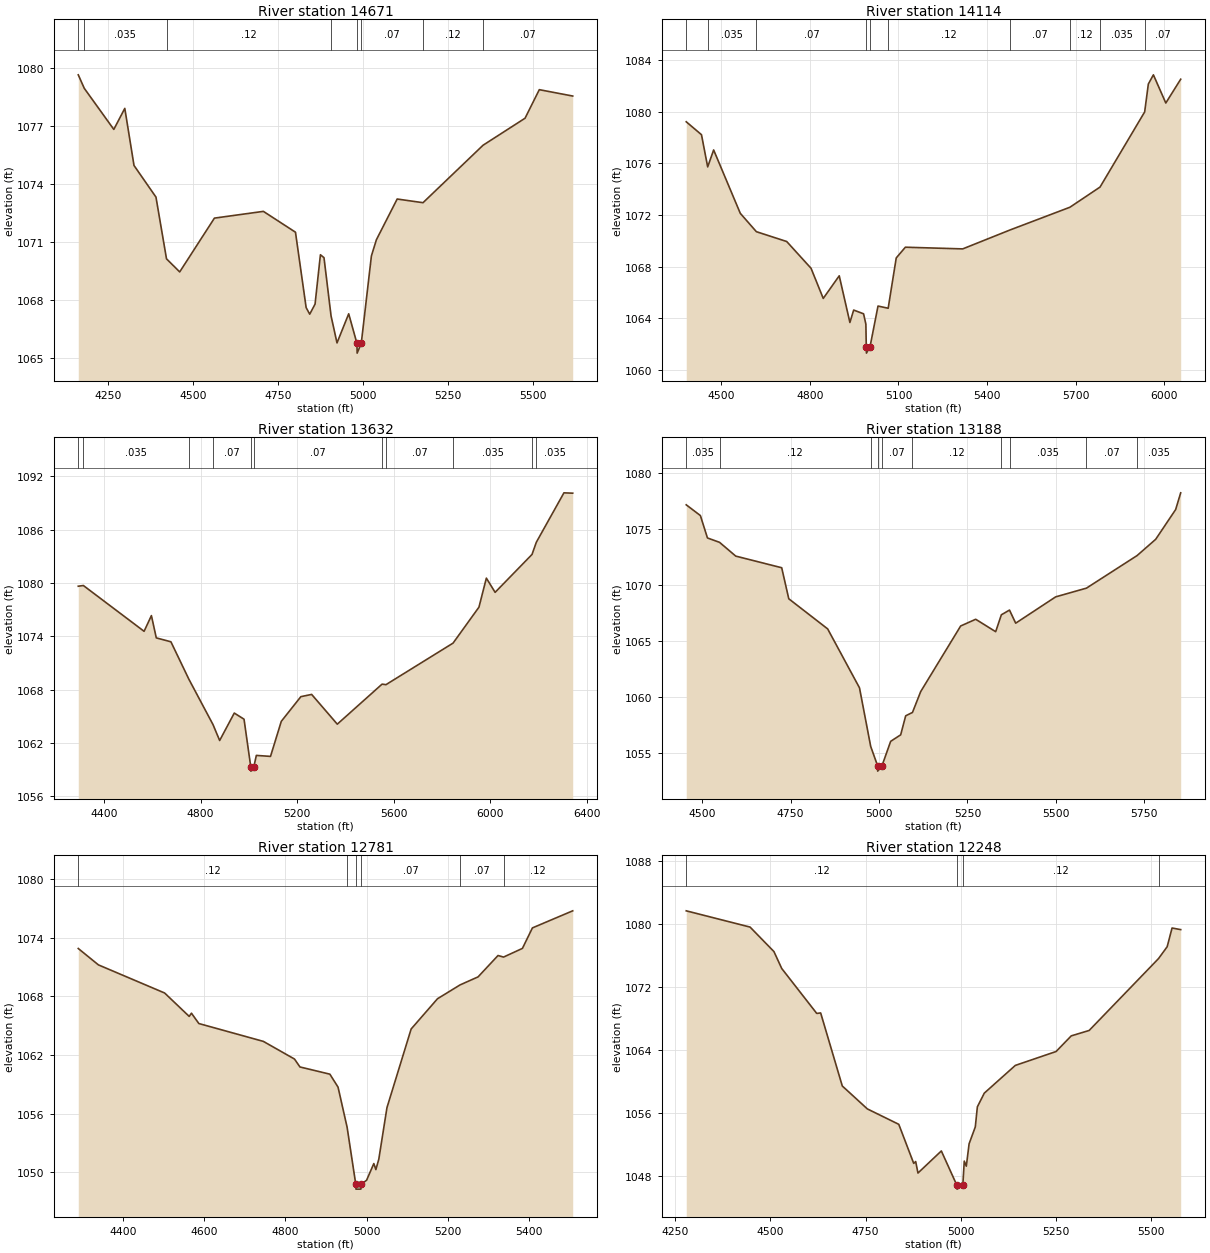
Type RM Length L Ch R = 1 ,14671   ,557,557,557
BEGIN DESCRIPTION:
Swine Creek 30.0
END DESCRIPTION:
XS GIS Cut Line= 4
       2145875.8     13857400.13       2146613.4     13857166.76
      2146896.78     13857112.58      2147188.48     13856850.05
#Sta/Elev= 30
  4163.2 1079.67  4180.9 1078.97  4267.8 1076.84  4300.1 1077.93  4327.2 1074.97
  4391.8 1073.33  4422.8 1070.13  4461.6 1069.45  4563.8 1072.24  4707.8 1072.59
  4802.2 1071.51  4833.6  1067.6  4844.1 1067.26  4859.8 1067.78  4875.6 1070.34
  4886.1 1070.19  4906.9 1067.17  4924.4 1065.77  4958.8 1067.28  4983.1 1065.74
  4983.6 1065.24  4995.7 1065.74  5025.6 1070.28  5040.3 1071.12  5101.4 1073.23
  5177.4 1073.04  5354.1 1076.02  5477.6 1077.42  5519.5  1078.9  5617.8 1078.57
#Mann= 8 ,-1 , 0
  4163.2     .12       0  4180.9    .035       0  4422.8     .12       0
  4906.9     .07       0  4983.1     .05       0  4995.7     .07       0
  5177.4     .12       0  5354.1     .07       0
Bank Sta=4983.1,4995.7
XS Rating Curve= 0 ,0
Exp/Cntr=0.3,0.1

Type RM Length L Ch R = 1 ,14114   ,482,482,482
BEGIN DESCRIPTION:
Swine Creek 29.0
END DESCRIPTION:
XS GIS Cut Line= 3
      2146124.98       13857775.        2146725.       13857625.
      2147751.51     13857378.84
#Sta/Elev= 30
  4381.5 1079.21  4433.1 1078.21  4454.1 1075.72  4474.3 1077.03  4564.5 1072.13
    4619 1070.71  4721.7 1069.95  4804.1 1067.88  4845.4 1065.55  4899.5  1067.3
  4935.6 1063.69  4948.4 1064.65  4981.9 1064.36  4989.7 1063.56  4991.1 1061.82
  4991.6 1061.32  5003.8 1061.82  5030.8 1064.96  5065.2 1064.79  5092.5 1068.68
  5123.4 1069.51  5317.6 1069.38  5476.3 1070.83  5680.5  1072.6  5782.5 1074.16
  5933.6 1079.97  5946.1 1082.13  5963.2 1082.84  6005.2 1080.66  6055.6  1082.5
#Mann= 10 ,-1 , 0
  4381.5     .12       0  4454.1    .035       0    4619     .07       0
  4991.1     .05       0  5003.8     .07       0  5065.2     .12       0
  5476.3     .07       0  5680.5     .12       0  5782.5    .035       0
  5933.6     .07       0
Bank Sta=4991.1,5003.8
XS Rating Curve= 0 ,0
Exp/Cntr=0.3,0.1

Type RM Length L Ch R = 1 ,13632   ,444,444,444
BEGIN DESCRIPTION:
Swine Creek 28.0
END DESCRIPTION:
XS GIS Cut Line= 3
      2146124.97       13858175.        2146825.       13858075.
      2148025.02     13857474.99
#Sta/Elev= 30
  4293.3 1079.64  4314.4 1079.72  4566.1 1074.56  4596.4 1076.33  4616.6 1073.82
  4677.2 1073.38  4751.7 1069.16  4851.7 1064.05  4879.2 1062.26  4939.8 1065.35
  4980.2 1064.66    5008 1059.31  5008.5 1058.81  5020.8 1059.31  5031.2 1060.58
  5089.9 1060.47  5134.6 1064.42  5215.7  1067.2  5260.4 1067.45  5366.6  1064.1
  5552.2 1068.61  5568.3 1068.55  5846.3 1073.23  5953.6 1077.28  5984.3 1080.55
  6020.6 1078.95  6173.5 1083.22  6191.3 1084.59  6305.7 1090.16  6342.1 1090.12
#Mann= 11 ,-1 , 0
  4293.3     .12       0  4314.4    .035       0  4751.7     .12       0
  4851.7     .07       0    5008     .05       0  5020.8     .07       0
  5552.2    .035       0  5568.3     .07       0  5846.3    .035       0
  6173.5     .07       0  6191.3    .035       0
Bank Sta=5008,5020.8
XS Rating Curve= 0 ,0
Exp/Cntr=0.3,0.1

Type RM Length L Ch R = 1 ,13188   ,407,407,407
BEGIN DESCRIPTION:
Swine Creek 27.0
END DESCRIPTION:
XS GIS Cut Line= 3
      2146575.04       13858375.        2147125.       13858375.
      2147725.01     13857774.99
#Sta/Elev= 30
  4454.8 1077.12  4494.8 1076.16  4514.8 1074.16    4549 1073.77  4594.8 1072.54
  4724.8  1071.5  4744.8 1068.73  4854.8 1066.04  4944.8 1060.78  4976.5 1055.55
  4995.8 1053.84  4996.3 1053.34  5008.7 1053.84    5033    1056  5061.3 1056.58
  5075.5 1058.28  5094.7 1058.58  5117.9 1060.44    5231  1066.3  5273.5  1066.9
    5330 1065.79  5346.1  1067.3  5369.1 1067.72  5386.6 1066.55  5499.7  1068.9
  5586.8 1069.68  5730.1 1072.59  5782.6 1074.04  5839.1  1076.7  5853.3 1078.19
#Mann= 10 ,-1 , 0
  4454.8    .035       0    4549     .12       0  4976.5     .07       0
  4995.8     .05       0  5008.7     .07       0  5094.7     .12       0
  5346.1     .07       0  5369.1    .035       0  5586.8     .07       0
  5730.1    .035       0
Bank Sta=4995.8,5008.7
XS Rating Curve= 0 ,0
Exp/Cntr=0.3,0.1

Type RM Length L Ch R = 1 ,12781   ,533,533,533
BEGIN DESCRIPTION:
Swine Creek 26.0
END DESCRIPTION:
XS GIS Cut Line= 4
      2146659.26     13858483.68       2147163.5     13858696.21
      2147438.55     13858717.05      2147805.29     13858575.35
#Sta/Elev= 30
  4290.7 1072.91  4340.3 1071.23  4503.1 1068.35  4563.6 1065.95  4569.1 1066.28
  4587.3 1065.22    4746 1063.39  4822.6 1061.58    4836 1060.77  4909.6 1060.03
  4929.7  1058.7    4952 1054.59  4973.3 1048.75  4973.8 1048.25  4985.8 1048.25
  4986.3 1048.75  4999.9 1049.16  5017.7 1050.87  5022.7 1050.25    5030 1051.33
    5050  1056.6  5109.5 1064.66  5174.3 1067.76  5229.9 1069.18  5274.1    1070
  5323.2 1072.19  5336.8 1072.03  5383.2 1072.92  5407.8 1075.02  5506.9 1076.77
#Mann= 6 ,-1 , 0
  4290.7     .12       0    4952     .07       0  4973.3     .05       0
  4986.3     .07       0  5229.9     .07       0  5336.8     .12       0
Bank Sta=4973.3,4986.3
XS Rating Curve= 0 ,0
Exp/Cntr=0.3,0.1

Type RM Length L Ch R = 1 ,12248   ,477,477,477
BEGIN DESCRIPTION:
Swine Creek 25.0
END DESCRIPTION:
XS GIS Cut Line= 3
      2146669.74     13859375.87        2147375.       13859225.
      2147905.85     13858997.39
#Sta/Elev= 30
  4278.8 1081.72  4446.5 1079.65  4509.2 1076.53  4529.6 1074.38  4621.6 1068.66
  4631.9 1068.72  4688.7 1059.42  4754.6  1056.5  4837.1 1054.54  4876.3 1049.57
  4881.5  1049.8  4887.5 1048.34  4948.9 1051.15  4989.6 1046.79  4990.1 1046.29
  5005.3 1046.79  5009.1 1049.86  5014.5 1049.21  5021.8 1052.06  5038.1 1054.21
  5043.5 1056.76  5061.7 1058.51  5143.2 1062.04  5250.3 1063.81  5290.1  1065.8
  5337.2 1066.49  5519.4 1075.64  5542.1 1077.15  5554.9 1079.53  5577.6 1079.33
#Mann= 4 ,-1 , 0
  4278.8     .12       0  4989.6     .05       0  5005.3     .12       0
  5519.4     .07       0
Bank Sta=4989.6,5005.3
XS Rating Curve= 0 ,0
Exp/Cntr=0.3,0.1

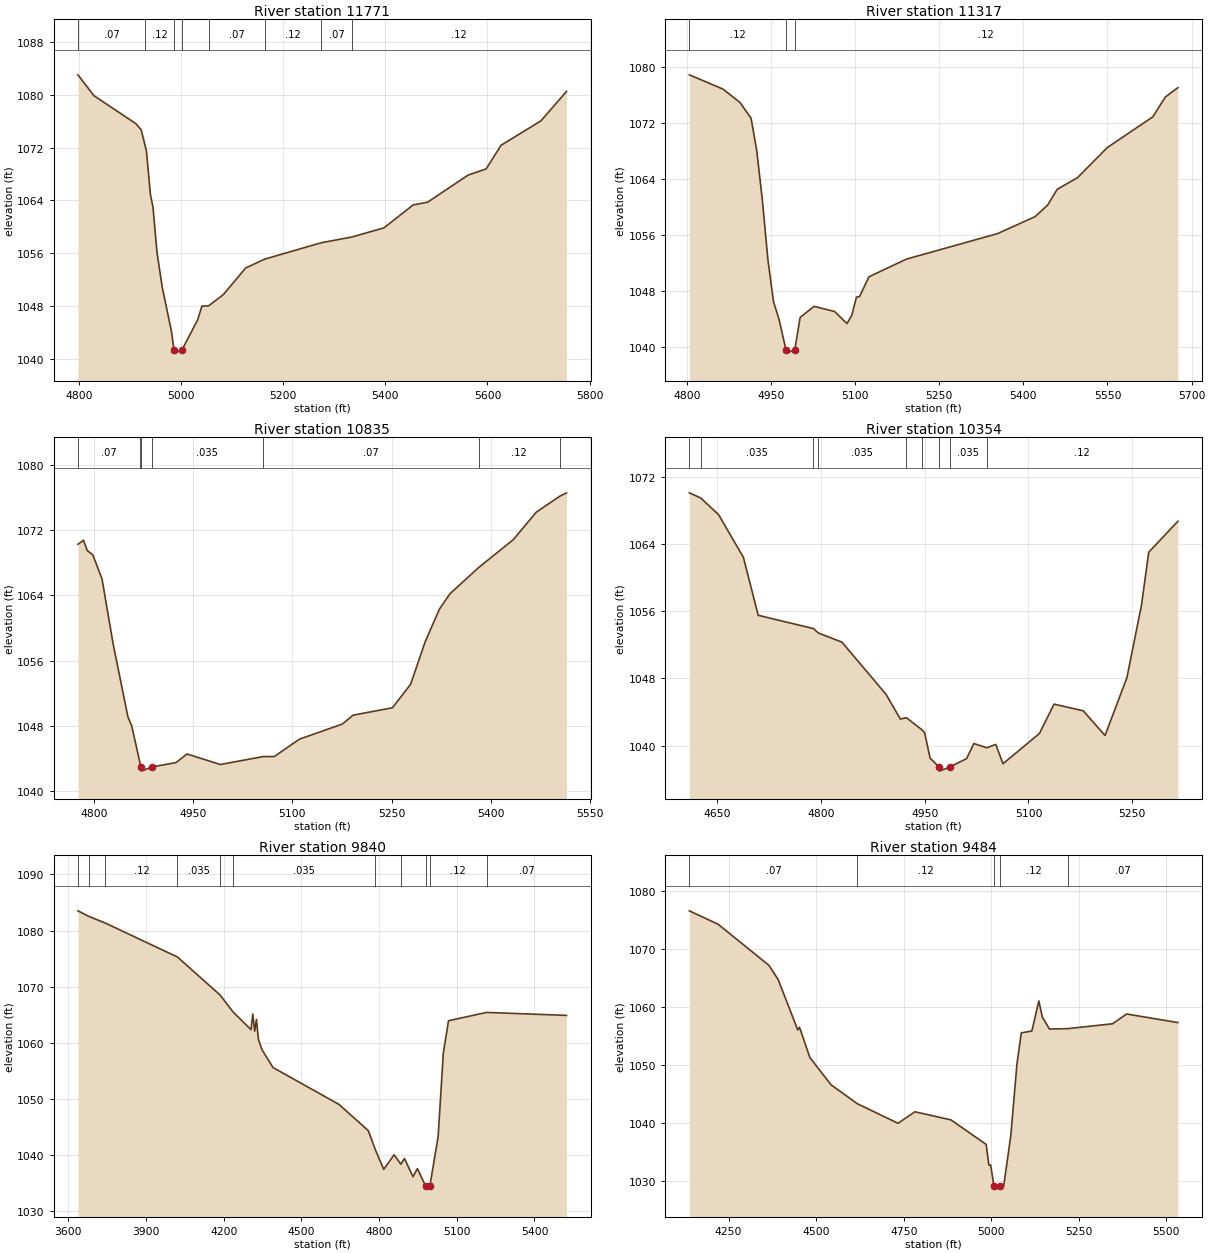
Type RM Length L Ch R = 1 ,11771   ,454,454,454
BEGIN DESCRIPTION:
Swine Creek 24.0
END DESCRIPTION:
XS GIS Cut Line= 3
      2147474.99     13859825.03        2147525.       13859625.
      2147975.01     13859024.99
#Sta/Elev= 30
  4798.5 1083.01  4829.5 1079.87  4911.9 1075.62  4922.2  1074.7  4930.4 1072.15
  4932.5  1071.5  4940.3 1064.91  4945.4 1062.97  4953.2 1056.14  4963.5 1050.86
  4981.5 1044.18  4986.5 1041.41    4987 1040.91  5002.2 1041.41  5032.8 1045.95
  5041.1 1048.02  5054.1 1048.06  5082.8 1049.74  5126.6 1053.78  5163.6 1055.12
  5274.9 1057.61  5334.8 1058.48  5397.4 1059.86  5454.7 1063.33  5482.8 1063.74
    5562 1067.84  5597.4 1068.78  5626.6 1072.35  5704.7 1076.05  5754.7  1080.5
#Mann= 8 ,-1 , 0
  4798.5     .07       0  4930.4     .12       0  4986.5     .05       0
  5002.2     .12       0  5054.1     .07       0  5163.6     .12       0
  5274.9     .07       0  5334.8     .12       0
Bank Sta=4986.5,5002.2
XS Rating Curve= 0 ,0
Exp/Cntr=0.3,0.1

Type RM Length L Ch R = 1 ,11317   ,482,482,482
BEGIN DESCRIPTION:
Swine Creek 23.0
END DESCRIPTION:
XS GIS Cut Line= 3
        2147925.     13859974.96        2147925.       13859775.
      2148225.01     13859174.98
#Sta/Elev= 30
  4804.7 1078.86  4864.7 1076.82  4894.7 1074.93  4914.7 1072.67  4924.7  1068.1
  4934.7 1061.09  4944.7 1052.47  4954.7 1046.48  4964.7  1043.9  4976.8 1039.63
  4977.3 1039.13  4992.6 1039.63  5002.2 1044.23    5027 1045.81  5063.4 1045.08
  5085.7 1043.35  5094.1 1044.51  5102.5 1047.12  5108.1 1047.21  5124.8 1050.03
  5191.9 1052.56    5354 1056.19  5421.1 1058.62  5443.5 1060.28  5460.3 1062.51
  5496.6 1064.18  5549.7 1068.48  5630.8 1072.86  5653.1 1075.69  5675.5 1077.03
#Mann= 3 ,-1 , 0
  4804.7     .12       0  4976.8     .05       0  4992.6     .12       0
Bank Sta=4976.8,4992.6
XS Rating Curve= 0 ,0
Exp/Cntr=0.3,0.1

Type RM Length L Ch R = 1 ,10835   ,481,481,481
BEGIN DESCRIPTION:
Swine Creek 22.0
END DESCRIPTION:
XS GIS Cut Line= 3
      2148274.99     13859975.02        2148375.       13859775.
        2148625.     13859325.01
#Sta/Elev= 30
  4775.9 1070.25  4784.3 1070.75  4789.9 1069.48  4798.3 1068.96  4812.3    1066
    4829 1058.07  4851.4 1049.11    4857 1048.05  4869.7 1043.46  4871.4 1042.97
  4871.9 1042.47  4887.2 1042.97  4924.1 1043.52  4940.8 1044.57  4991.1 1043.28
  5055.7 1044.25  5072.7 1044.26  5110.5 1046.38  5175.7 1048.24  5191.7 1049.32
  5251.2 1050.23  5278.7 1053.11  5300.4 1058.25  5322.1 1062.29  5338.1 1064.19
  5381.5  1067.4  5434.2 1070.84  5468.5 1074.17  5503.8 1076.12  5514.3 1076.55
#Mann= 7 ,-1 , 0
  4775.9     .07       0  4869.7    .035       0  4871.4    .035       0
  4887.2    .035       0  5055.7     .07       0  5381.5     .12       0
  5503.8     .07       0
Bank Sta=4871.4,4887.2
XS Rating Curve= 0 ,0
Exp/Cntr=0.3,0.1

Type RM Length L Ch R = 1 ,10354   ,514,514,514
BEGIN DESCRIPTION:
Swine Creek 21.0
END DESCRIPTION:
XS GIS Cut Line= 3
      2148574.97     13860175.04        2148825.       13859875.
        2148925.     13859574.99
#Sta/Elev= 30
  4609.4 1070.07  4625.8 1069.46  4651.8 1067.46  4687.6 1062.39    4709  1055.5
  4788.9 1053.92  4796.1 1053.39  4830.1 1052.31  4893.9  1046.1  4914.7 1043.15
  4923.3 1043.32  4945.3 1041.92  4949.8 1041.53  4957.7  1038.5  4970.6 1037.46
  4971.1 1036.96  4986.4 1037.46  5010.5 1038.45    5021 1040.24  5039.6 1039.74
  5052.7 1040.14  5063.2 1037.84  5115.9 1041.44    5137 1044.93  5179.2 1044.14
  5210.8  1041.2  5242.4 1048.07  5263.5 1056.69    5274    1063  5316.2 1066.69
#Mann= 9 ,-1 , 0
  4609.4     .12       0  4625.8    .035       0  4788.9     .07       0
  4796.1    .035       0  4923.3     .07       0  4945.3    .035       0
  4970.6    .035       0  4986.4    .035       0  5039.6     .12       0
Bank Sta=4970.6,4986.4
XS Rating Curve= 0 ,0
Exp/Cntr=0.3,0.1

Type RM Length L Ch R = 1 ,9840    ,356,356,356
BEGIN DESCRIPTION:
Swine Creek 20.0
END DESCRIPTION:
XS GIS Cut Line= 3
      2148394.11      13860738.4      2149218.26     13859966.07
      2149226.37     13859209.38
#Sta/Elev= 30
  3637.4 1083.51  3678.5 1082.54  3743.5 1081.32  4021.6 1075.28  4185.9 1068.52
    4236 1065.51  4305.5 1062.34  4312.4 1065.12  4319.7 1062.07  4326.5 1064.16
  4333.9 1060.66    4348 1058.76  4390.5 1055.59    4645 1049.03  4758.3 1044.35
  4785.6 1040.95  4817.9 1037.45  4857.9 1040.05    4884 1038.37  4897.9 1039.39
    4931 1036.14    4948 1037.59    4980 1034.43  4980.5 1033.93  4995.9 1034.43
    5028 1043.31    5048 1058.15    5068 1063.93  5214.9 1065.41  5523.6 1064.88
#Mann= 11 ,-1 , 0
  3637.4     .12       0  3678.5    .035       0  3743.5     .12       0
  4021.6    .035       0  4185.9     .12       0    4236    .035       0
  4785.6     .07       0    4884     .12       0    4980     .05       0
  4995.9     .12       0  5214.9     .07       0
Bank Sta=4980,4995.9
XS Rating Curve= 0 ,0
Exp/Cntr=0.3,0.1

Type RM Length L Ch R = 1 ,9484    ,476,476,476
BEGIN DESCRIPTION:
Swine Creek 19.0
END DESCRIPTION:
XS GIS Cut Line= 3
      2149423.17     13860726.59        2149525.       13859875.
      2149558.52      13859338.8
#Sta/Elev= 30
  4137.9  1076.6  4220.1 1074.28    4365 1067.19  4391.3 1064.75  4447.4 1056.03
  4452.4  1056.5  4481.9 1051.27  4542.3 1046.56  4617.4 1043.29  4733.7  1039.9
    4782 1041.89  4884.8 1040.49  4985.5 1036.25    4993 1032.71  4998.1 1032.71
  5007.6 1029.03  5008.1 1028.53  5023.5 1029.03  5035.6 1029.14  5055.7 1037.77
  5073.2  1050.1  5085.7 1055.52  5115.8 1055.84  5135.8 1061.03  5145.8 1058.26
  5165.9 1056.19  5218.6 1056.25  5346.2 1057.09  5386.3 1058.78  5532.8  1057.3
#Mann= 5 ,-1 , 0
  4137.9     .07       0  4617.4     .12       0  5007.6     .05       0
  5023.5     .12       0  5218.6     .07       0
Bank Sta=5007.6,5023.5
XS Rating Curve= 0 ,0
Exp/Cntr=0.3,0.1

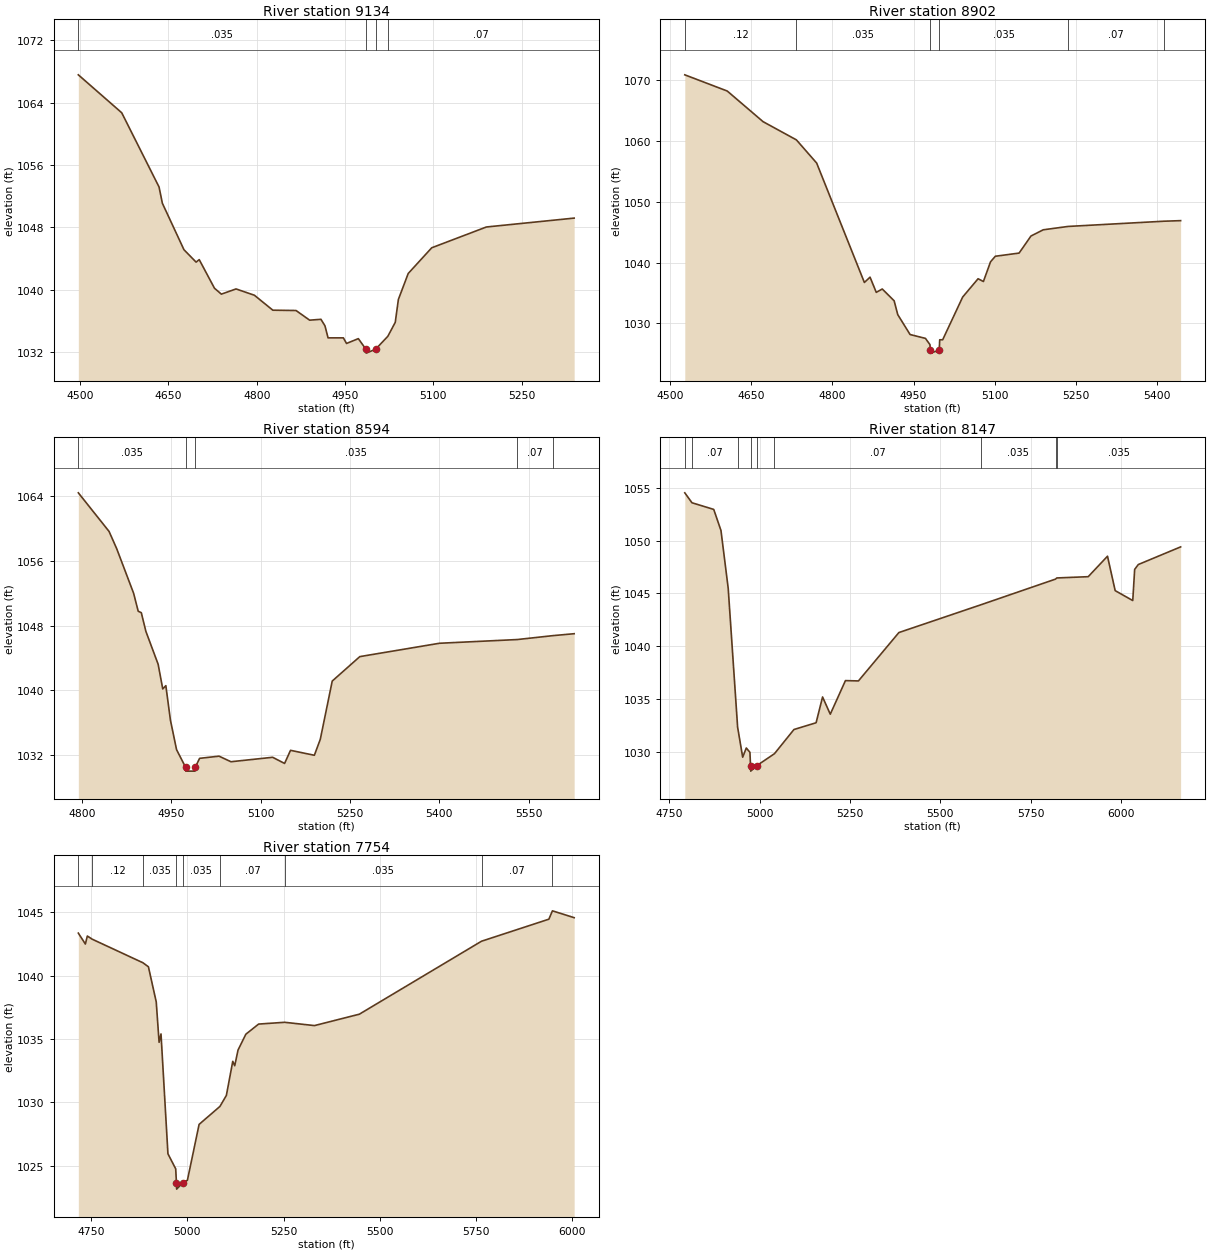
Type RM Length L Ch R = 1 ,9134    ,232,232,232
BEGIN DESCRIPTION:
Swine Creek 18.0
END DESCRIPTION:
XS GIS Cut Line= 3
      2149653.58     13860494.72      2149816.84     13860018.95
      2149929.29     13859699.15
#Sta/Elev= 30
    4497 1067.59  4570.7 1062.72  4634.1 1053.19  4639.7 1051.11  4676.4 1045.14
    4697 1043.55  4702.3 1043.87  4728.2  1040.2  4739.9 1039.44  4764.8 1040.11
    4796  1039.3  4827.3 1037.38  4866.7 1037.34  4889.8  1036.1    4909 1036.21
  4915.8 1035.38  4921.1 1033.83  4947.1 1033.83  4952.4 1033.11  4972.5 1033.73
  4985.4 1032.37  4985.9 1031.87  5001.8 1032.37  5022.6 1034.03  5035.2 1035.82
  5040.5 1038.76  5057.2 1042.09  5097.1 1045.39    5190 1048.06    5339  1049.2
#Mann= 4 ,-1 , 0
    4497    .035       0  4985.4    .035       0  5001.8    .035       0
  5022.6     .07       0
Bank Sta=4985.4,5001.8
XS Rating Curve= 0 ,0
Exp/Cntr=0.3,0.1

Type RM Length L Ch R = 1 ,8902    ,308,308,308
BEGIN DESCRIPTION:
Swine Creek 17.5
END DESCRIPTION:
XS GIS Cut Line= 3
       2149763.3     13860606.27      2149962.96     13860177.14
      2150147.75      13859773.2
#Sta/Elev= 30
  4526.7 1070.79  4605.3 1068.13  4671.5 1063.11  4733.2 1060.12  4770.7 1056.32
    4859 1036.73  4869.5  1037.6    4881 1035.11  4892.1 1035.66  4914.1 1033.72
  4920.8 1031.45  4943.6 1028.19    4972 1027.56  4980.3 1026.54  4981.2 1025.64
  4981.7 1025.14  4997.6 1025.64  4998.4 1027.33  5003.9 1027.33  5040.9 1034.34
  5069.4 1037.34  5079.3 1036.89  5092.4 1040.11  5101.3 1041.03  5145.3 1041.55
  5167.3 1044.35    5190 1045.37  5235.9 1045.92  5413.7 1046.78  5444.2 1046.87
#Mann= 6 ,-1 , 0
  4526.7     .12       0  4733.2    .035       0  4981.2    .035       0
  4997.6    .035       0  5235.9     .07       0  5413.7    .035       0
Bank Sta=4981.2,4997.6
XS Rating Curve= 0 ,0
Exp/Cntr=0.3,0.1

Type RM Length L Ch R = 1 ,8594    ,447,447,447
BEGIN DESCRIPTION:
Swine Creek 17.0
END DESCRIPTION:
XS GIS Cut Line= 3
        2150125.     13860575.01        2150175.       13860375.
       2150163.3     13859748.98
#Sta/Elev= 30
  4794.1 1064.41  4845.7 1059.64  4858.5 1057.51  4886.9    1052  4894.6 1049.78
  4899.8  1049.6  4907.5 1047.29  4928.1 1043.22  4935.8 1040.18    4941 1040.58
  4948.7 1036.32    4959 1032.67    4974 1030.52  4974.5 1030.02    4990 1030.02
  4990.5 1030.52  4997.7  1031.6  5030.3 1031.87  5050.3 1031.18  5120.3 1031.73
  5140.3 1030.97  5150.3 1032.59  5190.3 1031.98  5200.3 1033.96  5220.3 1041.15
  5266.6 1044.17  5400.3 1045.82    5531 1046.28  5590.4 1046.76  5626.4    1047
#Mann= 5 ,-1 , 0
  4794.1    .035       0    4974    .035       0  4990.5    .035       0
    5531     .07       0  5590.4    .035       0
Bank Sta=4974,4990.5
XS Rating Curve= 0 ,0
Exp/Cntr=0.3,0.1

Type RM Length L Ch R = 1 ,8147    ,393,393,393
BEGIN DESCRIPTION:
Swine Creek 16.0
END DESCRIPTION:
XS GIS Cut Line= 3
        2150575.     13860724.95        2150575.       13860525.
      2150175.01     13859425.02
#Sta/Elev= 30
  4793.5 1054.52  4813.3 1053.58  4873.5 1052.95  4893.5 1050.95  4913.5 1045.47
  4939.5 1032.33  4953.5 1029.49  4963.5 1030.36  4973.5 1029.95  4975.2 1028.67
  4975.7 1028.17  4991.7 1028.67  5041.3 1029.82  5095.2 1032.11  5156.4 1032.75
  5174.3 1035.19  5195.6 1033.56  5237.5 1036.74  5273.4 1036.71  5385.2 1041.29
  5611.9 1043.92  5818.1 1046.35  5821.7 1046.46  5908.5 1046.58  5961.8 1048.52
    5983 1045.26  6031.6 1044.32  6036.9 1047.27  6046.9 1047.73  6163.9  1049.4
#Mann= 9 ,-1 , 0
  4793.5     .12       0  4813.3     .07       0  4939.5    .035       0
  4975.2    .035       0  4991.7    .035       0  5041.3     .07       0
  5611.9    .035       0  5818.1     .07       0  5821.7    .035       0
Bank Sta=4975.2,4991.7
XS Rating Curve= 0 ,0
Exp/Cntr=0.3,0.1

Type RM Length L Ch R = 1 ,7754    ,552,552,552
BEGIN DESCRIPTION:
Swine Creek 15.0
END DESCRIPTION:
XS GIS Cut Line= 3
      2150993.37     13860854.98      2150918.35     13860384.02
      2150647.95     13859618.57
#Sta/Elev= 30
  4716.5 1043.37  4734.8 1042.51  4739.9 1043.14  4752.6 1042.89  4884.4 1041.03
  4898.7 1040.71    4919 1037.94  4926.4 1034.75  4931.4 1035.41  4949.4 1025.95
  4969.6 1024.76  4971.5 1023.66    4972 1023.16    4988 1023.66    5000 1023.86
  5030.4 1028.27  5084.6 1029.69  5101.3 1030.56  5117.9 1033.25    5123  1032.9
  5131.6 1034.14  5151.9 1035.39  5185.1 1036.19  5252.8 1036.33  5330.2 1036.07
  5446.9 1036.97  5764.4 1042.73  5939.5 1044.47  5948.7 1045.13  6005.2 1044.59
#Mann= 9 ,-1 , 0
  4716.5    .035       0  4752.6     .12       0  4884.4    .035       0
  4971.5    .035       0    4988    .035       0  5084.6     .07       0
  5252.8    .035       0  5764.4     .07       0  5948.7    .035       0
Bank Sta=4971.5,4988
XS Rating Curve= 0 ,0
Exp/Cntr=0.3,0.1