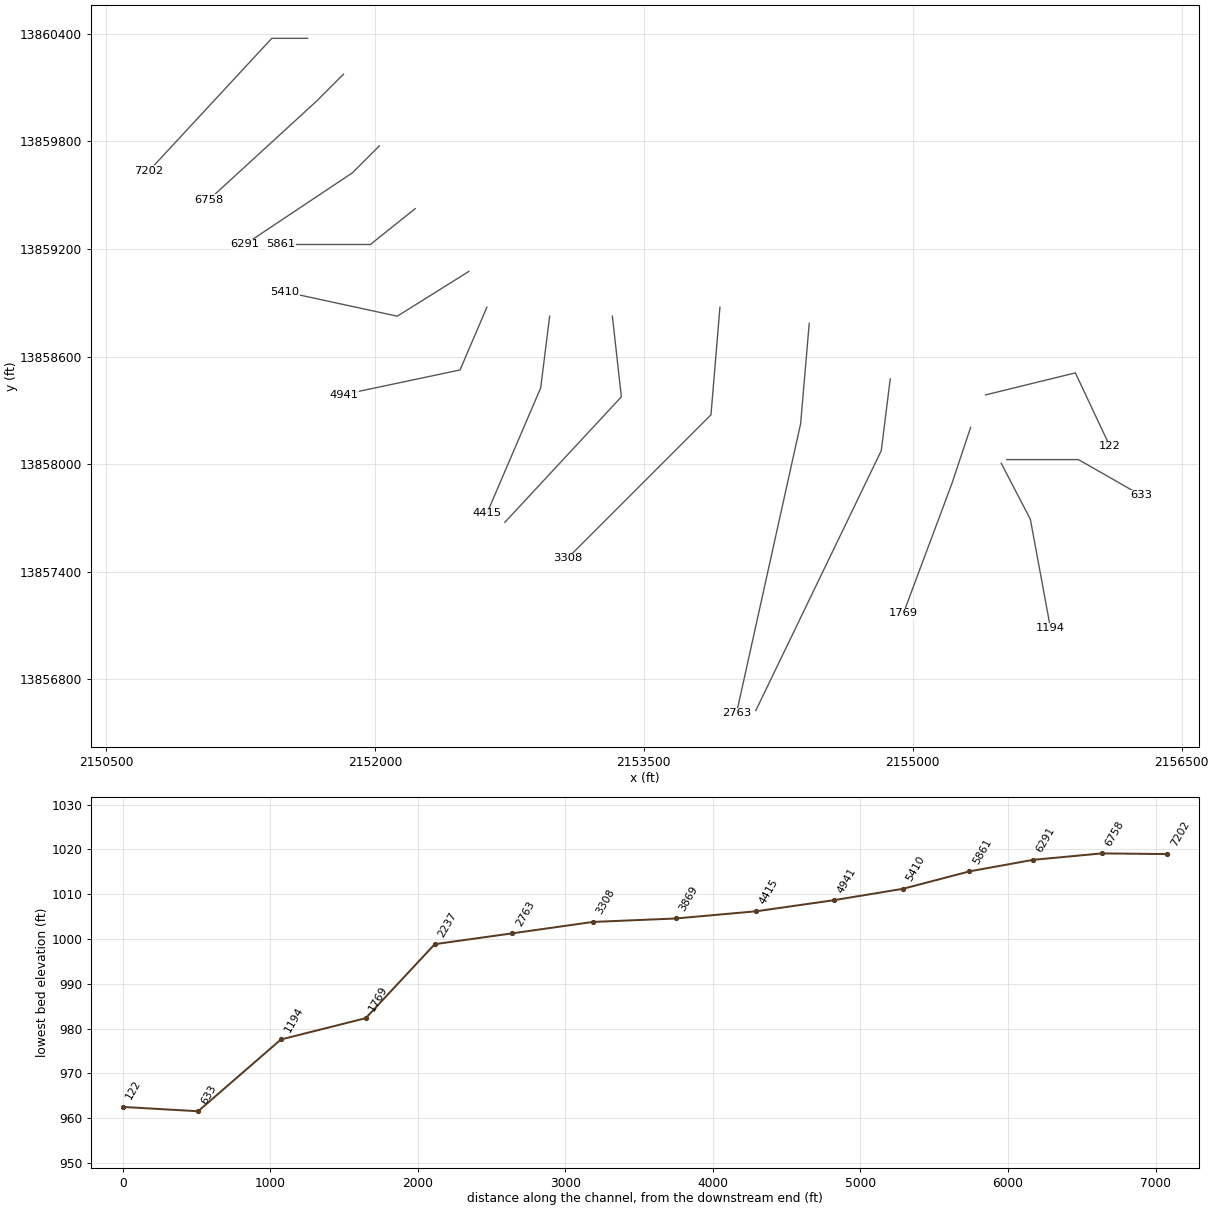
HEC-RAS study Swine Creek.prj: Swine Creek Base Level Engineering

--- Swine Creek.g01 (geometry) --- (continued)

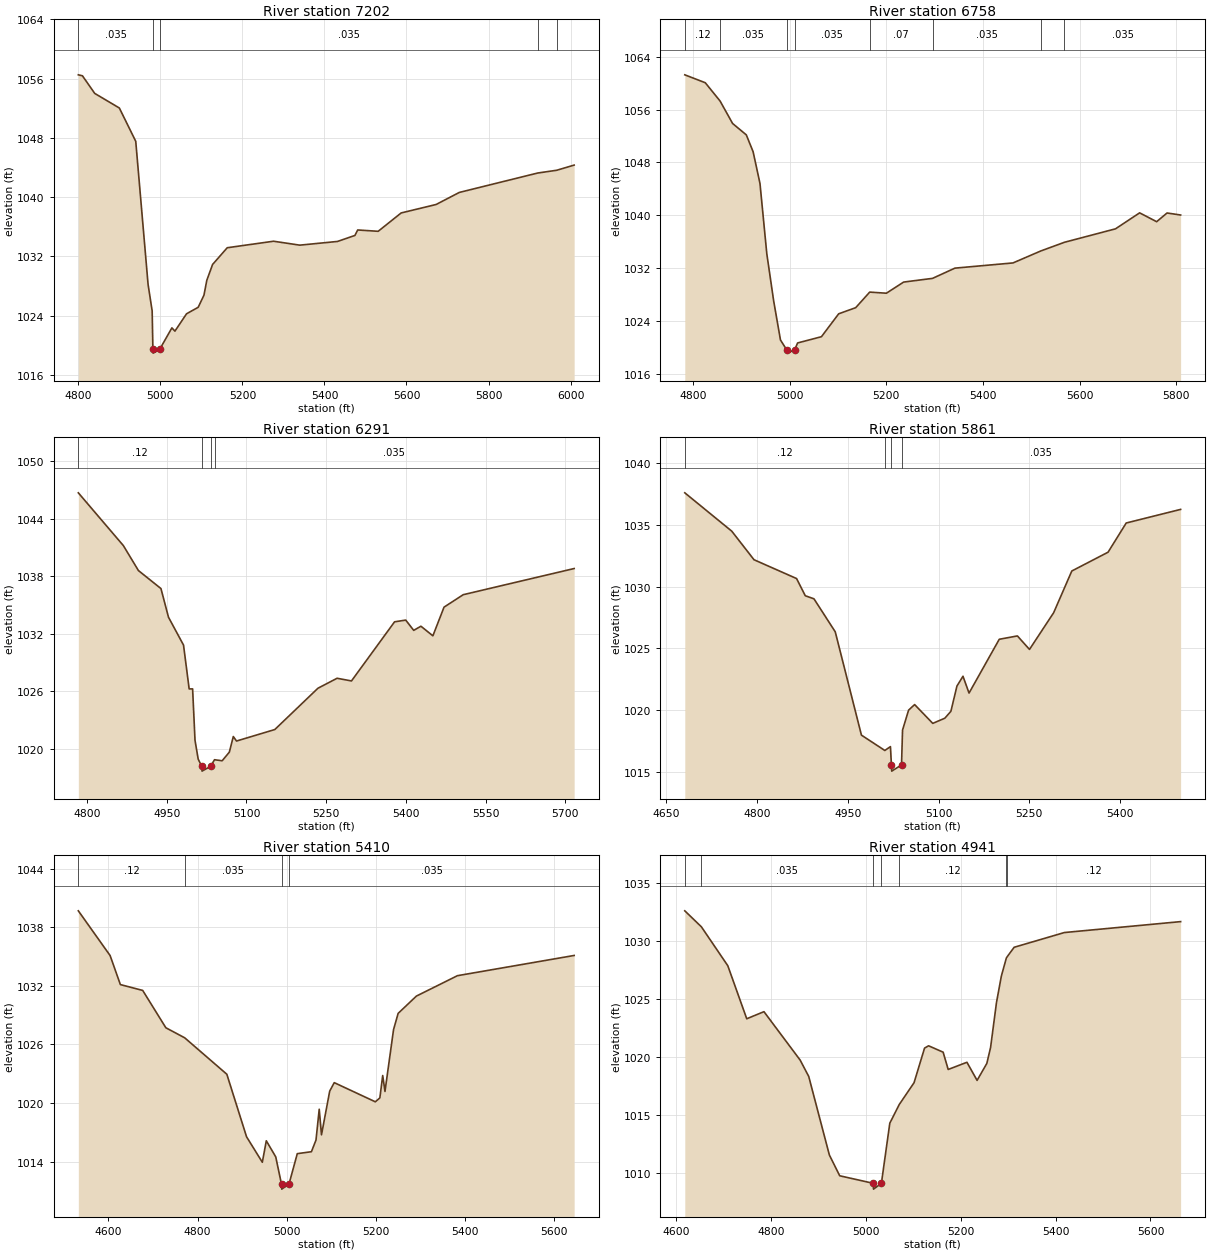
Type RM Length L Ch R = 1 ,7202    ,444,444,444
BEGIN DESCRIPTION:
Swine Creek 14.0
END DESCRIPTION:
XS GIS Cut Line= 3
      2151625.05       13860375.        2151425.       13860375.
       2150739.4     13859635.05
#Sta/Elev= 30
    4800 1056.52    4810 1056.39    4840 1054.01    4900 1052.04    4940 1047.54
    4970 1028.24    4980 1024.64  4981.8 1019.44  4982.3 1018.94  4998.3 1019.44
  5028.1 1022.35  5035.5 1021.91  5063.8 1024.25  5092.2 1025.13  5106.3 1026.77
  5113.2 1028.77  5127.3 1030.91    5163 1033.17  5275.9 1034.05  5339.9 1033.52
  5431.8 1034.02  5474.3 1034.83  5481.1 1035.57    5531 1035.39  5587.1 1037.87
  5672.2 1039.01  5728.9 1040.64  5919.9 1043.26  5966.1 1043.63  6008.8 1044.33
#Mann= 5 ,-1 , 0
    4800    .035       0  4981.8    .035       0  4998.3    .035       0
  5919.9     .07       0  5966.1    .035       0
Bank Sta=4981.8,4998.3
XS Rating Curve= 0 ,0
Exp/Cntr=0.3,0.1

Type RM Length L Ch R = 1 ,6758    ,467,467,467
BEGIN DESCRIPTION:
Swine Creek 13.0
END DESCRIPTION:
XS GIS Cut Line= 3
      2151825.01     13860175.01        2151675.       13860025.
      2151074.99     13859474.99
#Sta/Elev= 30
  4782.9 1061.27  4825.3 1060.07  4855.9  1057.3  4881.9 1053.89  4910.2 1052.17
  4924.3 1049.61  4938.5  1044.8  4952.6 1034.16  4966.8 1027.01  4980.9 1021.08
  4993.8 1019.59  4994.3 1019.09  5010.4 1019.59  5016.3 1020.63  5065.7 1021.58
  5101.4 1025.05  5136.6 1025.98  5165.6 1028.34  5200.1 1028.17  5235.8 1029.86
  5295.6 1030.42  5341.9 1031.97  5462.1 1032.76  5519.9 1034.58  5568.6 1035.89
  5674.3 1037.93  5724.2 1040.35  5759.4 1039.01  5780.9 1040.33    5809 1040.02
#Mann= 8 ,-1 , 0
  4782.9     .12       0  4855.9    .035       0  4993.8    .035       0
  5010.4    .035       0  5165.6     .07       0  5295.6    .035       0
  5519.9     .07       0  5568.6    .035       0
Bank Sta=4993.8,5010.4
XS Rating Curve= 0 ,0
Exp/Cntr=0.3,0.1

Type RM Length L Ch R = 1 ,6291    ,430,430,430
BEGIN DESCRIPTION:
Swine Creek 12.0
END DESCRIPTION:
XS GIS Cut Line= 3
      2152024.97     13859774.97        2151875.       13859625.
        2151275.       13859225.
#Sta/Elev= 30
  4783.6 1046.69  4868.4 1041.18  4896.7 1038.58  4939.1  1036.7  4953.3 1033.71
  4981.6  1030.8  4992.2 1026.23  4998.7 1026.23  5003.2 1020.87  5009.2  1018.9
  5015.9 1018.15  5016.4 1017.65  5032.5 1018.15  5039.9 1018.84  5054.3 1018.73
  5067.8 1019.63  5075.3 1021.26  5081.3 1020.79  5153.4 1021.99  5234.6  1026.3
  5270.6 1027.34  5297.7 1027.06  5378.8 1033.23  5399.8 1033.41  5414.8 1032.34
  5428.4 1032.77  5450.9 1031.77  5471.9 1034.76    5508 1036.06  5716.8 1038.79
#Mann= 4 ,-1 , 0
  4783.6     .12       0  5015.9     .05       0  5032.5     .12       0
  5039.9    .035       0
Bank Sta=5015.9,5032.5
XS Rating Curve= 0 ,0
Exp/Cntr=0.3,0.1

Type RM Length L Ch R = 1 ,5861    ,451,451,451
BEGIN DESCRIPTION:
Swine Creek 11.0
END DESCRIPTION:
XS GIS Cut Line= 3
      2152225.01     13859425.01        2151975.       13859225.
      2151474.97       13859225.
#Sta/Elev= 30
  4680.3 1037.58    4758 1034.48  4794.8 1032.17  4865.2 1030.65  4879.6 1029.26
    4894 1029.01  4929.2 1026.34  4972.5 1017.99  5011.2 1016.75  5020.5 1017.06
  5022.1 1015.58  5022.6 1015.08  5038.8 1015.58  5040.5  1018.4  5050.5 1020.01
  5060.5 1020.46  5090.5 1018.94  5110.5 1019.36  5120.5 1019.92  5130.5 1021.96
  5140.5 1022.75  5150.5 1021.39  5200.5 1025.74  5230.5 1026.01  5250.5 1024.92
  5290.5 1027.89  5320.5 1031.26  5380.5 1032.78  5410.5 1035.14  5500.5 1036.24
#Mann= 4 ,-1 , 0
  4680.3     .12       0  5011.2    .035       0  5022.1     .05       0
  5038.8    .035       0
Bank Sta=5022.1,5038.8
XS Rating Curve= 0 ,0
Exp/Cntr=0.3,0.1

Type RM Length L Ch R = 1 ,5410    ,469,469,469
BEGIN DESCRIPTION:
Swine Creek 10.0
END DESCRIPTION:
XS GIS Cut Line= 3
      2152524.98     13859074.99        2152125.       13858825.
      2151499.13     13858960.74
#Sta/Elev= 30
  4532.7 1039.68    4604  1035.1    4627 1032.13  4677.1 1031.53    4729 1027.71
  4771.3 1026.68  4865.8 1022.95    4910 1016.55  4945.4 1013.94  4954.3 1016.14
  4975.5 1014.49  4988.4 1011.69  4988.9 1011.19  5005.1 1011.69  5023.8 1014.82
  5055.5 1015.02  5065.8 1016.22    5073 1019.37  5078.1 1016.75  5096.5 1021.22
  5106.7 1022.09  5198.8 1020.13    5209 1020.53  5215.4 1022.82  5220.5 1021.19
  5239.7 1027.52    5250 1029.18  5290.9 1030.95    5383 1033.04  5644.8 1035.11
#Mann= 4 ,-1 , 0
  4532.7     .12       0  4771.3    .035       0  4988.4    .035       0
  5005.1    .035       0
Bank Sta=4988.4,5005.1
XS Rating Curve= 0 ,0
Exp/Cntr=0.3,0.1

Type RM Length L Ch R = 1 ,4941    ,526,526,526
BEGIN DESCRIPTION:
Swine Creek 9.0
END DESCRIPTION:
XS GIS Cut Line= 3
      2152624.99     13858874.99        2152475.       13858525.
      2151825.51     13858387.81
#Sta/Elev= 30
  4618.9 1032.62  4653.9 1031.24  4709.5 1027.89  4749.4 1023.32  4785.7 1023.93
  4861.9 1019.76    4880 1018.35  4923.5 1011.58  4945.3 1009.79    5016 1009.14
  5016.5 1008.64  5033.1 1009.14  5050.8 1014.32  5070.7 1015.93  5101.9 1017.81
    5124 1020.79  5132.5 1020.99  5163.2 1020.44  5173.8 1018.95  5213.3 1019.57
  5234.7 1018.01  5255.2 1019.47  5263.1 1020.84  5275.6 1024.73  5285.9 1027.01
  5296.4 1028.56  5298.2 1028.67  5312.8 1029.48  5418.7 1030.75  5663.5 1031.69
#Mann= 7 ,-1 , 0
  4618.9     .12       0  4653.9    .035       0    5016    .035       0
  5033.1    .035       0  5070.7     .12       0  5296.4    .035       0
  5298.2     .12       0
Bank Sta=5016,5033.1
XS Rating Curve= 0 ,0
Exp/Cntr=0.3,0.1

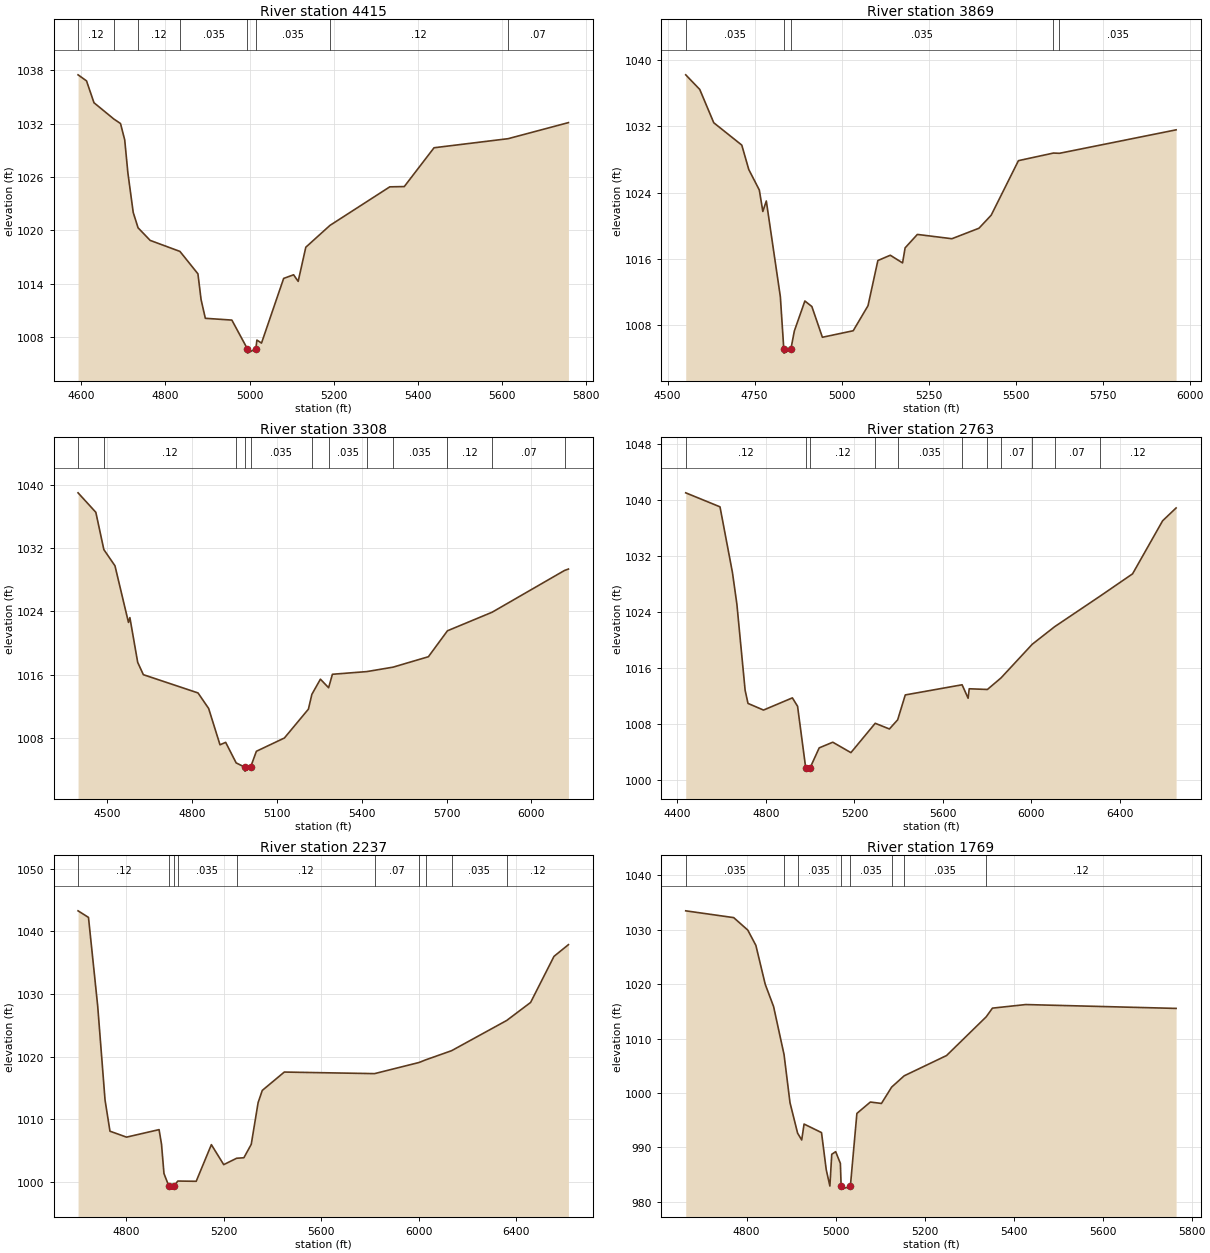
Type RM Length L Ch R = 1 ,4415    ,546,546,546
BEGIN DESCRIPTION:
Swine Creek 8.0
END DESCRIPTION:
XS GIS Cut Line= 3
        2152975.     13858824.97        2152925.       13858425.
      2152624.99     13857724.97
#Sta/Elev= 30
  4592.7  1037.5  4612.8 1036.82  4630.5 1034.36  4677.8 1032.52  4693.5 1032.02
  4703.5 1030.18  4711.1 1026.44  4723.7 1022.01  4735.2 1020.28    4764 1018.86
  4834.7 1017.62  4877.4  1015.1  4884.9 1012.19    4895 1010.09    4958 1009.89
  4994.7 1006.67  4995.2 1006.17    5015 1006.67  5017.5 1007.64  5028.4  1007.3
    5081 1014.58  5104.6 1014.99  5115.5 1014.25  5133.6 1018.09    5191 1020.55
  5333.1 1024.89  5367.5 1024.92  5438.2 1029.29    5614 1030.31  5757.4 1032.12
#Mann= 8 ,-1 , 0
  4592.7     .12       0  4677.8    .035       0  4735.2     .12       0
  4834.7    .035       0  4994.7    .035       0    5015    .035       0
    5191     .12       0    5614     .07       0
Bank Sta=4994.7,5015
XS Rating Curve= 0 ,0
Exp/Cntr=0.3,0.1

Type RM Length L Ch R = 1 ,3869    ,561,561,561
BEGIN DESCRIPTION:
Swine Creek 7.0
END DESCRIPTION:
XS GIS Cut Line= 3
        2153325.     13858825.02        2153375.       13858375.
      2152725.03     13857675.03
#Sta/Elev= 30
    4552 1038.25  4592.3 1036.48  4632.5 1032.45    4713 1029.74  4733.1 1026.78
  4763.3 1024.31  4773.4 1021.71  4783.4 1022.98  4823.7 1011.39  4833.6 1005.06
  4834.1 1004.56    4854 1005.06  4863.9 1007.24  4894.1 1010.87  4914.2  1010.2
  4944.4 1006.48  5032.9 1007.27  5075.4  1010.3  5103.7 1015.77  5139.4 1016.41
  5174.6 1015.48  5181.9  1017.3  5217.1 1018.93  5316.3 1018.41    5394 1019.68
  5429.1 1021.26  5507.3 1027.86  5607.9 1028.78  5625.1 1028.75    5960 1031.59
#Mann= 5 ,-1 , 0
    4552    .035       0  4833.6    .035       0    4854    .035       0
  5607.9     .07       0  5625.1    .035       0
Bank Sta=4833.6,4854
XS Rating Curve= 0 ,0
Exp/Cntr=0.3,0.1

Type RM Length L Ch R = 1 ,3308    ,545,545,545
BEGIN DESCRIPTION:
Swine Creek 6.0
END DESCRIPTION:
XS GIS Cut Line= 3
        2153925.     13858875.04        2153875.       13858275.
        2153075.       13857475.
#Sta/Elev= 30
  4397.3 1038.99  4460.1 1036.53  4488.5 1031.81  4527.8 1029.76  4575.5  1022.6
  4580.5 1023.21  4608.1 1017.55  4628.1 1015.99  4821.3 1013.68  4858.9 1011.72
  4899.1 1007.12  4919.1 1007.43  4956.2 1004.83  4986.7 1004.29  4987.2 1003.79
  5007.1 1004.29  5027.7  1006.3  5126.7 1007.98  5211.6 1011.63  5223.8  1013.5
    5254 1015.42    5283 1014.34  5296.4 1016.04  5418.2 1016.38  5510.8 1016.94
  5635.8 1018.26  5703.1 1021.54  5861.1 1023.89  6116.9 1029.17  6130.8 1029.35
#Mann= 12 ,-1 , 0
  4397.3    .035       0  4488.5     .12       0  4956.2    .035       0
  4986.7    .035       0  5007.1    .035       0  5223.8     .07       0
    5283    .035       0  5418.2     .07       0  5510.8    .035       0
  5703.1     .12       0  5861.1     .07       0  6116.9     .12       0
Bank Sta=4986.7,5007.1
XS Rating Curve= 0 ,0
Exp/Cntr=0.3,0.1

Type RM Length L Ch R = 1 ,2763    ,526,526,526
BEGIN DESCRIPTION:
Swine Creek 5.0
END DESCRIPTION:
XS GIS Cut Line= 3
      2154423.17     13858785.56        2154375.       13858225.
       2154017.1     13856609.29
#Sta/Elev= 30
  4437.3 1040.99  4592.3 1038.99  4648.6 1029.61  4668.7 1025.08  4705.9  1012.8
  4718.9 1010.92  4789.1 1009.97  4919.6 1011.71  4943.1 1010.51  4979.7 1001.75
  4980.2 1001.25  5000.1 1001.75  5040.9 1004.57  5102.3 1005.38  5184.3 1003.89
  5294.2 1008.08  5358.4 1007.27  5395.7 1008.58  5430.1 1012.13  5687.1 1013.58
  5714.2 1011.66  5719.3 1013.01  5801.5 1012.91  5863.4 1014.57  6004.4 1019.37
  6105.8 1021.88  6308.8 1026.19  6457.9 1029.42  6593.9    1037  6654.8 1038.83
#Mann= 11 ,-1 , 0
  4437.3     .12       0  4979.7    .035       0  5000.1     .12       0
  5294.2     .12       0  5395.7    .035       0  5687.1     .07       0
  5801.5    .035       0  5863.4     .07       0  6004.4    .035       0
  6105.8     .07       0  6308.8     .12       0
Bank Sta=4979.7,5000.1
XS Rating Curve= 0 ,0
Exp/Cntr=0.3,0.1

Type RM Length L Ch R = 1 ,2237    ,468,468,468
BEGIN DESCRIPTION:
Swine Creek 4.0
END DESCRIPTION:
XS GIS Cut Line= 3
        2154875.     13858474.99        2154825.       13858075.
      2154125.01     13856625.02
#Sta/Elev= 30
  4601.4 1043.26  4644.2 1042.21    4682 1028.07  4712.2 1013.05  4732.4 1008.08
  4800.4 1007.13    4934 1008.33    4944    1006  4954.1 1001.32    4974  999.33
  4974.5  998.83  4994.7  999.33  5011.1 1000.12  5086.4 1000.08  5148.7 1005.93
  5199.4 1002.74  5252.5 1003.76  5282.1 1003.84  5312.4 1005.98  5340.6 1012.64
  5357.7 1014.59  5448.1 1017.52  5818.9 1017.27  6001.5 1019.05  6028.7 1019.47
  6134.9 1020.93  6361.3 1025.76  6459.2 1028.63  6555.3 1035.99  6614.6 1037.86
#Mann= 10 ,-1 , 0
  4601.4     .12       0    4974     .05       0  4994.7     .12       0
  5011.1    .035       0  5252.5     .12       0  5818.9     .07       0
  6001.5    .035       0  6028.7     .07       0  6134.9    .035       0
  6361.3     .12       0
Bank Sta=4974,4994.7
XS Rating Curve= 0 ,0
Exp/Cntr=0.3,0.1

Type RM Length L Ch R = 1 ,1769    ,575,575,575
BEGIN DESCRIPTION:
Swine Creek 3.0
END DESCRIPTION:
XS GIS Cut Line= 3
      2155323.34     13858204.48      2155219.15     13857891.89
      2154948.88     13857168.42
#Sta/Elev= 30
  4663.3  1033.5  4771.1 1032.25  4802.7 1029.96  4820.9 1027.15    4842 1019.97
  4860.7  1015.9  4884.2 1007.07  4897.6  998.21  4914.7   992.6  4923.9  991.35
  4929.2  994.28  4968.4  992.71    4979  985.89  4987.2  982.88  4991.4  988.72
  5000.2   989.2  5010.8  987.04  5012.5  982.81    5013  982.31  5033.2  982.81
  5047.9  996.24  5078.2  998.33  5103.1  998.07    5126 1001.08  5154.1 1003.15
  5249.3 1006.88  5338.5 1014.01  5352.4  1015.6  5427.2 1016.26  5765.1 1015.55
#Mann= 8 ,-1 , 0
  4663.3    .035       0  4884.2     .12       0  4914.7    .035       0
  5012.5    .035       0  5033.2    .035       0    5126     .12       0
  5154.1    .035       0  5338.5     .12       0
Bank Sta=5012.5,5033.2
XS Rating Curve= 0 ,0
Exp/Cntr=0.3,0.1

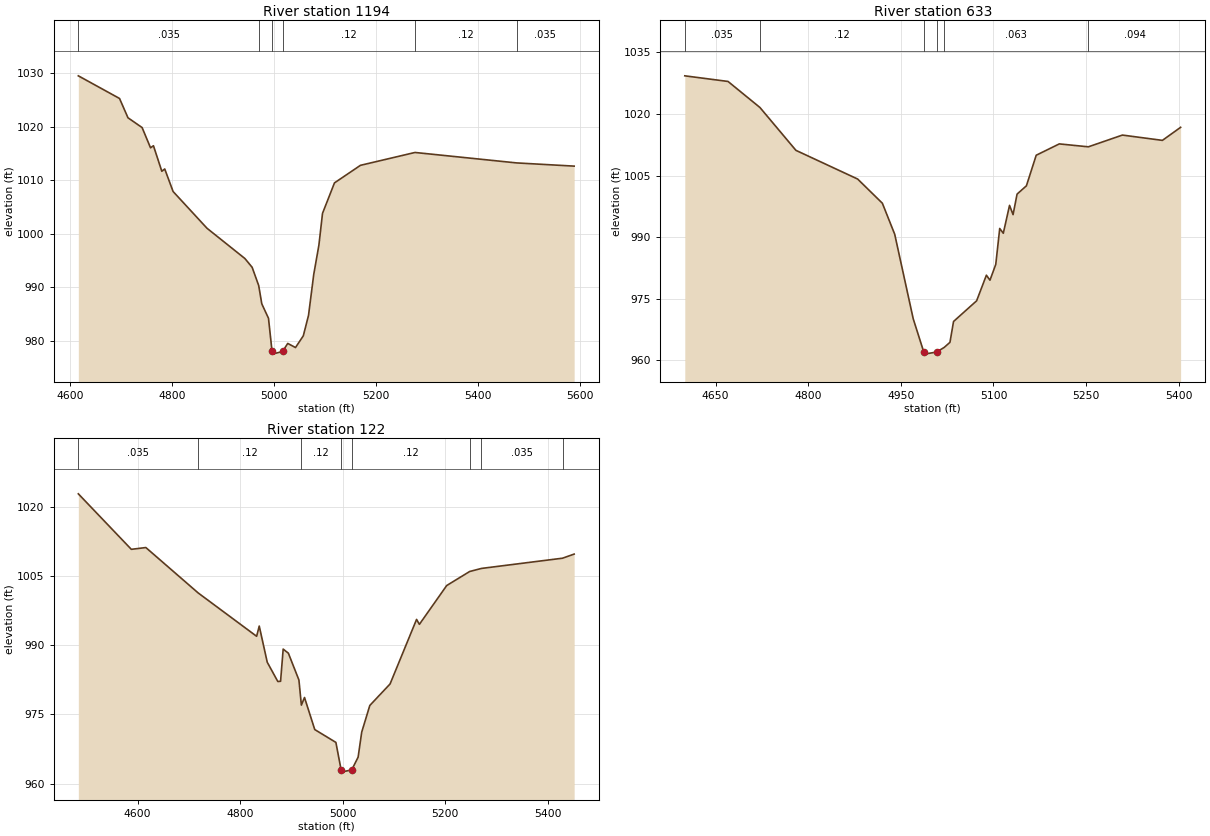
Type RM Length L Ch R = 1 ,1194    ,561,561,561
BEGIN DESCRIPTION:
Swine Creek 2.0
END DESCRIPTION:
XS GIS Cut Line= 3
       2155494.2     13858004.41      2155656.73     13857691.86
      2155769.24     13857083.45
#Sta/Elev= 30
  4616.9 1029.51  4697.6 1025.28  4714.1 1021.68  4741.8 1019.85  4758.3 1016.07
    4764 1016.46  4780.4 1011.69  4786.1 1012.12  4802.5 1007.91  4868.9 1001.05
  4943.1   995.4  4957.3  993.76  4970.1  990.36  4976.2  986.94  4989.3  984.24
  4996.3  978.05  4996.8  977.55    5017  978.05    5027  979.55  5042.2  978.78
  5057.5  980.97  5067.7  984.79  5077.9  992.42    5088  997.89  5095.1 1003.83
  5118.5 1009.52  5169.4  1012.8  5276.2  1015.2  5475.2 1013.25  5587.9 1012.65
#Mann= 6 ,-1 , 0
  4616.9    .035       0  4970.1     .12       0  4996.3     .05       0
    5017     .12       0  5276.2     .12       0  5475.2    .035       0
Bank Sta=4996.3,5017
XS Rating Curve= 0 ,0
Exp/Cntr=0.3,0.1

Type RM Length L Ch R = 1 ,633     ,511,511,511
BEGIN DESCRIPTION:
Swine Creek 1.0
END DESCRIPTION:
XS GIS Cut Line= 3
        2155525.       13858025.        2155925.       13858025.
      2156274.99       13857825.
#Sta/Elev= 30
    4600 1029.31    4670 1027.94  4721.7  1021.6    4780 1011.16    4880 1004.17
    4920  998.28    4940  990.73    4970  970.13  4987.1  962.03  4987.6  961.53
  5007.9  962.03  5020.3  963.18  5029.5  964.41  5035.3  969.48  5072.7  974.52
  5088.5  980.75  5094.3  979.54  5103.7  983.39  5110.1  992.13  5115.9  990.97
    5126  997.76  5131.7   995.5  5138.2  1000.5  5153.3 1002.52  5169.2 1009.97
  5206.6 1012.73  5253.7 1012.02  5308.8 1014.88  5373.6 1013.59  5403.1 1016.77
#Mann= 6 ,-1 , 0
    4600    .035       0  4721.7     .12       0  4987.1     .05       0
  5007.9     .12       0  5020.3    .063       0  5253.7    .094       0
Bank Sta=4987.1,5007.9
XS Rating Curve= 0 ,0
Exp/Cntr=0.3,0.1

Type RM Length L Ch R = 1 ,122     ,0,0,0
BEGIN DESCRIPTION:
Swine Creek 0.0
END DESCRIPTION:
XS GIS Cut Line= 3
      2155407.07     13858385.96      2155907.72     13858508.78
      2156099.98     13858100.04
#Sta/Elev= 30
  4484.5 1022.85  4587.9 1010.81  4616.2  1011.2  4718.2 1001.36  4832.3  991.95
  4837.4  994.17    4853  986.33  4873.6  982.15    4879  982.19  4884.1  989.17
  4894.2  988.29  4914.8  982.47  4919.6  977.02  4925.7  978.68  4945.7  971.72
  4986.9  968.94  4997.1  962.99  4997.6  962.49  5017.9  962.99  5030.3  965.75
  5037.3  971.17  5053.1  976.95  5092.6  981.61  5144.3  995.61  5149.8  994.54
  5203.1 1002.96  5247.8    1006  5270.9 1006.67  5429.1 1008.89  5451.7 1009.78
#Mann= 8 ,-1 , 0
  4484.5    .035       0  4718.2     .12       0  4919.6     .12       0
  4997.1     .05       0  5017.9     .12       0  5247.8     .12       0
  5270.9    .035       0  5429.1    .063       0
Bank Sta=4997.1,5017.9
XS Rating Curve= 0 ,0
Exp/Cntr=0.3,0.1

Chan Stop Cuts=-1
Use User Specified Reach Order=0
Composite Channel Slope=5