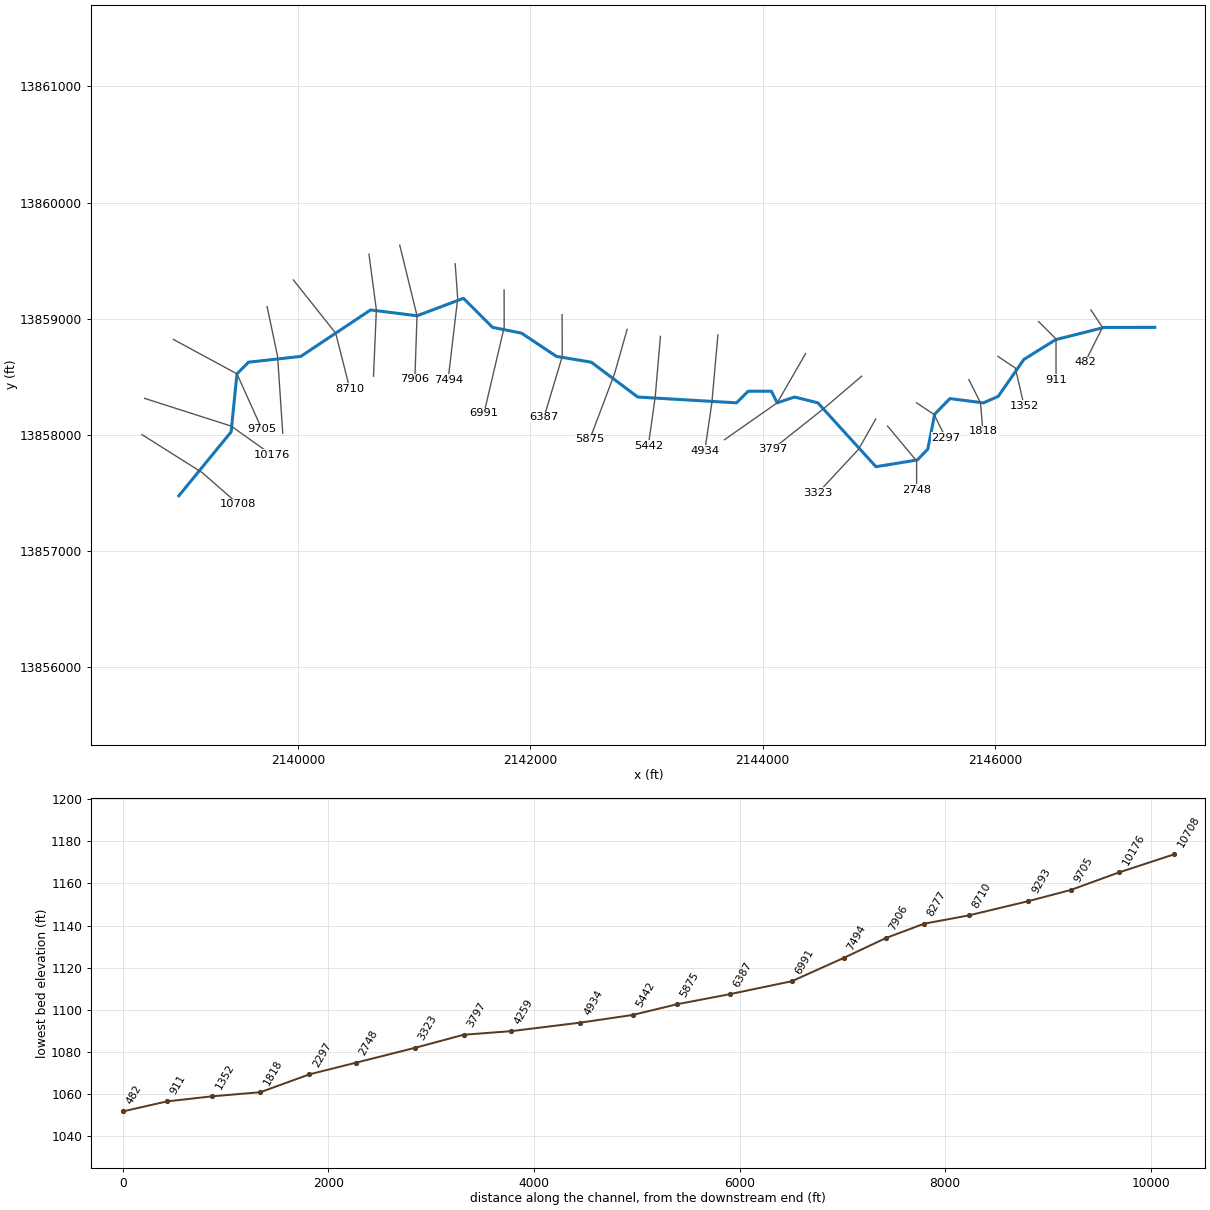
--- Swine Tributary 2.prj (project) ---

Proj Title=Swine Tributary 2 Base Level Engineering
Current Plan=p01
Default Exp/Contr=0.3,0.1
English Units
Geom File=g01
Flow File=f01
Plan File=p01
BEGIN DESCRIPTION:
Swine Tributary 2
END DESCRIPTION:

--- Swine Tributary 2.p01 (plan) ---

Plan Title=Multiple Run
Short Identifier=Multiple
Geom File=g01
Flow File=f01
Subcritical Flow
K Sum by GR= 0
Std Step Tol= 0.01
Critical Tol= 0.01
Num of Std Step Trials= 20
Max Error Tol= 0.3
Flow Tol Ratio= 0.001
Split Flow NTrial= 30
Split Flow Tol= 0.02
Split Flow Ratio= 0.02
Log Output Level= 0
Friction Slope Method= 1
Unsteady Friction Slope Method= 2
Unsteady Bridges Friction Slope Method= 1
Parabolic Critical Depth
Global Vel Dist=  1 , 1 , 1
Global Log Level= 0
CheckData=True
Encroach Param= -1, 0, 0, 0
BEGIN DESCRIPTION:
Multiple Run
END DESCRIPTION:

--- Swine Tributary 2.f01 (steady flow) ---

Flow Title=Multiple
Number of Profiles=7
Profile Names=10-year,25-year,50-year,1pct_min,100-year,1pct_plu,500-year
River Rch & RM= Swine Tributary ,Reach-1,10708
     191     286     367     230     458     914     703
River Rch & RM= Swine Tributary ,Reach-1,10176
     715    1185    1622    1077    2149    4288    3733
River Rch & RM= Swine Tributary ,Reach-1,5875
    1278    2188    3061    2073    4136    8253    7480
River Rch & RM= Swine Tributary ,Reach-1,2748
    1347    2307    3229    2186    4362    8703    7885
Boundary for River Rch & Prof#=Swine Tributary ,Reach-1,1
Up Type=0
Dn Type=3
Dn Slope=0.005
Boundary for River Rch & Prof#=Swine Tributary ,Reach-1,2
Up Type=0
Dn Type=3
Dn Slope=0.005
Boundary for River Rch & Prof#=Swine Tributary ,Reach-1,3
Up Type=0
Dn Type=3
Dn Slope=0.005
Boundary for River Rch & Prof#=Swine Tributary ,Reach-1,4
Up Type=0
Dn Type=3
Dn Slope=0.005
Boundary for River Rch & Prof#=Swine Tributary ,Reach-1,5
Up Type=0
Dn Type=3
Dn Slope=0.005
Boundary for River Rch & Prof#=Swine Tributary ,Reach-1,6
Up Type=0
Dn Type=3
Dn Slope=0.005
Boundary for River Rch & Prof#=Swine Tributary ,Reach-1,7
Up Type=0
Dn Type=3
Dn Slope=0.005

--- Swine Tributary 2.g01 (geometry) ---

Geom Title=Existing Conditions

River Reach=Swine Tributary ,Reach-1
Reach XY= 30
      2138975.00     13857475.00      2139425.00     13858025.00
      2139475.00     13858525.00      2139575.00     13858625.00
      2140025.00     13858675.00      2140625.00     13859075.00
      2141025.00     13859025.00      2141425.00     13859175.00
      2141675.00     13858925.00      2141925.00     13858875.00
      2142225.00     13858675.00      2142525.00     13858625.00
      2142925.00     13858325.00      2143775.00     13858275.00
      2143875.00     13858375.00      2144075.00     13858375.00
      2144125.00     13858275.00      2144275.00     13858325.00
      2144475.00     13858275.00      2144975.00     13857725.00
      2145331.08     13857783.13      2145421.39     13857876.48
      2145480.47     13858177.45      2145611.69     13858311.66
      2145900.08     13858274.76      2146027.55     13858330.73
      2146248.18     13858648.71      2146522.58     13858819.46
      2146940.22     13858924.49      2147375.00     13858925.00

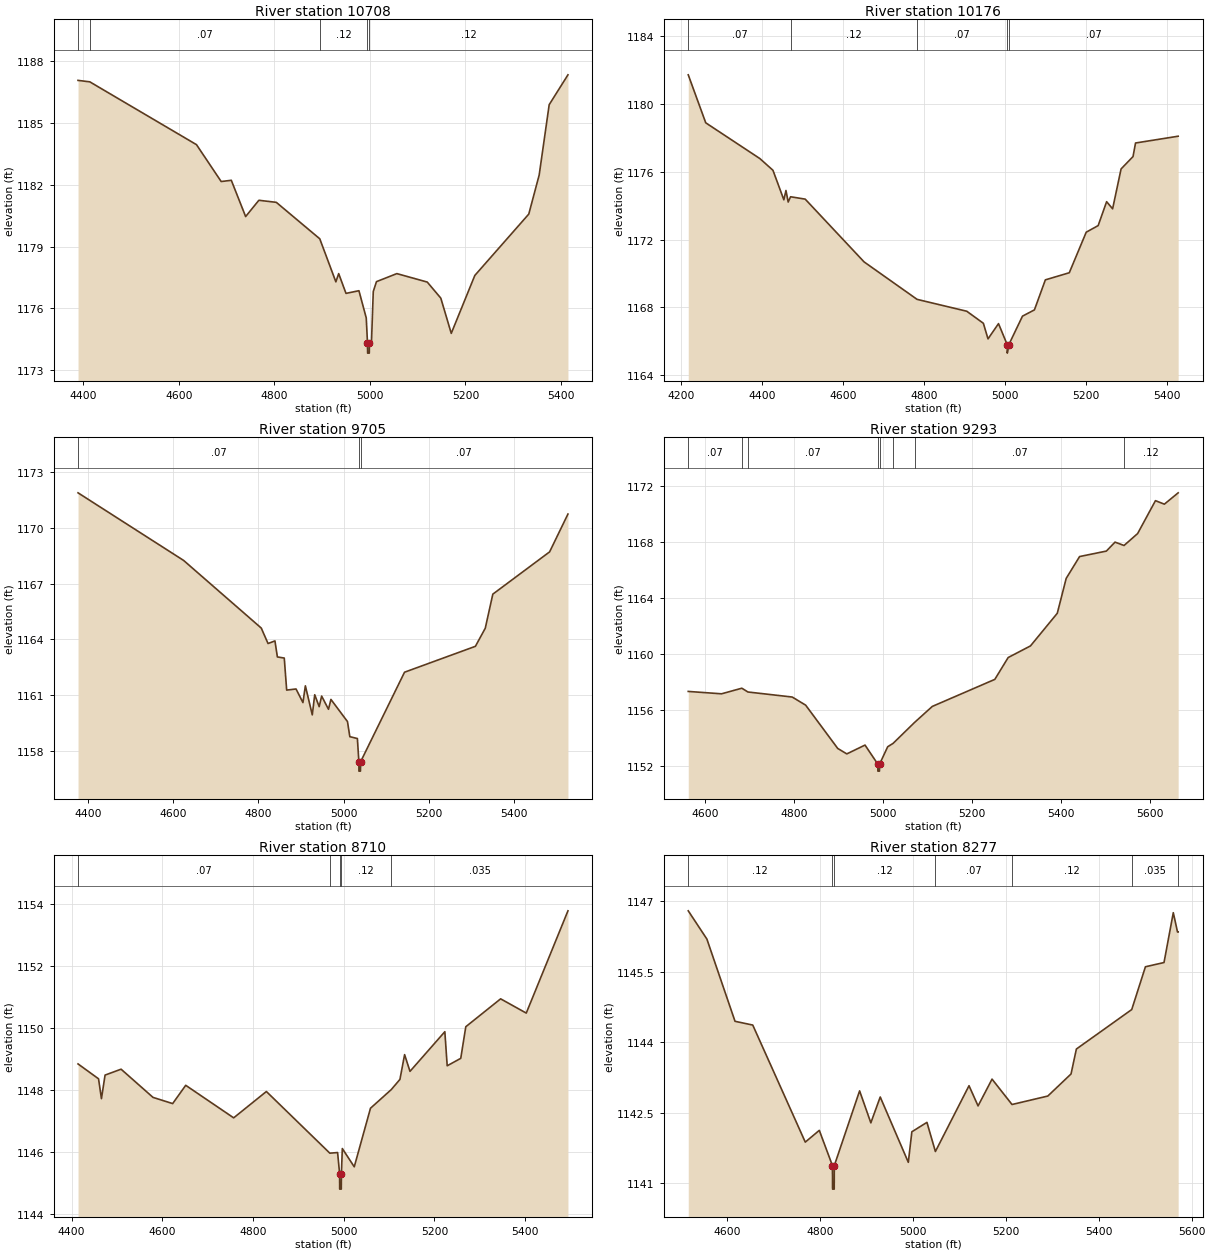
Type RM Length L Ch R = 1,10708,532,532,532
BEGIN DESCRIPTION:
Swine Tributary 2 22.0
END DESCRIPTION:
XS GIS Cut Line= 3
      2138658.24     13858001.01      2139175.00     13857675.00
      2139487.21     13857402.06
#Sta/Elev= 30
  4389.0 1187.07  4413.6 1187.00  4637.0 1183.95  4688.7 1182.16  4709.9 1182.22
  4739.9 1180.46  4767.6 1181.25  4804.1 1181.15  4895.1 1179.38  4928.8 1177.29
  4934.7 1177.69  4950.0 1176.73  4977.1 1176.86  4992.4 1175.54  4995.0 1174.33
  4995.3 1173.83  4998.8 1173.83  4999.0 1174.33  5003.3 1174.33  5007.1 1176.82
  5013.8 1177.30  5056.5 1177.69  5120.1 1177.28  5148.5 1176.50  5170.4 1174.79
  5219.7 1177.60  5332.7 1180.58  5354.5 1182.48  5375.4 1185.89  5414.7 1187.34
#Mann=5,-1,0
  4389.0    0.12       0  4413.6    0.07       0  4895.1    0.12       0
  4995.0    0.05       0  4999.0    0.12       0
Bank Sta=4995,4999
Exp/Cntr=0.3,0.1

Type RM Length L Ch R = 1,10176,471,471,471
BEGIN DESCRIPTION:
Swine Tributary 2 21.0
END DESCRIPTION:
XS GIS Cut Line= 3
      2138679.95     13858313.51      2139425.00     13858075.00
      2139773.64     13857827.43
#Sta/Elev= 30
  4217.7 1181.71  4260.9 1178.88  4394.7 1176.77  4426.9 1176.08  4453.8 1174.34
  4459.0 1174.89  4464.5 1174.21  4470.4 1174.52  4506.5 1174.38  4651.9 1170.68
  4782.8 1168.47  4905.5 1167.77  4946.5 1167.06  4958.0 1166.14  4983.9 1167.04
  5005.4 1165.80  5005.6 1165.30  5009.4 1165.80  5043.1 1167.48  5072.6 1167.85
  5099.6 1169.62  5158.7 1170.04  5200.5 1172.43  5230.0 1172.82  5250.9 1174.23
  5265.7 1173.81  5286.6 1176.16  5316.1 1176.89  5322.3 1177.69  5427.6 1178.09
#Mann=5,-1,0
  4217.7    0.07       0  4470.4    0.12       0  4782.8    0.07       0
  5005.4    0.05       0  5009.4    0.07       0
Bank Sta=5005.4,5009.4
Exp/Cntr=0.3,0.1

Type RM Length L Ch R = 1,9705,412,412,412
BEGIN DESCRIPTION:
Swine Tributary 2 20.0
END DESCRIPTION:
XS GIS Cut Line= 3
      2138927.33     13858821.33      2139475.00     13858525.00
      2139690.60     13858045.76
#Sta/Elev= 30
  4377.3 1171.87  4624.8 1168.24  4806.7 1164.61  4822.6 1163.78  4838.8 1163.92
  4844.5 1163.06  4860.6 1163.00  4866.3 1161.28  4888.2 1161.34  4904.4 1160.61
  4910.1 1161.51  4926.3 1159.95  4932.0 1161.03  4942.5 1160.39  4948.2 1160.96
  4964.3 1160.25  4970.0 1160.78  5008.8 1159.59  5014.3 1158.78  5032.0 1158.68
  5035.5 1157.43  5035.7 1156.93  5039.2 1156.93  5039.5 1157.43  5142.5 1162.24
  5308.6 1163.63  5331.7 1164.60  5349.4 1166.43  5482.5 1168.70  5525.5 1170.73
#Mann=3,-1,0
  4377.3    0.07       0  5035.5    0.05       0  5039.5    0.07       0
Bank Sta=5035.5,5039.5
Exp/Cntr=0.3,0.1

Type RM Length L Ch R = 1,9293,583,583,583
BEGIN DESCRIPTION:
Swine Tributary 2 19.0
END DESCRIPTION:
XS GIS Cut Line= 3
      2139734.60     13859103.47      2139825.00     13858675.00
      2139869.15     13858014.07
#Sta/Elev= 30
  4562.1 1157.31  4636.9 1157.14  4682.4 1157.54  4696.1 1157.27  4795.6 1156.91
  4825.8 1156.33  4897.8 1153.24  4918.2 1152.85  4959.1 1153.48  4987.8 1152.12
  4988.0 1151.62  4991.5 1151.62  4991.8 1152.12  5010.0 1153.36  5022.1 1153.60
  5070.5 1155.10  5110.2 1156.24  5250.6 1158.17  5280.6 1159.73  5330.7 1160.56
  5390.9 1162.89  5410.9 1165.38  5441.0 1166.94  5501.1 1167.33  5520.6 1167.97
  5540.8 1167.73  5571.3 1168.58  5611.4 1170.93  5631.4 1170.68  5662.4 1171.49
#Mann=8,-1,0
  4562.1    0.07       0  4682.4    0.12       0  4696.1    0.07       0
  4987.8    0.05       0  4991.8    0.07       0  5022.1    0.12       0
  5070.5    0.07       0  5540.8    0.12       0
Bank Sta=4987.8,4991.8
Exp/Cntr=0.3,0.1

Type RM Length L Ch R = 1,8710,433,433,433
BEGIN DESCRIPTION:
Swine Tributary 2 18.0
END DESCRIPTION:
XS GIS Cut Line= 3
      2139960.33     13859333.45      2140325.00     13858875.00
      2140446.42     13858395.95
#Sta/Elev= 30
  4414.2 1148.85  4459.4 1148.37  4465.8 1147.73  4473.8 1148.49  4509.1 1148.68
  4579.5 1147.77  4622.8 1147.57  4651.6 1148.16  4757.3 1147.11  4829.4 1147.96
  4969.3 1145.97  4986.4 1145.99  4990.8 1145.31  4991.0 1144.81  4994.5 1144.81
  4994.8 1145.31  4996.8 1146.12  5023.1 1145.53  5058.9 1147.42  5104.6 1148.02
  5123.8 1148.35  5134.1 1149.15  5146.0 1148.61  5222.8 1149.89  5228.0 1148.79
  5257.9 1149.03  5269.0 1150.05  5345.8 1150.95  5402.3 1150.49  5494.2 1153.79
#Mann=5,-1,0
  4414.2    0.07       0  4969.3    0.12       0  4990.8    0.05       0
  4994.8    0.12       0  5104.6   0.035       0
Bank Sta=4990.8,4994.8
Exp/Cntr=0.3,0.1

Type RM Length L Ch R = 1,8277,371,371,371
BEGIN DESCRIPTION:
Swine Tributary 2 17.0
END DESCRIPTION:
XS GIS Cut Line= 3
      2140611.35     13859554.80      2140675.00     13859075.00
      2140650.40     13858504.53
#Sta/Elev= 30
  4516.0 1146.80  4556.1 1146.20  4616.7 1144.45  4654.9 1144.37  4768.0 1141.88
  4798.2 1142.13  4826.5 1141.38  4826.8 1140.88  4830.3 1140.88  4830.5 1141.38
  4885.0 1142.97  4909.2 1142.29  4929.4 1142.84  4989.9 1141.45  4997.5 1142.10
  5030.0 1142.30  5048.2 1141.68  5120.6 1143.08  5140.1 1142.65  5170.2 1143.22
  5213.2 1142.68  5290.3 1142.86  5340.3 1143.33  5351.8 1143.86  5471.0 1144.70
  5500.5 1145.61  5540.5 1145.70  5560.5 1146.76  5569.6 1146.35  5571.0 1146.35
#Mann=7,-1,0
  4516.0    0.12       0  4826.5    0.05       0  4830.5    0.12       0
  5048.2    0.07       0  5213.2    0.12       0  5471.0   0.035       0
  5569.6    0.12       0
Bank Sta=4826.5,4830.5
Exp/Cntr=0.3,0.1

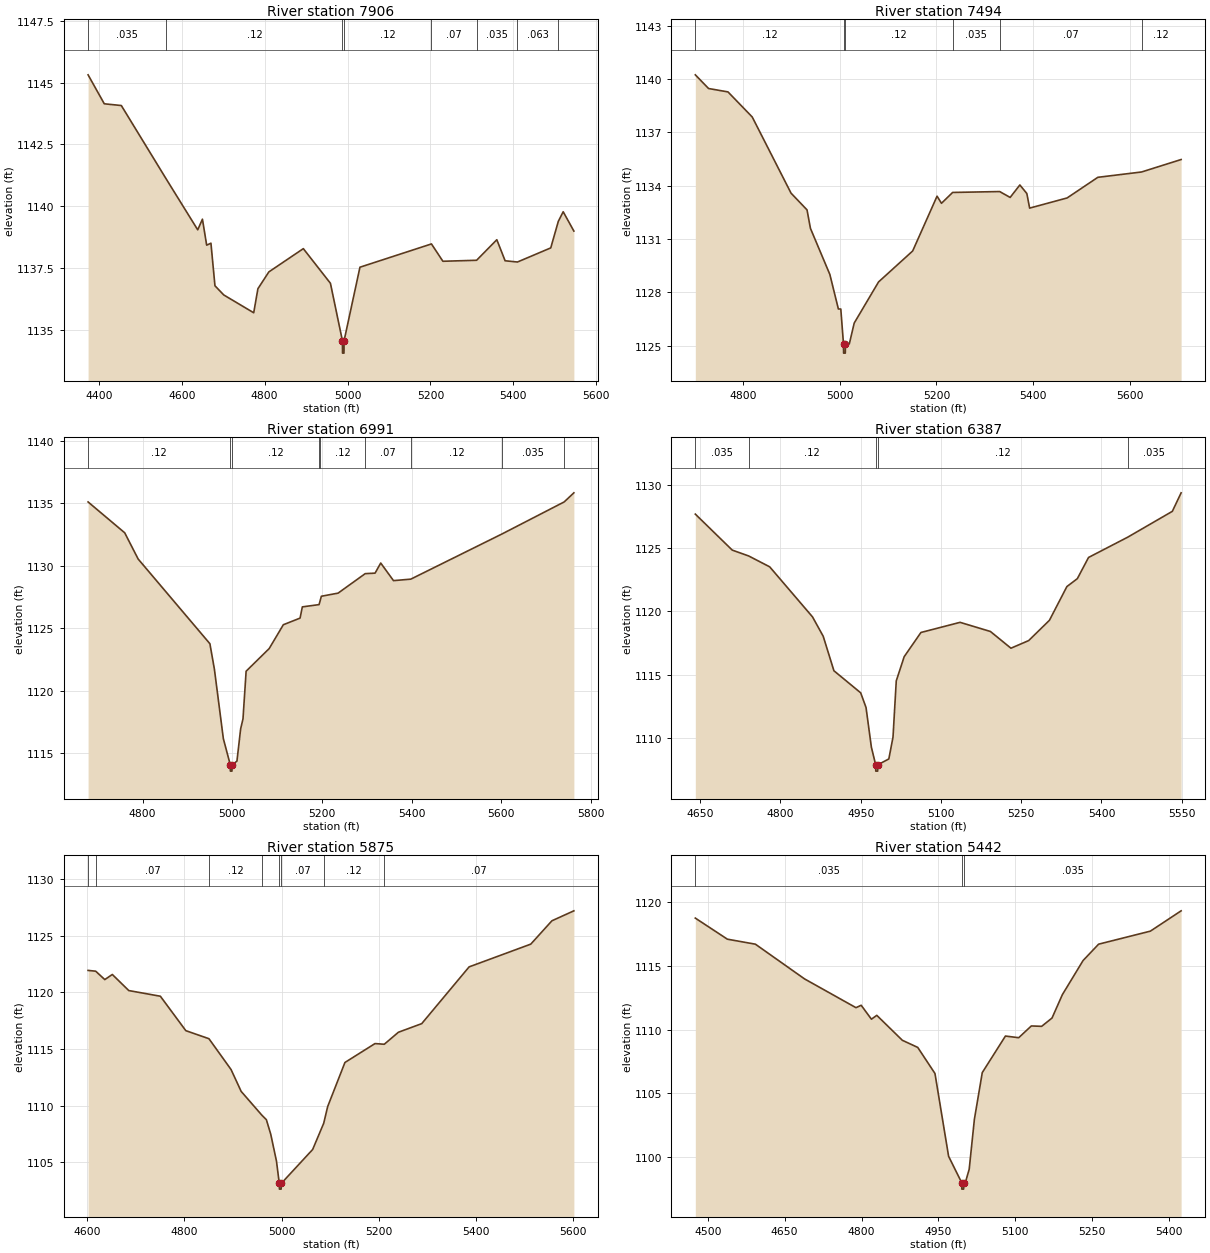
Type RM Length L Ch R = 1,7906,412,412,412
BEGIN DESCRIPTION:
Swine Tributary 2 16.0
END DESCRIPTION:
XS GIS Cut Line= 3
      2140876.11     13859632.93      2141025.00     13859025.00
      2141006.33     13858479.22
#Sta/Elev= 30
  4374.1 1145.31  4413.2 1144.14  4454.3 1144.07  4563.1 1141.09  4638.6 1139.05
  4650.0 1139.48  4660.2 1138.43  4670.5 1138.51  4680.2 1136.79  4701.4 1136.42
  4773.7 1135.70  4783.8 1136.67  4810.2 1137.35  4893.4 1138.29  4958.8 1136.89
  4987.7 1134.57  4988.0 1134.07  4991.5 1134.07  4991.7 1134.57  5030.0 1137.54
  5202.5 1138.48  5230.1 1137.78  5311.4 1137.82  5360.2 1138.65  5380.2 1137.80
  5410.0 1137.75  5490.3 1138.32  5508.5 1139.39  5520.3 1139.78  5546.1 1139.00
#Mann=8,-1,0
  4374.1   0.035       0  4563.1    0.12       0  4987.7    0.05       0
  4991.7    0.12       0  5202.5    0.07       0  5311.4   0.035       0
  5410.0   0.063       0  5508.5   0.035       0
Bank Sta=4987.7,4991.7
Exp/Cntr=0.3,0.1

Type RM Length L Ch R = 1,7494,503,503,503
BEGIN DESCRIPTION:
Swine Tributary 2 15.0
END DESCRIPTION:
XS GIS Cut Line= 3
      2141353.53     13859472.33      2141375.00     13859175.00
      2141292.76     13858474.11
#Sta/Elev= 30
  4701.9 1140.23  4729.3 1139.46  4769.4 1139.27  4819.5 1137.86  4899.7 1133.58
  4932.7 1132.64  4939.8 1131.60  4979.9 1129.01  4997.5 1127.07  5002.5 1127.07
  5008.1 1125.09  5008.3 1124.59  5011.8 1124.59  5012.1 1125.09  5020.1 1125.11
  5030.2 1126.28  5080.5 1128.59  5151.0 1130.33  5201.4 1133.41  5210.5 1133.01
  5233.6 1133.62  5330.8 1133.67  5352.4 1133.34  5372.5 1134.04  5386.9 1133.56
  5392.7 1132.74  5470.1 1133.31  5533.6 1134.47  5624.0 1134.77  5705.7 1135.47
#Mann=6,-1,0
  4701.9    0.12       0  5008.1    0.05       0  5012.1    0.12       0
  5233.6   0.035       0  5330.8    0.07       0  5624.0    0.12       0
Bank Sta=5008.1,5012.1
Exp/Cntr=0.3,0.1

Type RM Length L Ch R = 1,6991,604,604,604
BEGIN DESCRIPTION:
Swine Tributary 2 14.0
END DESCRIPTION:
XS GIS Cut Line= 3
      2141774.54     13859246.70      2141775.00     13858925.00
      2141600.93     13858183.35
#Sta/Elev= 30
  4678.3 1135.11  4760.0 1132.64  4790.0 1130.54  4950.0 1123.76  4960.0 1121.73
  4980.0 1116.16  4995.5 1114.06  4995.7 1113.56  4999.2 1113.56  4999.5 1114.06
  5010.3 1114.36  5018.6 1116.95  5023.8 1117.74  5030.8 1121.56  5082.2 1123.37
  5113.8 1125.28  5151.1 1125.81  5156.2 1126.71  5193.4 1126.89  5194.6 1127.03
  5198.6 1127.56  5235.9 1127.81  5296.4 1129.37  5318.4 1129.41  5331.0 1130.22
  5359.5 1128.81  5398.1 1128.93  5601.7 1132.55  5740.1 1135.11  5761.8 1135.84
#Mann=9,-1,0
  4678.3    0.12       0  4995.5    0.05       0  4999.5    0.12       0
  5193.4   0.035       0  5194.6    0.12       0  5296.4    0.07       0
  5398.1    0.12       0  5601.7   0.035       0  5740.1    0.07       0
Bank Sta=4995.5,4999.5
Exp/Cntr=0.3,0.1

Type RM Length L Ch R = 1,6387,512,512,512
BEGIN DESCRIPTION:
Swine Tributary 2 13.0
END DESCRIPTION:
XS GIS Cut Line= 3
      2142273.67     13859034.00      2142275.00     13858675.00
      2142117.62     13858149.25
#Sta/Elev= 30
  4641.0 1127.67  4710.0 1124.83  4740.6 1124.37  4780.0 1123.51  4860.0 1119.56
  4880.0 1118.03  4900.0 1115.31  4950.0 1113.57  4960.0 1112.41  4970.0 1109.28
  4978.0 1107.89  4978.2 1107.39  4981.7 1107.39  4982.0 1107.89  5002.6 1108.35
  5010.4 1110.07  5016.5 1114.51  5031.3 1116.42  5062.6 1118.33  5135.7 1119.13
  5192.4 1118.41  5230.8 1117.09  5263.9 1117.69  5302.7 1119.29  5335.3 1121.95
  5354.9 1122.58  5375.8 1124.25  5449.0 1125.85  5532.4 1127.89  5548.8 1129.35
#Mann=5,-1,0
  4641.0   0.035       0  4740.6    0.12       0  4978.0    0.05       0
  4982.0    0.12       0  5449.0   0.035       0
Bank Sta=4978,4982
Exp/Cntr=0.3,0.1

Type RM Length L Ch R = 1,5875,433,433,433
BEGIN DESCRIPTION:
Swine Tributary 2 12.0
END DESCRIPTION:
XS GIS Cut Line= 3
      2142833.56     13858908.12      2142725.00     13858525.00
      2142512.40     13857962.00
#Sta/Elev= 30
  4601.8 1121.93  4617.5 1121.86  4636.2 1121.12  4651.7 1121.57  4685.6 1120.15
  4750.6 1119.65  4803.0 1116.61  4850.6 1115.90  4896.1 1113.18  4916.9 1111.25
  4959.5 1109.15  4968.8 1108.75  4977.8 1107.47  4989.6 1105.09  4995.4 1103.12
  4995.7 1102.62  4999.2 1102.62  4999.4 1103.12  5064.1 1106.12  5086.8 1108.43
  5095.0 1109.91  5130.5 1113.80  5192.4 1115.47  5211.5 1115.41  5240.6 1116.47
  5288.6 1117.23  5386.1 1122.24  5513.1 1124.25  5556.6 1126.31  5601.8 1127.19
#Mann=8,-1,0
  4601.8   0.035       0  4617.5    0.07       0  4850.6    0.12       0
  4959.5    0.07       0  4995.4    0.05       0  4999.4    0.07       0
  5086.8    0.12       0  5211.5    0.07       0
Bank Sta=4995.4,4999.4
Exp/Cntr=0.3,0.1

Type RM Length L Ch R = 1,5442,508,508,508
BEGIN DESCRIPTION:
Swine Tributary 2 11.0
END DESCRIPTION:
XS GIS Cut Line= 3
      2143120.02     13858847.36      2143075.00     13858325.00
      2143015.86     13857905.55
#Sta/Elev= 30
  4475.7 1118.72  4538.3 1117.07  4592.9 1116.68  4688.9 1113.96  4789.2 1111.71
  4799.3 1111.90  4819.3 1110.81  4829.8 1111.11  4879.6 1109.16  4909.7 1108.60
  4943.3 1106.56  4969.9 1100.08  4995.5 1098.01  4995.7 1097.51  4999.2 1097.51
  4999.5 1098.01  5002.5 1098.01  5010.1 1099.07  5020.2 1102.97  5035.6 1106.63
  5080.8 1109.49  5106.7 1109.36  5131.3 1110.28  5151.5 1110.25  5171.7 1110.90
  5191.9 1112.73  5232.3 1115.40  5262.6 1116.68  5363.6 1117.70  5423.6 1119.29
#Mann=3,-1,0
  4475.7   0.035       0  4995.5   0.035       0  4999.5   0.035       0
Bank Sta=4995.5,4999.5
Exp/Cntr=0.3,0.1

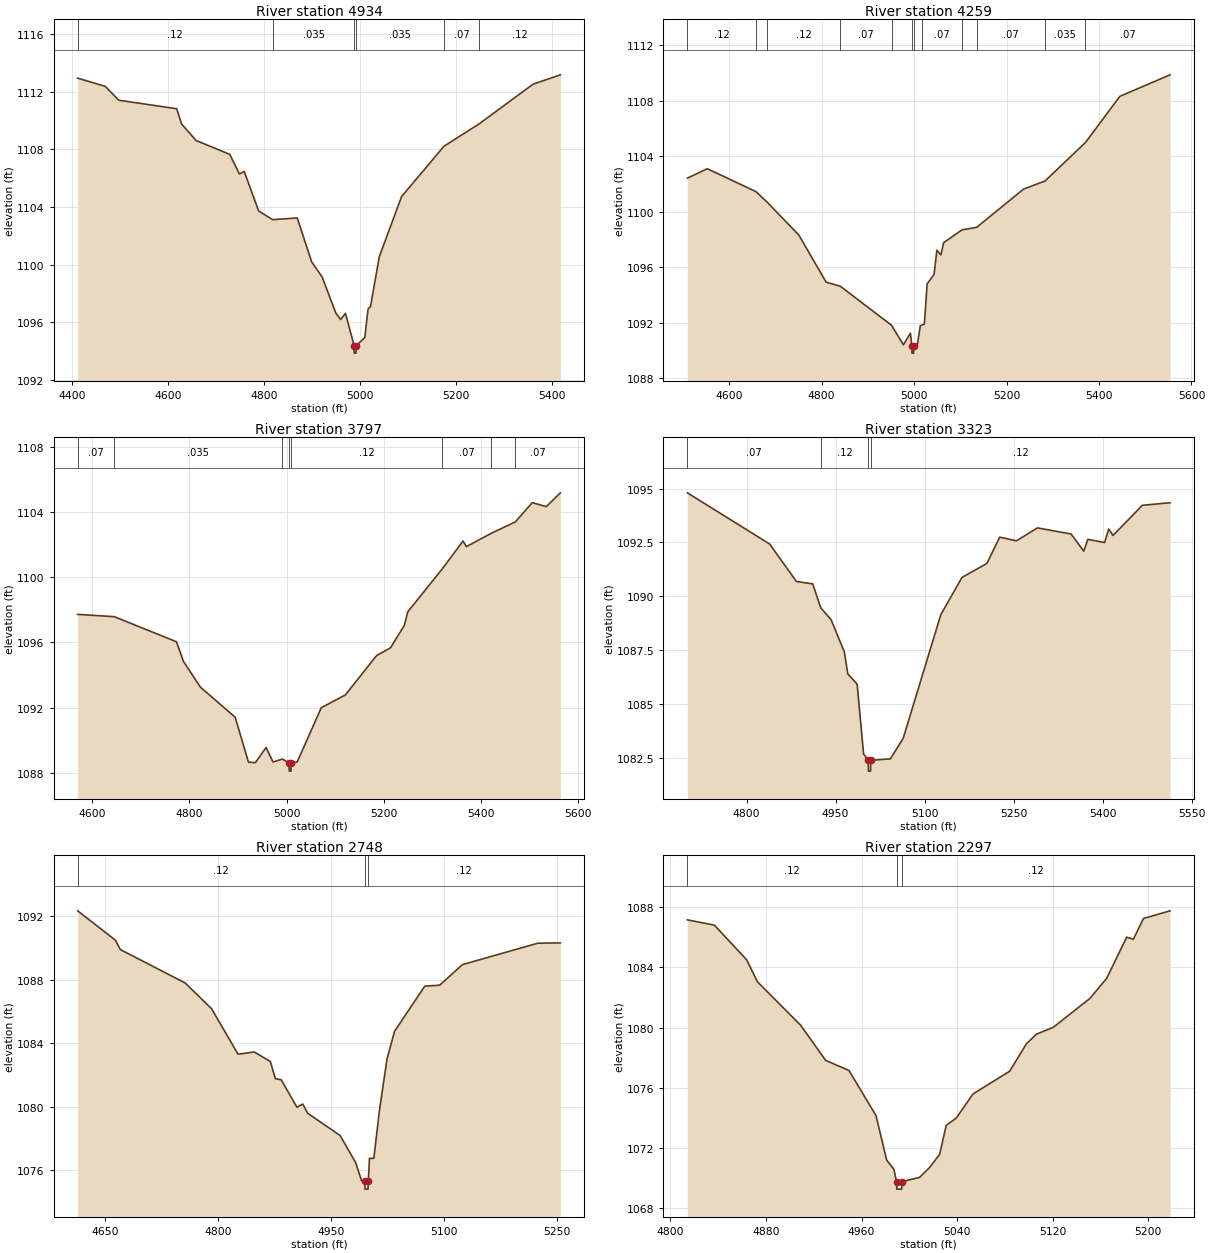
Type RM Length L Ch R = 1,4934,675,675,675
BEGIN DESCRIPTION:
Swine Tributary 2 10.0
END DESCRIPTION:
XS GIS Cut Line= 3
      2143614.81     13858860.39      2143562.73     13858275.00
      2143501.97     13857862.15
#Sta/Elev= 30
  4412.3 1112.93  4469.8 1112.36  4498.0 1111.40  4618.5 1110.81  4628.5 1109.76
  4658.7 1108.61  4728.9 1107.65  4749.0 1106.29  4759.1 1106.46  4789.2 1103.72
  4818.4 1103.12  4869.5 1103.24  4899.6 1100.19  4921.3 1099.15  4949.8 1096.65
  4959.8 1096.20  4969.9 1096.63  4988.0 1094.37  4988.2 1093.87  4991.7 1093.87
  4992.0 1094.37  5010.1 1094.95  5017.0 1096.93  5022.0 1097.10  5040.4 1100.56
  5086.7 1104.72  5175.0 1108.21  5248.1 1109.76  5360.5 1112.51  5417.3 1113.16
#Mann=6,-1,0
  4412.3    0.12       0  4818.4   0.035       0  4988.0   0.035       0
  4992.0   0.035       0  5175.0    0.07       0  5248.1    0.12       0
Bank Sta=4988,4992
Exp/Cntr=0.3,0.1

Type RM Length L Ch R = 1,4259,462,462,462
BEGIN DESCRIPTION:
Swine Tributary 2 9.0
END DESCRIPTION:
XS GIS Cut Line= 3
      2144370.02     13858699.80      2144125.00     13858275.00
      2143671.27     13857957.64
#Sta/Elev= 30
  4509.6 1102.43  4552.6 1103.11  4657.8 1101.46  4682.4 1100.69  4750.8 1098.32
  4809.7 1094.93  4840.6 1094.63  4951.2 1091.82  4976.9 1090.41  4992.1 1091.25
  4995.1 1090.31  4995.4 1089.81  4998.9 1089.81  4999.1 1090.31  5007.4 1090.49
  5013.5 1091.79  5017.5 1091.84  5022.2 1091.90  5028.3 1094.81  5043.2 1095.48
  5049.3 1097.23  5058.0 1096.90  5064.1 1097.78  5103.6 1098.70  5135.3 1098.88
  5236.8 1101.64  5283.1 1102.22  5370.7 1105.00  5445.2 1108.33  5553.7 1109.88
#Mann=12,-1,0
  4509.6    0.12       0  4657.8   0.035       0  4682.4    0.12       0
  4840.6    0.07       0  4951.2    0.12       0  4995.1    0.05       0
  4999.1    0.12       0  5017.5    0.07       0  5103.6   0.035       0
  5135.3    0.07       0  5283.1   0.035       0  5370.7    0.07       0
Bank Sta=4995.1,4999.1
Exp/Cntr=0.3,0.1

Type RM Length L Ch R = 1,3797,474,474,474
BEGIN DESCRIPTION:
Swine Tributary 2 8.0
END DESCRIPTION:
XS GIS Cut Line= 3
      2144851.78     13858504.49      2144525.00     13858225.00
      2144083.53     13857875.13
#Sta/Elev= 30
  4570.0 1097.72  4645.3 1097.58  4773.3 1096.04  4787.6 1094.84  4822.7 1093.25
  4894.1 1091.41  4921.5 1088.65  4935.8 1088.62  4957.7 1089.55  4972.0 1088.66
  4991.4 1088.84  5005.2 1088.60  5005.5 1088.10  5009.0 1088.10  5009.2 1088.60
  5021.6 1088.65  5071.3 1091.99  5121.0 1092.78  5185.1 1095.19  5213.9 1095.67
  5242.4 1097.06  5249.2 1097.87  5320.5 1100.52  5363.0 1102.22  5370.0 1101.88
  5421.3 1102.70  5470.9 1103.40  5505.6 1104.58  5534.4 1104.33  5563.3 1105.18
#Mann=8,-1,0
  4570.0    0.07       0  4645.3   0.035       0  4991.4    0.12       0
  5005.2    0.05       0  5009.2    0.12       0  5320.5    0.07       0
  5421.3    0.12       0  5470.9    0.07       0
Bank Sta=5005.2,5009.2
Exp/Cntr=0.3,0.1

Type RM Length L Ch R = 1,3323,575,575,575
BEGIN DESCRIPTION:
Swine Tributary 2 7.0
END DESCRIPTION:
XS GIS Cut Line= 3
      2144973.31     13858135.55      2144825.00     13857875.00
      2144475.35     13857498.80
#Sta/Elev= 30
  4700.2 1094.80  4838.9 1092.42  4884.0 1090.68  4911.4 1090.57  4924.9 1089.46
  4942.5 1088.90  4964.7 1087.41  4970.5 1086.39  4986.3 1085.91  4997.1 1082.67
  5005.1 1082.37  5005.3 1081.87  5008.8 1081.87  5009.1 1082.37  5042.3 1082.44
  5063.8 1083.39  5127.3 1089.14  5163.0 1090.87  5205.0 1091.52  5226.5 1092.74
  5254.8 1092.57  5290.0 1093.17  5346.7 1092.89  5368.2 1092.09  5375.0 1092.64
  5403.3 1092.49  5410.2 1093.12  5417.5 1092.82  5466.9 1094.22  5513.6 1094.34
#Mann=4,-1,0
  4700.2    0.07       0  4924.9    0.12       0  5005.1    0.05       0
  5009.1    0.12       0
Bank Sta=5005.1,5009.1
Exp/Cntr=0.3,0.1

Type RM Length L Ch R = 1,2748,451,451,451
BEGIN DESCRIPTION:
Swine Tributary 2 6.0
END DESCRIPTION:
XS GIS Cut Line= 3
      2145075.03     13858074.97      2145325.00     13857775.00
      2145325.00     13857524.97
#Sta/Elev= 30
  4614.1 1092.33  4664.2 1090.48  4670.7 1089.89  4756.6 1087.79  4791.7 1086.17
  4826.9 1083.30  4848.4 1083.44  4869.8 1082.84  4876.4 1081.76  4884.2 1081.69
  4905.0 1079.96  4912.8 1080.16  4919.3 1079.58  4962.3 1078.18  4983.1 1076.46
  4990.9 1075.32  4995.1 1075.30  4995.4 1074.80  4999.4 1074.80  4999.8 1075.30
  5001.3 1076.74  5007.1 1076.74  5014.6 1079.78  5024.6 1083.00  5034.6 1084.74
  5074.6 1087.58  5094.6 1087.65  5124.6 1088.94  5224.6 1090.29  5254.6 1090.31
#Mann=3,-1,0
  4614.1    0.12       0  4995.1    0.05       0  4999.8    0.12       0
Bank Sta=4995.1,4999.8
Exp/Cntr=0.3,0.1

Type RM Length L Ch R = 1,2297,479,479,479
BEGIN DESCRIPTION:
Swine Tributary 2 5.0
END DESCRIPTION:
XS GIS Cut Line= 3
      2145324.98     13858275.02      2145475.00     13858175.00
      2145574.99     13857975.01
#Sta/Elev= 30
  4814.3 1087.16  4836.9 1086.81  4863.9 1084.51  4872.9 1083.05  4909.0 1080.17
  4930.0 1077.83  4949.5 1077.16  4972.1 1074.17  4981.1 1071.20  4987.1 1070.60
  4989.3 1069.78  4989.6 1069.28  4993.6 1069.28  4994.0 1069.78  5008.6 1070.06
  5017.0 1070.72  5025.4 1071.59  5030.9 1073.52  5039.3 1074.00  5053.3 1075.60
  5084.0 1077.11  5098.0 1078.93  5106.4 1079.57  5120.4 1080.02  5151.1 1081.94
  5165.1 1083.27  5181.9 1086.01  5187.5 1085.87  5195.9 1087.25  5218.2 1087.76
#Mann=3,-1,0
  4814.3    0.12       0  4989.3    0.05       0  4994.0    0.12       0
Bank Sta=4989.3,4994
Exp/Cntr=0.3,0.1

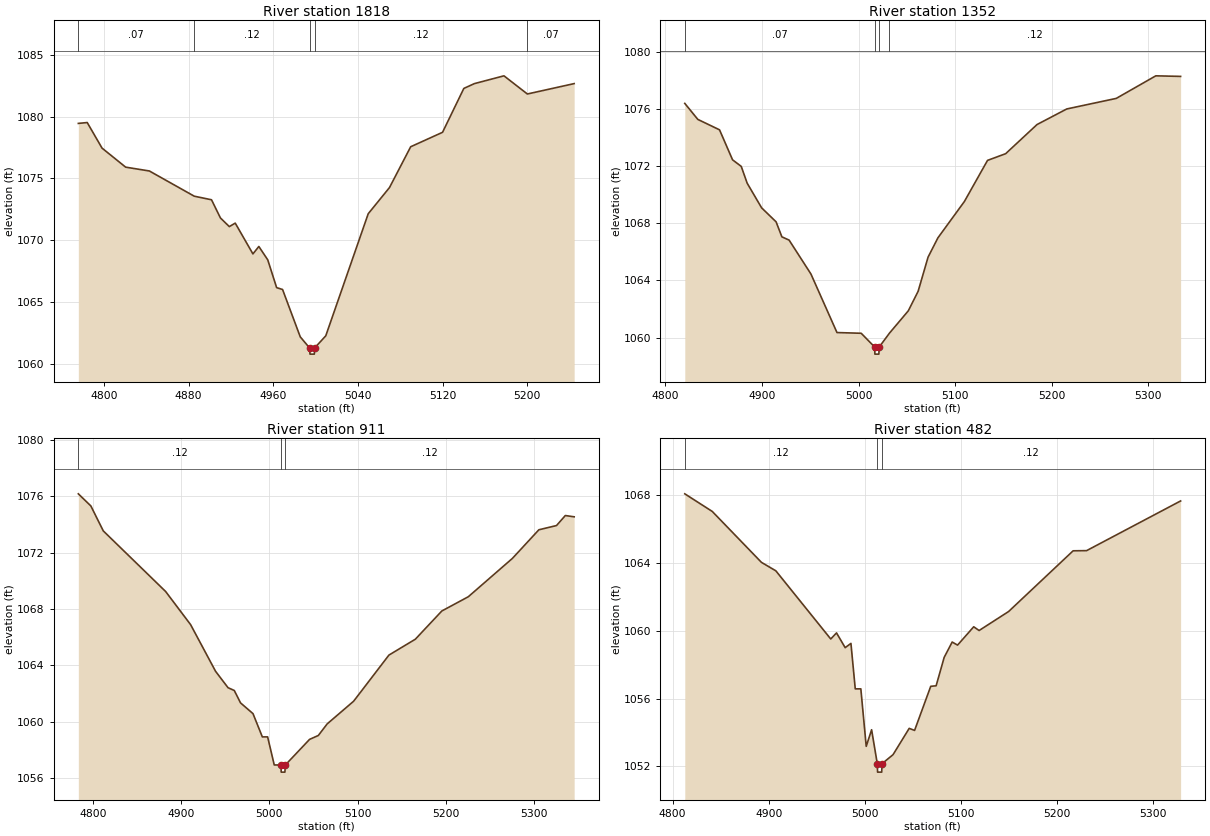
Type RM Length L Ch R = 1,1818,466,466,466
BEGIN DESCRIPTION:
Swine Tributary 2 4.0
END DESCRIPTION:
XS GIS Cut Line= 3
      2145774.99     13858475.02      2145875.00     13858275.00
      2145895.26     13858031.16
#Sta/Elev= 30
  4775.9 1079.45  4784.3 1079.52  4798.3 1077.45  4820.6 1075.91  4843.0 1075.60
  4885.4 1073.56  4901.7 1073.27  4910.1 1071.80  4918.5 1071.10  4924.1 1071.38
  4940.8 1068.89  4946.4 1069.49  4954.8 1068.41  4963.2 1066.16  4968.8 1066.01
  4985.5 1062.18  4994.3 1061.28  4994.7 1060.78  4998.8 1060.78  4999.1 1061.28
  5009.6 1062.26  5049.7 1072.14  5069.8 1074.26  5089.8 1077.56  5119.9 1078.73
  5140.0 1082.28  5150.0 1082.67  5177.9 1083.30  5200.0 1081.83  5244.2 1082.67
#Mann=5,-1,0
  4775.9    0.07       0  4885.4    0.12       0  4994.3    0.05       0
  4999.1    0.12       0  5200.0    0.07       0
Bank Sta=4994.3,4999.1
Exp/Cntr=0.3,0.1

Type RM Length L Ch R = 1,1352,441,441,441
BEGIN DESCRIPTION:
Swine Tributary 2 3.0
END DESCRIPTION:
XS GIS Cut Line= 3
      2146025.03     13858674.98      2146175.00     13858575.00
      2146250.00     13858249.98
#Sta/Elev= 30
  4820.0 1076.39  4833.5 1075.27  4856.0 1074.54  4869.5 1072.44  4878.5 1071.98
  4884.6 1070.81  4899.6 1069.08  4914.6 1068.10  4920.6 1067.05  4928.1 1066.82
  4950.7 1064.45  4977.7 1060.35  5002.8 1060.30  5016.7 1059.34  5017.0 1058.84
  5021.1 1058.84  5021.5 1059.34  5032.1 1060.31  5051.6 1061.87  5061.8 1063.24
  5072.1 1065.63  5082.3 1066.98  5109.7 1069.52  5133.7 1072.40  5152.5 1072.87
  5185.0 1074.91  5215.8 1076.00  5267.1 1076.74  5308.1 1078.32  5333.8 1078.28
#Mann=4,-1,0
  4820.0    0.07       0  5016.7    0.05       0  5021.5    0.07       0
  5032.1    0.12       0
Bank Sta=5016.7,5021.5
Exp/Cntr=0.3,0.1

Type RM Length L Ch R = 1,911,429,429,429
BEGIN DESCRIPTION:
Swine Tributary 2 2.0
END DESCRIPTION:
XS GIS Cut Line= 3
      2146374.99     13858975.01      2146525.00     13858825.00
      2146525.00     13858475.05
#Sta/Elev= 30
  4783.5 1076.17  4797.7 1075.31  4811.8 1073.54  4882.5 1069.24  4910.8 1066.89
  4939.1 1063.58  4953.2 1062.42  4960.3 1062.22  4967.4 1061.34  4981.5 1060.58
  4992.1 1058.93  4998.1 1058.93  5005.6 1056.94  5013.2 1056.93  5013.5 1056.43
  5017.7 1056.43  5018.1 1056.93  5045.6 1058.75  5055.6 1059.03  5065.6 1059.85
  5095.6 1061.46  5135.6 1064.73  5165.6 1065.86  5195.6 1067.86  5225.6 1068.87
  5275.6 1071.59  5305.6 1073.62  5325.6 1073.92  5335.6 1074.63  5345.6 1074.54
#Mann=3,-1,0
  4783.5    0.12       0  5013.2    0.05       0  5018.1    0.12       0
Bank Sta=5013.2,5018.1
Exp/Cntr=0.3,0.1

Type RM Length L Ch R = 1,482,0,0,0
BEGIN DESCRIPTION:
Swine Tributary 2 1.0
END DESCRIPTION:
XS GIS Cut Line= 3
      2146824.98     13859075.03      2146925.00     13858925.00
      2146775.01     13858625.02
#Sta/Elev= 30
  4812.7 1068.07  4841.3 1067.03  4892.4 1064.03  4907.4 1063.53  4964.5 1059.51
  4970.5 1059.87  4979.5 1059.00  4985.5 1059.25  4990.0 1056.57  4995.8 1056.57
  5001.4 1053.18  5007.0 1054.16  5012.9 1052.16  5013.2 1051.66  5017.5 1051.66
  5017.9 1052.16  5029.3 1052.69  5046.1 1054.24  5051.7 1054.12  5068.5 1056.72
  5074.1 1056.75  5082.5 1058.43  5090.8 1059.33  5096.4 1059.15  5113.2 1060.23
  5118.8 1060.01  5149.5 1061.13  5216.6 1064.71  5230.6 1064.72  5328.4 1067.65
#Mann=3,-1,0
  4812.7    0.12       0  5012.9    0.05       0  5017.9    0.12       0
Bank Sta=5012.9,5017.9
Exp/Cntr=0.3,0.1

Chan Stop Cuts=-1