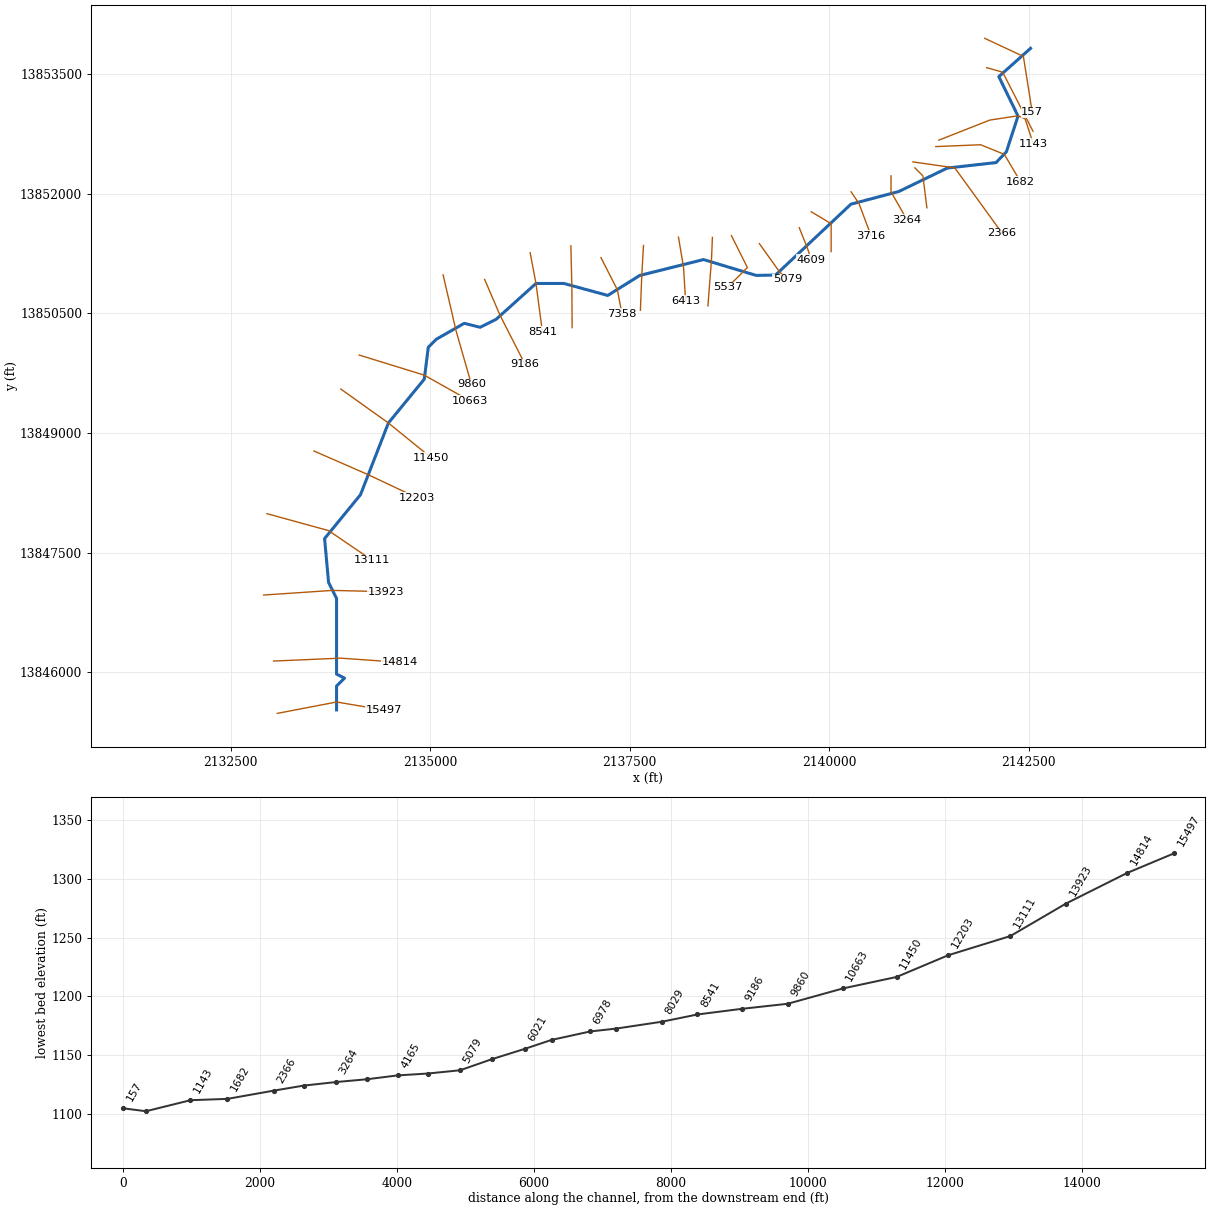
--- Swine Tributary 4.prj (project) ---

Proj Title=Swine Tributary 4 Base Level Engineering
Current Plan=p01
Default Exp/Contr=0.3,0.1
English Units
Geom File=g01
Flow File=f01
Plan File=p01
BEGIN DESCRIPTION:
Swine Tributary 4
END DESCRIPTION:

--- Swine Tributary 4.p01 (plan) ---

Plan Title=Multiple Run
Short Identifier=Multiple
Geom File=g01
Flow File=f01
Subcritical Flow
K Sum by GR= 0
Std Step Tol= 0.01
Critical Tol= 0.01
Num of Std Step Trials= 20
Max Error Tol= 0.3
Flow Tol Ratio= 0.001
Split Flow NTrial= 30
Split Flow Tol= 0.02
Split Flow Ratio= 0.02
Log Output Level= 0
Friction Slope Method= 1
Unsteady Friction Slope Method= 2
Unsteady Bridges Friction Slope Method= 1
Parabolic Critical Depth
Global Vel Dist=  1 , 1 , 1
Global Log Level= 0
CheckData=True
Encroach Param= -1, 0, 0, 0
BEGIN DESCRIPTION:
Multiple Run
END DESCRIPTION:

--- Swine Tributary 4.f01 (steady flow) ---

Flow Title=Multiple
Number of Profiles=7
Profile Names=10-year,25-year,50-year,1pct_min,100-year,1pct_plu,500-year
River Rch & RM= Swine Tributary ,Reach-1,15497
     216     328     424     268     534    1066     834
River Rch & RM= Swine Tributary ,Reach-1,13923
     693    1145    1566    1041    2076    4143    3604
River Rch & RM= Swine Tributary ,Reach-1,9860
    1465    2529    3559    2425    4839    9656    8855
River Rch & RM= Swine Tributary ,Reach-1,5537
    1991    3483    4944    3393    6770   13508   12571
River Rch & RM= Swine Tributary ,Reach-1,493
    2128    3747    5342    3681    7345   14654   13754
Boundary for River Rch & Prof#=Swine Tributary ,Reach-1,1
Up Type=0
Dn Type=3
Dn Slope=0.005
Boundary for River Rch & Prof#=Swine Tributary ,Reach-1,2
Up Type=0
Dn Type=3
Dn Slope=0.005
Boundary for River Rch & Prof#=Swine Tributary ,Reach-1,3
Up Type=0
Dn Type=3
Dn Slope=0.005
Boundary for River Rch & Prof#=Swine Tributary ,Reach-1,4
Up Type=0
Dn Type=3
Dn Slope=0.005
Boundary for River Rch & Prof#=Swine Tributary ,Reach-1,5
Up Type=0
Dn Type=3
Dn Slope=0.005
Boundary for River Rch & Prof#=Swine Tributary ,Reach-1,6
Up Type=0
Dn Type=3
Dn Slope=0.005
Boundary for River Rch & Prof#=Swine Tributary ,Reach-1,7
Up Type=0
Dn Type=3
Dn Slope=0.005

--- Swine Tributary 4.g01 (geometry) ---

Geom Title=Existing Conditions

River Reach=Swine Tributary ,Reach-1
Reach XY= 30
      2133825.00     13845525.00      2133825.00     13845825.00
      2133925.00     13845925.00      2133825.00     13845975.00
      2133825.00     13846925.00      2133725.00     13847125.00
      2133675.00     13847675.00      2134125.00     13848225.00
      2134475.00     13849125.00      2134925.00     13849675.00
      2134975.00     13850075.00      2135075.00     13850175.00
      2135425.00     13850375.00      2135625.00     13850325.00
      2135825.00     13850425.00      2136325.00     13850875.00
      2136675.00     13850875.00      2137225.00     13850725.00
      2137625.00     13850975.00      2138425.00     13851175.00
      2139084.59     13850976.21      2139327.45     13850980.47
      2140272.57     13851869.48      2140873.42     13852028.83
      2141480.94     13852322.74      2142091.77     13852391.43
      2142221.39     13852526.50      2142367.50     13852975.00
      2142126.88     13853469.85      2142525.00     13853825.00

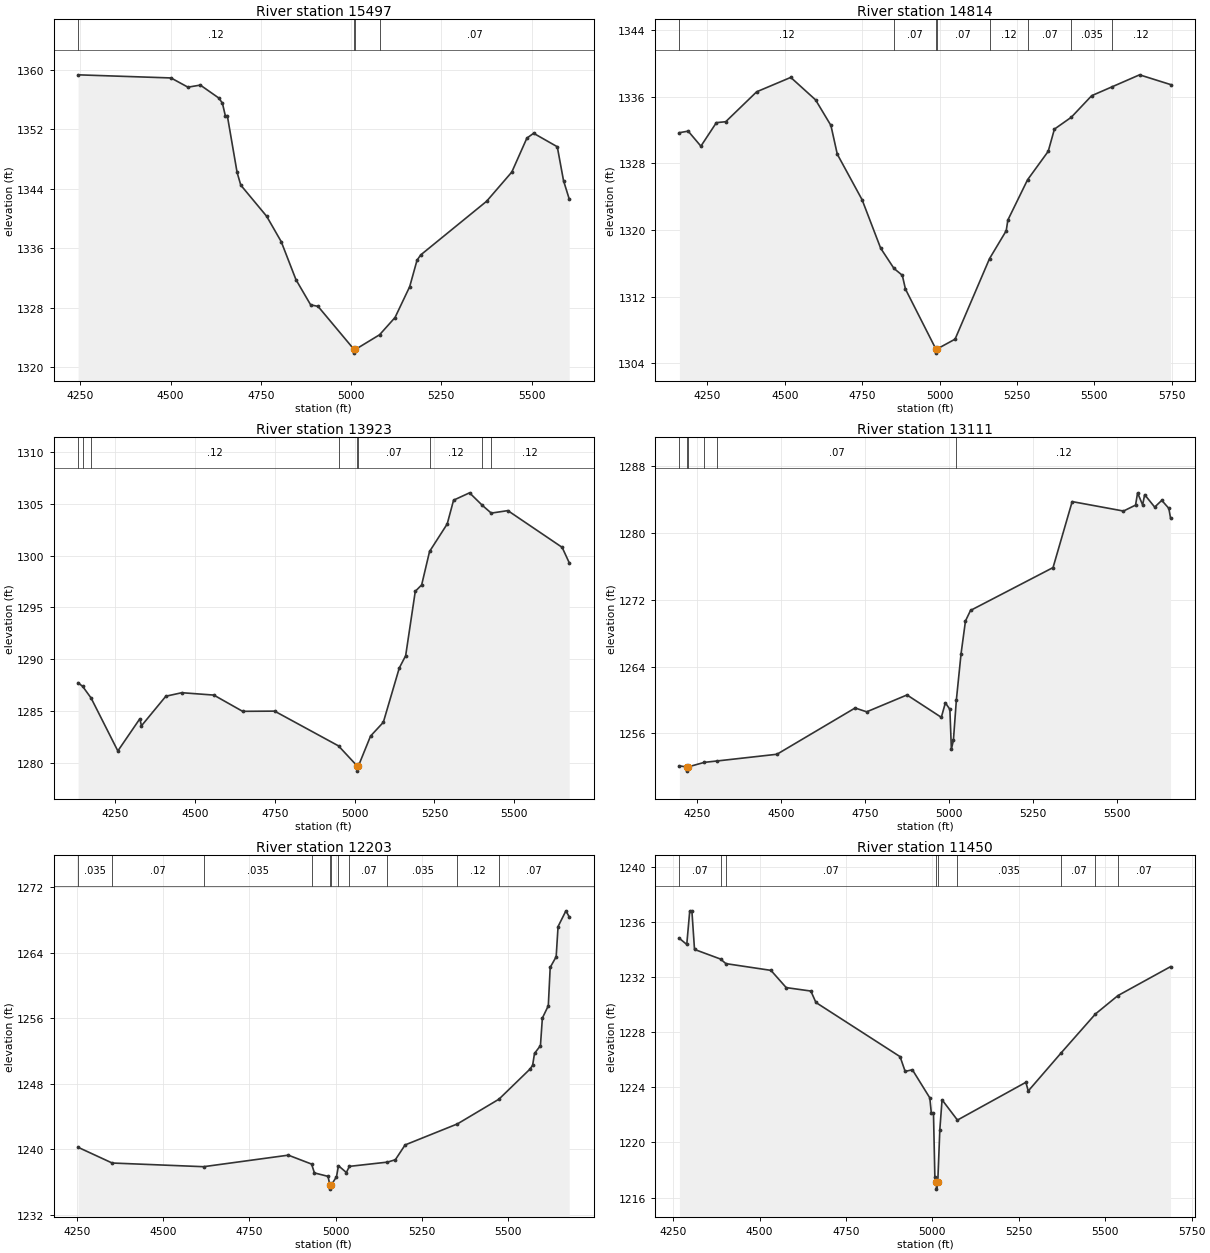
Type RM Length L Ch R = 1,15497,683,683,683
BEGIN DESCRIPTION:
Swine Tributary 4 26.0
END DESCRIPTION:
XS GIS Cut Line= 3
      2133082.58     13845482.35      2133825.00     13845625.00
      2134420.62     13845524.11
#Sta/Elev= 30
  4244.0 1359.29  4501.3 1358.87  4548.2 1357.63  4582.5 1357.91  4633.4 1356.18
  4643.6 1355.49  4652.1 1353.71  4657.2 1353.81  4684.3 1346.17  4694.5 1344.46
  4766.2 1340.27  4806.5 1336.86  4847.3 1331.75  4888.0 1328.36  4908.4 1328.16
  5008.1 1322.37  5008.4 1321.87  5012.1 1322.37  5078.9 1324.34  5121.7 1326.66
  5162.3 1330.81  5182.6 1334.36  5192.7 1335.07  5375.3 1342.29  5445.1 1346.22
  5486.8 1350.78  5505.5 1351.43  5571.0 1349.62  5588.3 1345.06  5604.1 1342.59
#Mann=4,-1,0
  4244.0    0.12       0  5008.1    0.05       0  5012.1    0.12       0
  5078.9    0.07       0
Bank Sta=5008.1,5012.1
Exp/Cntr=0.3,0.1

Type RM Length L Ch R = 1,14814,891,891,891
BEGIN DESCRIPTION:
Swine Tributary 4 25.0
END DESCRIPTION:
XS GIS Cut Line= 3
      2133035.69     13846138.61      2133875.00     13846175.00
      2134619.08     13846122.98
#Sta/Elev= 30
  4159.9 1331.70  4188.2 1331.89  4229.3 1330.08  4279.3 1332.91  4309.4 1333.02
  4409.4 1336.62  4519.5 1338.35  4599.6 1335.65  4649.2 1332.57  4669.7 1329.12
  4749.8 1323.64  4809.8 1317.81  4852.7 1315.38  4879.7 1314.55  4889.9 1312.89
  4988.0 1305.69  4988.2 1305.19  4992.0 1305.69  5050.1 1306.87  5161.3 1316.55
  5215.3 1319.91  5220.5 1321.19  5284.2 1326.04  5350.9 1329.46  5370.9 1332.13
  5425.5 1333.56  5491.2 1336.15  5557.2 1337.22  5645.9 1338.66  5745.9 1337.49
#Mann=8,-1,0
  4159.9    0.12       0  4852.7    0.07       0  4988.0    0.05       0
  4992.0    0.07       0  5161.3    0.12       0  5284.2    0.07       0
  5425.5   0.035       0  5557.2    0.12       0
Bank Sta=4988,4992
Exp/Cntr=0.3,0.1

Type RM Length L Ch R = 1,13923,812,812,812
BEGIN DESCRIPTION:
Swine Tributary 4 24.0
END DESCRIPTION:
XS GIS Cut Line= 3
      2132910.76     13846966.73      2133775.00     13847025.00
      2134447.20     13847008.40
#Sta/Elev= 30
  4133.8 1287.72  4148.1 1287.37  4174.4 1286.25  4258.3 1281.13  4327.2 1284.24
  4332.3 1283.56  4408.7 1286.42  4458.8 1286.76  4559.0 1286.53  4649.2 1284.96
  4749.4 1284.98  4949.6 1281.62  5008.0 1279.68  5008.3 1279.18  5012.0 1279.68
  5050.0 1282.57  5090.0 1283.90  5140.0 1289.15  5160.0 1290.34  5190.1 1296.56
  5210.1 1297.18  5234.8 1300.41  5290.1 1303.07  5310.1 1305.37  5360.1 1306.08
  5400.5 1304.86  5428.1 1304.12  5480.1 1304.36  5650.2 1300.81  5672.4 1299.32
#Mann=9,-1,0
  4133.8    0.12       0  4148.1    0.07       0  4174.4    0.12       0
  4949.6    0.07       0  5008.0    0.05       0  5012.0    0.07       0
  5234.8    0.12       0  5400.5    0.07       0  5428.1    0.12       0
Bank Sta=5008,5012
Exp/Cntr=0.3,0.1

Type RM Length L Ch R = 1,13111,908,908,908
BEGIN DESCRIPTION:
Swine Tributary 4 23.0
END DESCRIPTION:
XS GIS Cut Line= 3
      2132952.41     13847987.56      2133725.00     13847775.00
      2134270.07     13847404.26
#Sta/Elev= 30
  4198.7 1252.11  4220.1 1251.98  4220.3 1251.48  4224.1 1251.98  4272.9 1252.53
  4311.6 1252.70  4488.8 1253.50  4721.2 1259.04  4755.6 1258.58  4875.5 1260.60
  4977.6 1257.92  4989.6 1259.66  5003.0 1258.88  5007.5 1254.11  5013.5 1255.16
  5022.3 1260.00  5036.3 1265.55  5049.4 1269.46  5064.4 1270.72  5309.8 1275.85
  5366.7 1283.75  5519.3 1282.62  5555.2 1283.33  5561.2 1284.80  5576.2 1283.35
  5582.2 1284.58  5612.1 1283.09  5633.1 1283.90  5654.1 1282.94  5659.2 1281.79
#Mann=6,-1,0
  4198.7    0.07       0  4220.1    0.05       0  4224.1    0.07       0
  4272.9   0.035       0  4311.6    0.07       0  5022.3    0.12       0
Bank Sta=4220.1,4224.1
Exp/Cntr=0.3,0.1

Type RM Length L Ch R = 1,12203,753,753,753
BEGIN DESCRIPTION:
Swine Tributary 4 22.0
END DESCRIPTION:
XS GIS Cut Line= 3
      2133540.90     13848774.04      2134225.00     13848475.00
      2134837.85     13848185.47
#Sta/Elev= 30
  4253.4 1240.23  4352.2 1238.31  4617.2 1237.86  4863.1 1239.27  4930.6 1238.18
  4938.8 1237.10  4978.2 1236.68  4983.6 1235.62  4983.8 1235.12  4987.6 1235.62
  5002.8 1236.63  5008.5 1237.98  5031.4 1237.15  5040.2 1237.90  5150.7 1238.42
  5173.5 1238.71  5201.8 1240.52  5353.6 1243.09  5474.0 1246.11  5564.1 1249.79
  5571.6 1250.25  5577.1 1251.70  5594.3 1252.65  5599.9 1256.02  5617.1 1257.52
  5622.6 1262.21  5639.9 1263.51  5645.4 1267.20  5668.2 1269.12  5677.8 1268.38
#Mann=11,-1,0
  4253.4   0.035       0  4352.2    0.07       0  4617.2   0.035       0
  4930.6    0.07       0  4983.6    0.05       0  4987.6    0.07       0
  5008.5   0.035       0  5040.2    0.07       0  5150.7   0.035       0
  5353.6    0.12       0  5474.0    0.07       0
Bank Sta=4983.6,4987.6
Exp/Cntr=0.3,0.1

Type RM Length L Ch R = 1,11450,787,787,787
BEGIN DESCRIPTION:
Swine Tributary 4 21.0
END DESCRIPTION:
XS GIS Cut Line= 3
      2133879.45     13849550.09      2134475.00     13849125.00
      2135009.73     13848690.66
#Sta/Elev= 30
  4268.3 1234.80  4289.6 1234.36  4298.2 1236.79  4304.4 1236.80  4312.0 1234.00
  4387.4 1233.30  4402.7 1232.97  4533.1 1232.48  4577.2 1231.23  4648.5 1230.98
  4663.2 1230.15  4906.6 1226.22  4921.3 1225.15  4942.2 1225.27  4992.6 1223.23
  4996.9 1222.14  5003.2 1222.14  5007.2 1217.50  5011.6 1217.11  5011.9 1216.61
  5015.6 1217.11  5021.6 1220.93  5028.0 1223.09  5072.5 1221.62  5270.5 1224.36
  5277.3 1223.73  5372.7 1226.50  5471.8 1229.32  5536.7 1230.65  5688.9 1232.75
#Mann=9,-1,0
  4268.3    0.07       0  4387.4   0.035       0  4402.7    0.07       0
  5011.6    0.05       0  5015.6    0.07       0  5072.5   0.035       0
  5372.7    0.07       0  5471.8   0.035       0  5536.7    0.07       0
Bank Sta=5011.6,5015.6
Exp/Cntr=0.3,0.1

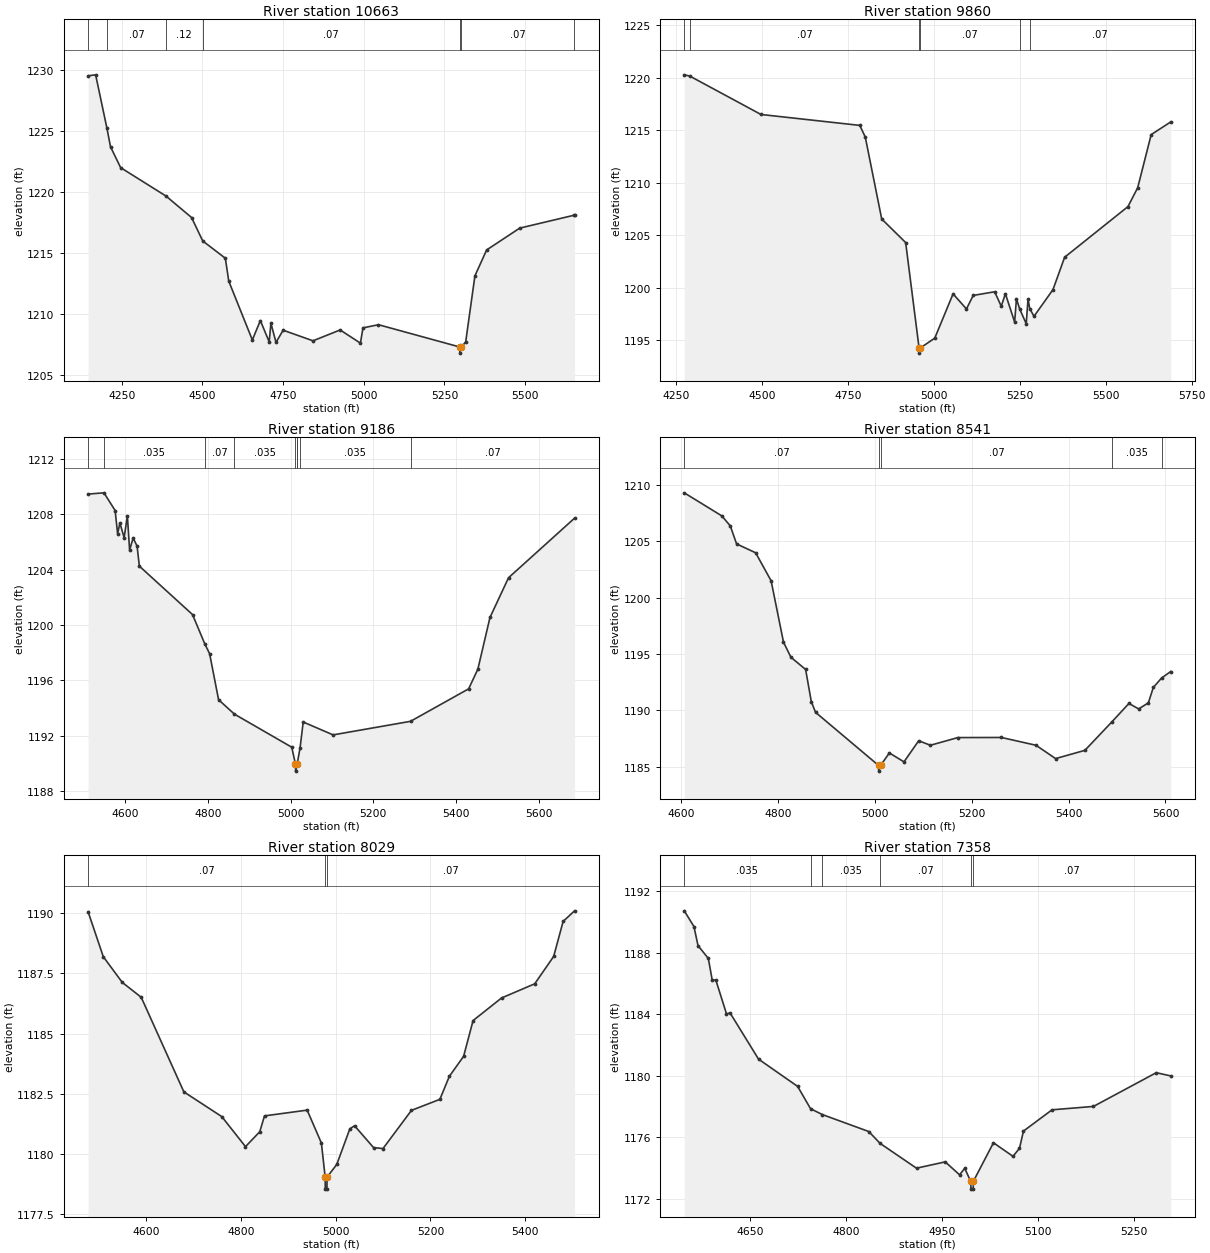
Type RM Length L Ch R = 1,10663,803,803,803
BEGIN DESCRIPTION:
Swine Tributary 4 20.0
END DESCRIPTION:
XS GIS Cut Line= 3
      2134108.65     13849977.15      2134925.00     13849725.00
      2135494.03     13849404.25
#Sta/Elev= 30
  4145.6 1229.52  4168.9 1229.60  4204.0 1225.21  4215.0 1223.70  4246.4 1221.99
  4387.0 1219.66  4466.2 1217.90  4500.8 1215.98  4570.9 1214.56  4581.5 1212.68
  4654.6 1207.86  4679.4 1209.45  4706.8 1207.70  4712.1 1209.23  4727.9 1207.66
  4750.0 1208.66  4842.6 1207.79  4926.7 1208.68  4989.5 1207.60  4997.4 1208.85
  5045.5 1209.11  5297.7 1207.28  5298.0 1206.78  5301.7 1207.28  5315.7 1207.69
  5344.4 1213.12  5380.7 1215.24  5483.2 1217.03  5652.1 1218.09  5653.2 1218.09
#Mann=7,-1,0
  4145.6   0.035       0  4204.0    0.07       0  4387.0    0.12       0
  4500.8    0.07       0  5297.7    0.05       0  5301.7    0.07       0
  5652.1    0.12       0
Bank Sta=5297.7,5301.7
Exp/Cntr=0.3,0.1

Type RM Length L Ch R = 1,9860,674,674,674
BEGIN DESCRIPTION:
Swine Tributary 4 19.0
END DESCRIPTION:
XS GIS Cut Line= 3
      2135160.73     13850982.38      2135325.00     13850275.00
      2135514.90     13849612.58
#Sta/Elev= 30
  4273.8 1220.29  4289.9 1220.17  4497.0 1216.51  4784.4 1215.47  4800.4 1214.36
  4848.2 1206.55  4917.9 1204.30  4956.9 1194.26  4957.2 1193.76  4960.9 1194.26
  5002.6 1195.19  5055.8 1199.41  5094.8 1197.97  5114.4 1199.26  5176.8 1199.61
  5196.0 1198.23  5208.1 1199.42  5235.0 1196.72  5240.2 1198.94  5249.6 1197.97
  5268.7 1196.56  5273.9 1198.92  5278.9 1198.01  5291.3 1197.27  5346.6 1199.82
  5380.4 1202.90  5564.7 1207.73  5593.0 1209.53  5632.2 1214.59  5689.1 1215.80
#Mann=6,-1,0
  4273.8   0.035       0  4289.9    0.07       0  4956.9    0.05       0
  4960.9    0.07       0  5249.6    0.12       0  5278.9    0.07       0
Bank Sta=4956.9,4960.9
Exp/Cntr=0.3,0.1

Type RM Length L Ch R = 1,9186,645,645,645
BEGIN DESCRIPTION:
Swine Tributary 4 18.0
END DESCRIPTION:
XS GIS Cut Line= 3
      2135681.56     13850925.09      2135875.00     13850475.00
      2136186.76     13849862.59
#Sta/Elev= 30
  4510.1 1209.46  4548.5 1209.55  4575.5 1208.27  4581.5 1206.59  4587.0 1207.37
  4597.3 1206.31  4605.1 1207.88  4610.5 1205.41  4619.0 1206.28  4628.6 1205.70
  4634.1 1204.25  4762.7 1200.75  4792.3 1198.64  4804.1 1197.92  4825.8 1194.59
  4864.2 1193.55  5002.8 1191.16  5011.9 1189.93  5012.2 1189.43  5015.9 1189.93
  5016.1 1189.96  5023.0 1191.12  5030.6 1192.98  5102.9 1192.05  5290.2 1193.03
  5430.9 1195.38  5453.2 1196.80  5482.5 1200.54  5527.4 1203.41  5687.2 1207.72
#Mann=9,-1,0
  4510.1    0.07       0  4548.5   0.035       0  4792.3    0.07       0
  4864.2   0.035       0  5011.9   0.035       0  5015.9   0.035       0
  5016.1    0.07       0  5023.0   0.035       0  5290.2    0.07       0
Bank Sta=5011.9,5015.9
Exp/Cntr=0.3,0.1

Type RM Length L Ch R = 1,8541,512,512,512
BEGIN DESCRIPTION:
Swine Tributary 4 17.0
END DESCRIPTION:
XS GIS Cut Line= 3
      2136251.87     13851261.03      2136325.00     13850875.00
      2136405.44     13850269.42
#Sta/Elev= 30
  4607.1 1209.27  4684.5 1207.23  4702.1 1206.34  4715.0 1204.75  4754.4 1203.96
  4786.3 1201.48  4811.8 1196.06  4827.0 1194.72  4857.5 1193.63  4869.2 1190.79
  4877.9 1189.84  5008.1 1185.13  5008.3 1184.63  5012.1 1185.13  5030.3 1186.24
  5060.5 1185.45  5090.8 1187.32  5115.0 1186.92  5171.5 1187.60  5261.5 1187.61
  5332.9 1186.92  5373.3 1185.74  5433.8 1186.47  5489.9 1189.01  5524.6 1190.62
  5544.7 1190.14  5564.7 1190.67  5575.0 1192.04  5591.9 1192.87  5610.9 1193.45
#Mann=5,-1,0
  4607.1    0.07       0  5008.1    0.05       0  5012.1    0.07       0
  5489.9   0.035       0  5591.9    0.07       0
Bank Sta=5008.1,5012.1
Exp/Cntr=0.3,0.1

Type RM Length L Ch R = 1,8029,671,671,671
BEGIN DESCRIPTION:
Swine Tributary 4 16.0
END DESCRIPTION:
XS GIS Cut Line= 3
      2136762.30     13851346.95      2136775.00     13850825.00
      2136777.92     13850320.91
#Sta/Elev= 30
  4477.9 1190.07  4509.9 1188.20  4549.9 1187.13  4589.9 1186.51  4679.9 1182.57
  4759.9 1181.54  4809.9 1180.29  4840.0 1180.91  4850.0 1181.57  4940.0 1181.81
  4970.0 1180.44  4978.0 1179.02  4978.2 1178.52  4981.7 1178.52  4982.0 1179.02
  5002.5 1179.55  5030.0 1181.03  5040.0 1181.16  5080.0 1180.25  5100.0 1180.21
  5160.0 1181.80  5220.0 1182.26  5240.0 1183.22  5270.0 1184.05  5290.0 1185.54
  5350.0 1186.48  5420.0 1187.07  5460.0 1188.21  5480.0 1189.67  5504.1 1190.11
#Mann=3,-1,0
  4477.9    0.07       0  4978.0    0.05       0  4982.0    0.07       0
Bank Sta=4978,4982
Exp/Cntr=0.3,0.1

Type RM Length L Ch R = 1,7358,380,380,380
BEGIN DESCRIPTION:
Swine Tributary 4 15.0
END DESCRIPTION:
XS GIS Cut Line= 3
      2137139.91     13851198.48      2137345.24     13850795.24
      2137402.92     13850492.79
#Sta/Elev= 30
  4547.5 1190.71  4562.6 1189.69  4569.0 1188.45  4585.1 1187.62  4591.2 1186.21
  4596.8 1186.22  4613.5 1184.02  4619.1 1184.08  4663.6 1181.08  4724.7 1179.31
  4744.9 1177.86  4763.4 1177.48  4835.9 1176.38  4853.6 1175.61  4910.5 1174.00
  4955.4 1174.41  4977.8 1173.57  4985.9 1173.99  4995.3 1173.14  4995.6 1172.64
  4999.1 1172.64  4999.3 1173.14  5030.8 1175.65  5061.3 1174.77  5071.5 1175.29
  5077.7 1176.41  5122.4 1177.79  5187.1 1178.01  5285.3 1180.20  5307.9 1179.99
#Mann=6,-1,0
  4547.5   0.035       0  4744.9    0.07       0  4763.4   0.035       0
  4853.6    0.07       0  4995.3    0.05       0  4999.3    0.07       0
Bank Sta=4995.3,4999.3
Exp/Cntr=0.3,0.1

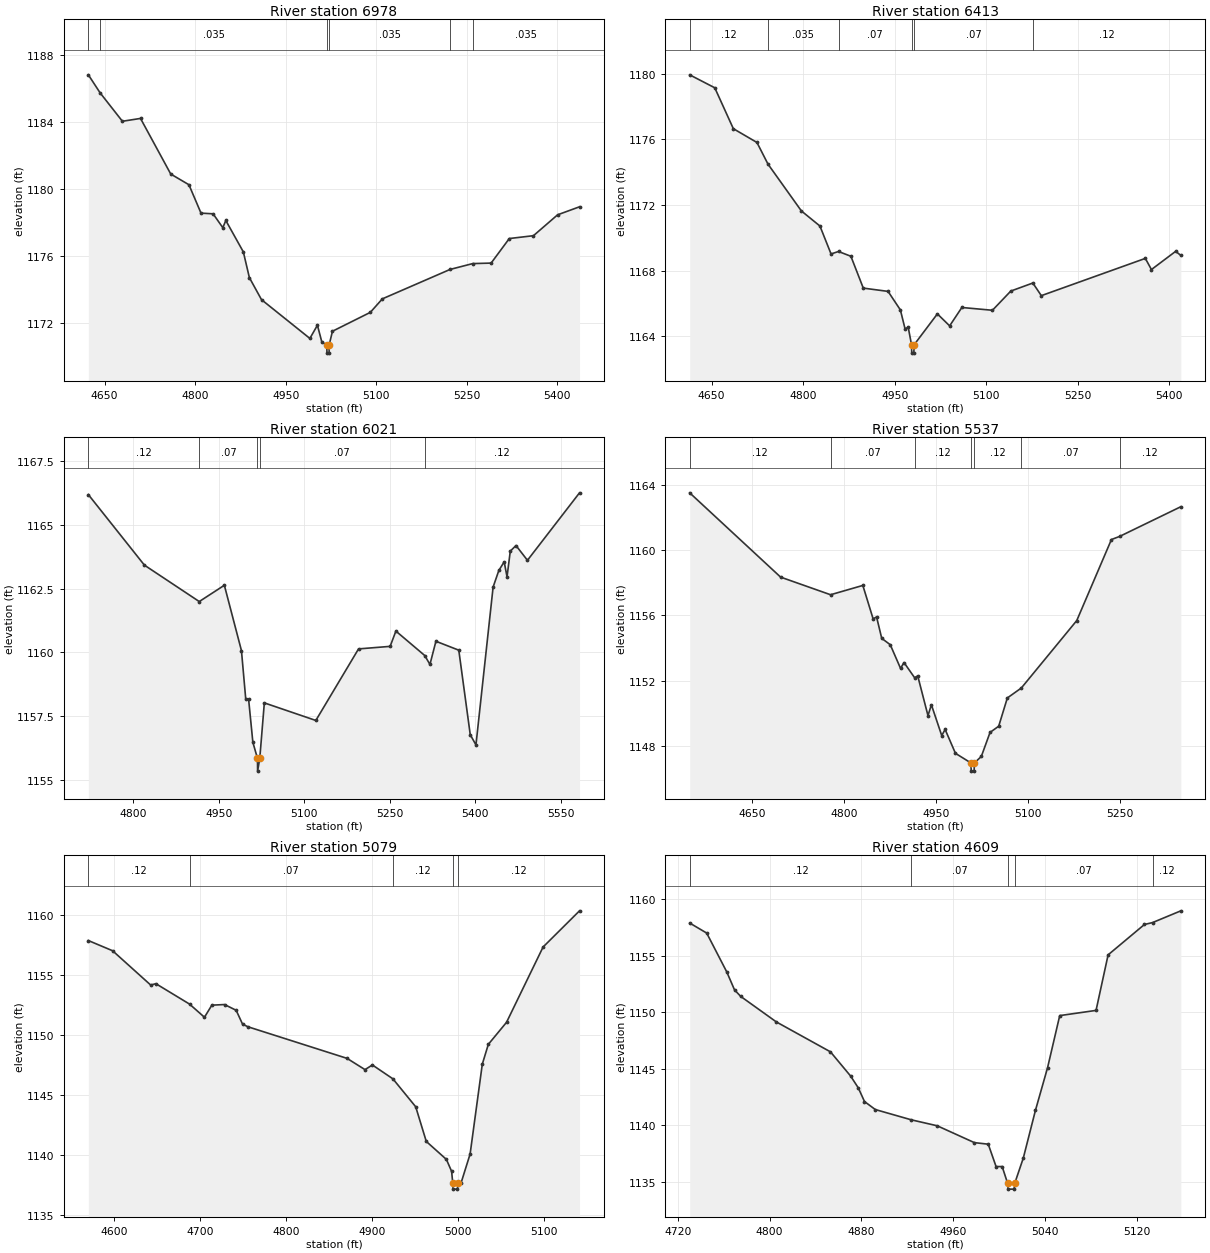
Type RM Length L Ch R = 1,6978,565,565,565
BEGIN DESCRIPTION:
Swine Tributary 4 14.0
END DESCRIPTION:
XS GIS Cut Line= 3
      2137672.89     13851351.27      2137651.18     13850975.00
      2137633.87     13850538.74
#Sta/Elev= 30
  4623.1 1186.84  4642.6 1185.76  4679.5 1184.06  4709.5 1184.23  4759.6 1180.90
  4789.7 1180.26  4809.7 1178.56  4829.7 1178.52  4845.8 1177.69  4850.8 1178.12
  4879.8 1176.24  4889.8 1174.70  4909.9 1173.38  4990.0 1171.06  5002.5 1171.85
  5010.0 1170.82  5018.0 1170.68  5018.3 1170.18  5021.8 1170.18  5022.0 1170.68
  5027.4 1171.49  5090.1 1172.62  5110.1 1173.43  5222.2 1175.19  5259.7 1175.54
  5290.2 1175.57  5320.3 1177.04  5360.3 1177.21  5400.3 1178.46  5436.6 1178.94
#Mann=6,-1,0
  4623.1    0.07       0  4642.6   0.035       0  5018.0   0.035       0
  5022.0   0.035       0  5222.2    0.12       0  5259.7   0.035       0
Bank Sta=5018,5022
Exp/Cntr=0.3,0.1

Type RM Length L Ch R = 1,6413,392,392,392
BEGIN DESCRIPTION:
Swine Tributary 4 13.0
END DESCRIPTION:
XS GIS Cut Line= 3
      2138111.25     13851455.50      2138175.00     13851075.00
      2138200.23     13850656.86
#Sta/Elev= 30
  4614.2 1179.92  4655.3 1179.13  4685.7 1176.64  4724.4 1175.80  4742.5 1174.48
  4797.2 1171.63  4827.6 1170.71  4845.8 1169.01  4858.0 1169.16  4878.3 1168.87
  4898.6 1166.93  4939.2 1166.73  4959.4 1165.60  4967.1 1164.44  4972.2 1164.55
  4977.7 1163.47  4978.0 1162.97  4981.5 1162.97  4981.7 1163.47  5020.0 1165.36
  5040.1 1164.63  5060.1 1165.75  5110.2 1165.58  5140.3 1166.75  5176.4 1167.24
  5190.3 1166.47  5360.7 1168.74  5370.7 1168.06  5410.4 1169.17  5418.9 1168.92
#Mann=6,-1,0
  4614.2    0.12       0  4742.5   0.035       0  4858.0    0.07       0
  4977.7    0.05       0  4981.7    0.07       0  5176.4    0.12       0
Bank Sta=4977.7,4981.7
Exp/Cntr=0.3,0.1

Type RM Length L Ch R = 1,6021,484,484,484
BEGIN DESCRIPTION:
Swine Tributary 4 12.0
END DESCRIPTION:
XS GIS Cut Line= 3
      2138536.60     13851453.26      2138525.00     13851175.00
      2138480.18     13850593.93
#Sta/Elev= 30
  4721.5 1166.19  4819.8 1163.42  4916.0 1161.99  4960.0 1162.63  4990.0 1160.06
  4997.5 1158.16  5002.5 1158.16  5010.0 1156.46  5018.1 1155.83  5018.3 1155.33
  5022.1 1155.83  5030.1 1158.01  5120.4 1157.32  5195.3 1160.13  5250.7 1160.23
  5260.8 1160.83  5311.4 1159.87  5320.5 1159.52  5331.0 1160.43  5371.1 1160.08
  5391.2 1156.76  5401.2 1156.36  5431.3 1162.56  5441.3 1163.21  5450.7 1163.55
  5455.7 1162.96  5461.4 1163.97  5471.4 1164.19  5491.5 1163.61  5582.8 1166.26
#Mann=5,-1,0
  4721.5    0.12       0  4916.0    0.07       0  5018.1    0.05       0
  5022.1    0.07       0  5311.4    0.12       0
Bank Sta=5018.1,5022.1
Exp/Cntr=0.3,0.1

Type RM Length L Ch R = 1,5537,458,458,458
BEGIN DESCRIPTION:
Swine Tributary 4 11.0
END DESCRIPTION:
XS GIS Cut Line= 3
      2138774.99     13851475.02      2138975.00     13851075.00
      2138724.99     13850824.99
#Sta/Elev= 30
  4548.4 1163.51  4696.6 1158.35  4778.1 1157.27  4830.7 1157.84  4847.5 1155.79
  4853.1 1155.91  4861.5 1154.60  4875.4 1154.21  4892.2 1152.76  4897.8 1153.12
  4915.1 1152.19  4920.2 1152.30  4936.9 1149.87  4942.5 1150.53  4959.3 1148.65
  4964.9 1149.02  4981.7 1147.56  5007.0 1146.97  5007.4 1146.47  5012.1 1146.47
  5012.6 1146.97  5023.9 1147.37  5038.1 1148.84  5052.2 1149.22  5066.3 1150.95
  5089.1 1151.56  5179.5 1155.69  5236.0 1160.65  5249.3 1160.84  5349.2 1162.66
#Mann=7,-1,0
  4548.4    0.12       0  4778.1    0.07       0  4915.1    0.12       0
  5007.0    0.05       0  5012.6    0.12       0  5089.1    0.07       0
  5249.3    0.12       0
Bank Sta=5007,5012.6
Exp/Cntr=0.3,0.1

Type RM Length L Ch R = 1,5079,470,470,470
BEGIN DESCRIPTION:
Swine Tributary 4 10.0
END DESCRIPTION:
XS GIS Cut Line= 3
      2139125.03     13851374.96      2139375.00     13851025.00
      2139475.01     13850924.99
#Sta/Elev= 30
  4569.9 1157.87  4598.1 1157.02  4642.4 1154.16  4648.5 1154.27  4687.6 1152.57
  4705.0 1151.47  4713.6 1152.48  4728.4 1152.53  4741.9 1152.05  4749.3 1150.90
  4755.4 1150.68  4870.9 1148.04  4891.8 1147.10  4900.4 1147.49  4924.3 1146.33
  4950.8 1144.00  4963.1 1141.11  4986.5 1139.61  4992.6 1138.61  4993.9 1137.63
  4994.4 1137.13  4999.4 1137.13  4999.9 1137.63  5003.5 1137.63  5014.1 1140.06
  5028.3 1147.56  5035.3 1149.21  5056.5 1151.05  5099.0 1157.33  5141.4 1160.35
#Mann=5,-1,0
  4569.9    0.12       0  4687.6    0.07       0  4924.3    0.12       0
  4993.9    0.05       0  4999.9    0.12       0
Bank Sta=4993.9,4999.9
Exp/Cntr=0.3,0.1

Type RM Length L Ch R = 1,4609,444,444,444
BEGIN DESCRIPTION:
Swine Tributary 4 9.0
END DESCRIPTION:
XS GIS Cut Line= 3
      2139625.00     13851574.99      2139725.00     13851325.00
      2139775.01     13851174.97
#Sta/Elev= 30
  4730.5 1157.91  4745.3 1157.02  4762.8 1153.57  4769.5 1151.99  4774.9 1151.41
  4805.9 1149.15  4853.0 1146.50  4870.5 1144.36  4877.2 1143.31  4882.6 1142.10
  4892.0 1141.39  4923.3 1140.48  4945.9 1139.95  4978.2 1138.46  4990.3 1138.32
  4997.1 1136.34  5002.4 1136.34  5007.2 1134.84  5007.7 1134.34  5012.8 1134.34
  5013.3 1134.84  5020.8 1137.09  5031.4 1141.33  5041.9 1145.09  5052.5 1149.71
  5084.1 1150.17  5094.6 1155.09  5126.2 1157.78  5133.3 1157.95  5157.9 1158.99
#Mann=5,-1,0
  4730.5    0.12       0  4923.3    0.07       0  5007.2    0.05       0
  5013.3    0.07       0  5133.3    0.12       0
Bank Sta=5007.2,5013.3
Exp/Cntr=0.3,0.1

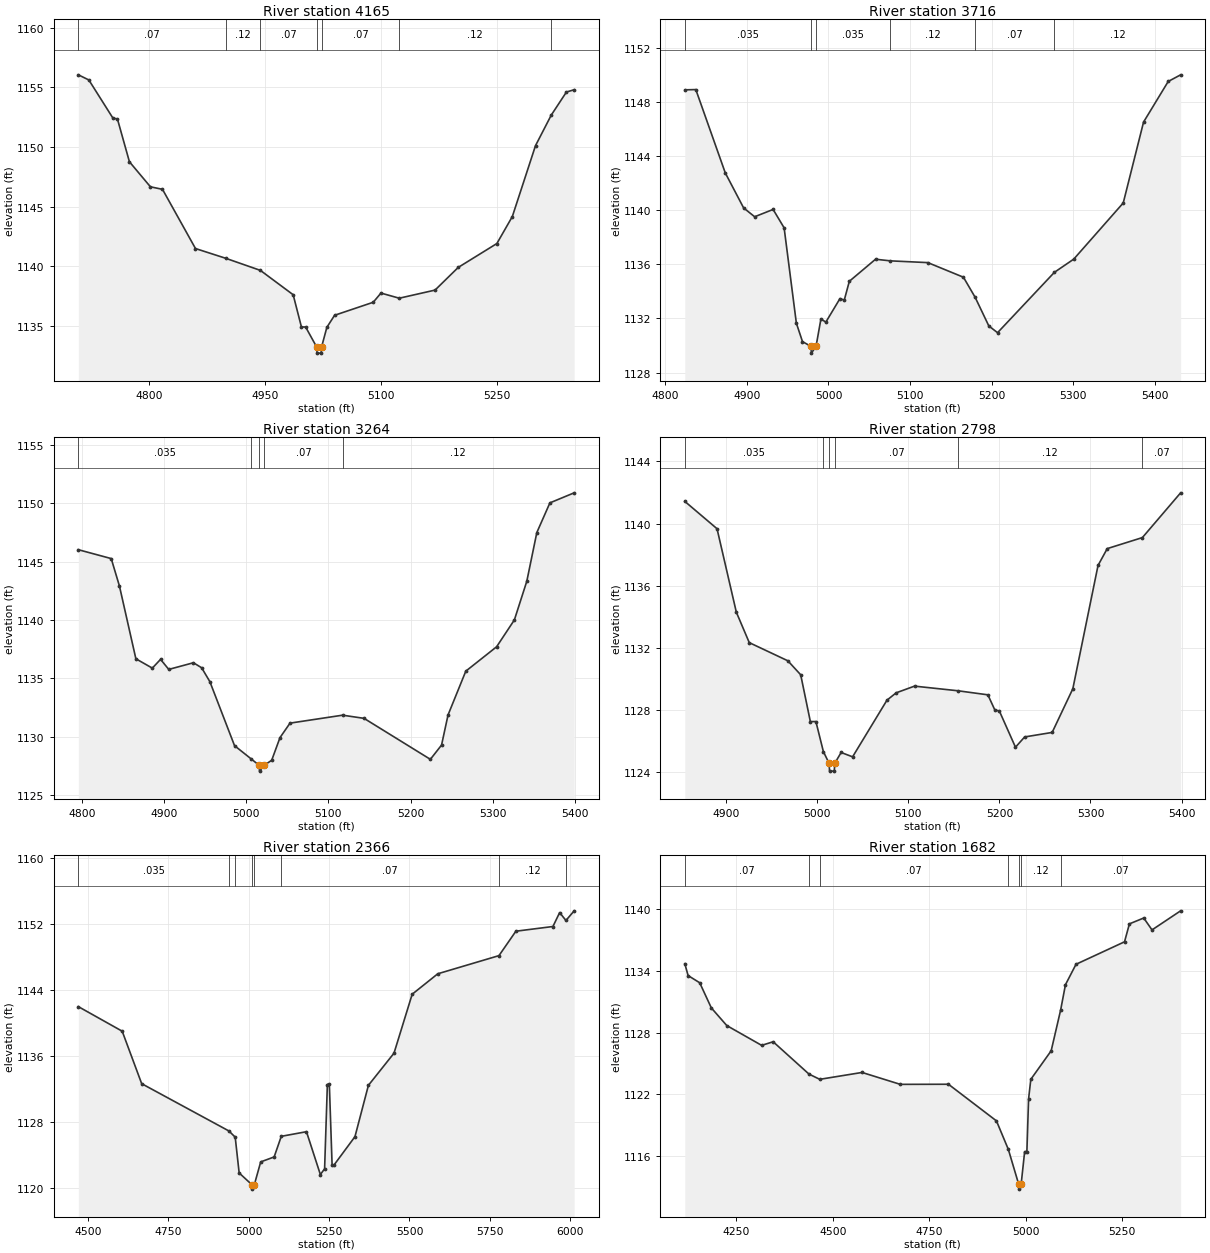
Type RM Length L Ch R = 1,4165,449,449,449
BEGIN DESCRIPTION:
Swine Tributary 4 8.0
END DESCRIPTION:
XS GIS Cut Line= 3
      2139774.98     13851775.01      2140025.00     13851625.00
      2140025.00     13851274.97
#Sta/Elev= 30
  4708.4 1156.04  4722.0 1155.61  4753.1 1152.42  4759.0 1152.34  4774.5 1148.76
  4801.7 1146.66  4817.3 1146.45  4860.0 1141.49  4899.3 1140.67  4944.0 1139.66
  4986.4 1137.62  4997.1 1134.92  5002.5 1134.92  5016.9 1133.23  5017.4 1132.73
  5022.6 1132.73  5023.1 1133.23  5030.0 1134.89  5040.0 1135.90  5090.0 1136.99
  5100.0 1137.76  5123.7 1137.33  5170.0 1138.01  5200.0 1139.91  5250.0 1141.91
  5270.0 1144.17  5300.0 1150.11  5320.4 1152.67  5340.0 1154.60  5350.0 1154.79
#Mann=7,-1,0
  4708.4    0.07       0  4899.3    0.12       0  4944.0    0.07       0
  5016.9    0.05       0  5023.1    0.07       0  5123.7    0.12       0
  5320.4   0.063       0
Bank Sta=5016.9,5023.1
Exp/Cntr=0.3,0.1

Type RM Length L Ch R = 1,3716,452,452,452
BEGIN DESCRIPTION:
Swine Tributary 4 7.0
END DESCRIPTION:
XS GIS Cut Line= 3
      2140275.00     13852025.00      2140375.00     13851875.00
      2140525.01     13851474.98
#Sta/Elev= 30
  4824.0 1148.90  4837.5 1148.92  4873.6 1142.76  4896.1 1140.17  4909.6 1139.52
  4932.2 1140.06  4945.7 1138.70  4960.7 1131.65  4968.2 1130.29  4978.6 1129.94
  4979.1 1129.44  4984.8 1129.94  4990.8 1131.97  4996.8 1131.73  5014.1 1133.47
  5019.4 1133.36  5025.6 1134.75  5057.7 1136.38  5075.9 1136.26  5121.8 1136.13
  5165.4 1135.05  5179.8 1133.56  5196.5 1131.45  5207.2 1130.95  5276.8 1135.41
  5300.6 1136.39  5361.2 1140.54  5386.1 1146.52  5416.3 1149.52  5431.5 1150.01
#Mann=6,-1,0
  4824.0   0.035       0  4978.6   0.035       0  4984.8   0.035       0
  5075.9    0.12       0  5179.8    0.07       0  5276.8    0.12       0
Bank Sta=4978.6,4984.8
Exp/Cntr=0.3,0.1

Type RM Length L Ch R = 1,3264,466,466,466
BEGIN DESCRIPTION:
Swine Tributary 4 6.0
END DESCRIPTION:
XS GIS Cut Line= 3
      2140775.00     13852224.96      2140775.00     13852025.00
      2140975.01     13851674.98
#Sta/Elev= 30
  4795.8 1146.02  4835.8 1145.26  4845.8 1142.91  4865.8 1136.68  4885.8 1135.88
  4895.8 1136.63  4905.8 1135.77  4935.8 1136.34  4945.8 1135.91  4955.8 1134.72
  4985.8 1129.24  5005.8 1128.12  5015.7 1127.56  5016.2 1127.06  5021.9 1127.56
  5031.0 1127.99  5041.1 1129.93  5053.3 1131.17  5117.2 1131.85  5143.3 1131.58
  5224.0 1128.07  5237.6 1129.29  5245.5 1131.87  5267.1 1135.62  5304.6 1137.71
  5326.2 1140.01  5341.3 1143.32  5353.5 1147.49  5369.4 1150.03  5398.9 1150.89
#Mann=5,-1,0
  4795.8   0.035       0  5005.8    0.07       0  5015.7   0.035       0
  5021.9    0.07       0  5117.2    0.12       0
Bank Sta=5015.7,5021.9
Exp/Cntr=0.3,0.1

Type RM Length L Ch R = 1,2798,432,432,432
BEGIN DESCRIPTION:
Swine Tributary 4 5.0
END DESCRIPTION:
XS GIS Cut Line= 3
      2141074.97     13852325.03      2141175.00     13852225.00
      2141225.00     13851824.98
#Sta/Elev= 30
  4854.4 1141.43  4889.8 1139.67  4911.0 1134.30  4925.2 1132.34  4967.6 1131.17
  4981.7 1130.27  4992.3 1127.26  4998.4 1127.26  5006.6 1125.33  5012.9 1124.57
  5013.4 1124.07  5018.6 1124.07  5019.1 1124.57  5026.1 1125.27  5038.7 1124.99
  5076.5 1128.64  5086.6 1129.11  5106.7 1129.54  5154.6 1129.24  5187.3 1128.98
  5194.9 1128.01  5199.9 1127.94  5217.6 1125.61  5227.7 1126.27  5257.9 1126.56
  5280.6 1129.37  5308.3 1137.31  5318.4 1138.39  5357.0 1139.10  5399.0 1141.98
#Mann=6,-1,0
  4854.4   0.035       0  5006.6    0.07       0  5012.9   0.035       0
  5019.1    0.07       0  5154.6    0.12       0  5357.0    0.07       0
Bank Sta=5012.9,5019.1
Exp/Cntr=0.3,0.1

Type RM Length L Ch R = 1,2366,684,684,684
BEGIN DESCRIPTION:
Swine Tributary 4 4.0
END DESCRIPTION:
XS GIS Cut Line= 3
      2141049.97     13852400.00      2141575.00     13852325.00
      2142168.06     13851505.68
#Sta/Elev= 30
  4470.3 1141.96  4606.7 1138.98  4667.3 1132.62  4938.5 1126.89  4958.1 1126.14
  4970.4 1121.80  5011.1 1120.34  5011.6 1119.84  5017.3 1120.34  5037.4 1123.14
  5079.2 1123.74  5101.4 1126.24  5179.7 1126.80  5222.9 1121.61  5236.1 1122.30
  5244.7 1132.52  5250.8 1132.59  5259.4 1122.76  5265.5 1122.77  5330.5 1126.20
  5372.3 1132.42  5451.9 1136.32  5508.4 1143.46  5588.0 1145.94  5778.3 1148.14
  5830.9 1151.10  5946.1 1151.67  5967.0 1153.36  5986.5 1152.40  6012.1 1153.57
#Mann=8,-1,0
  4470.3   0.035       0  4938.5    0.07       0  4958.1   0.035       0
  5011.1   0.035       0  5017.3   0.035       0  5101.4    0.07       0
  5778.3    0.12       0  5986.5    0.07       0
Bank Sta=5011.1,5017.3
Exp/Cntr=0.3,0.1

Type RM Length L Ch R = 1,1682,539,539,539
BEGIN DESCRIPTION:
Swine Tributary 4 3.0
END DESCRIPTION:
XS GIS Cut Line= 4
      2141336.38     13852591.99      2141897.92     13852615.16
      2142195.48     13852494.80      2142400.01     13852149.99
#Sta/Elev= 30
  4117.0 1134.71  4125.6 1133.55  4155.6 1132.85  4185.7 1130.40  4225.7 1128.68
  4316.0 1126.75  4345.8 1127.10  4438.6 1123.95  4466.5 1123.44  4576.0 1124.11
  4675.0 1122.95  4799.7 1122.96  4924.0 1119.39  4954.8 1116.61  4981.4 1113.24
  4981.9 1112.74  4988.0 1113.24  4997.0 1116.39  5002.8 1116.39  5007.2 1121.53
  5013.0 1123.44  5065.7 1126.22  5090.2 1130.19  5102.7 1132.66  5130.0 1134.65
  5255.6 1136.84  5268.3 1138.59  5305.4 1139.16  5326.8 1138.00  5400.9 1139.86
#Mann=7,-1,0
  4117.0    0.07       0  4438.6   0.035       0  4466.5    0.07       0
  4954.8    0.12       0  4981.4    0.05       0  4988.0    0.12       0
  5090.2    0.07       0
Bank Sta=4981.4,4988
Exp/Cntr=0.3,0.1

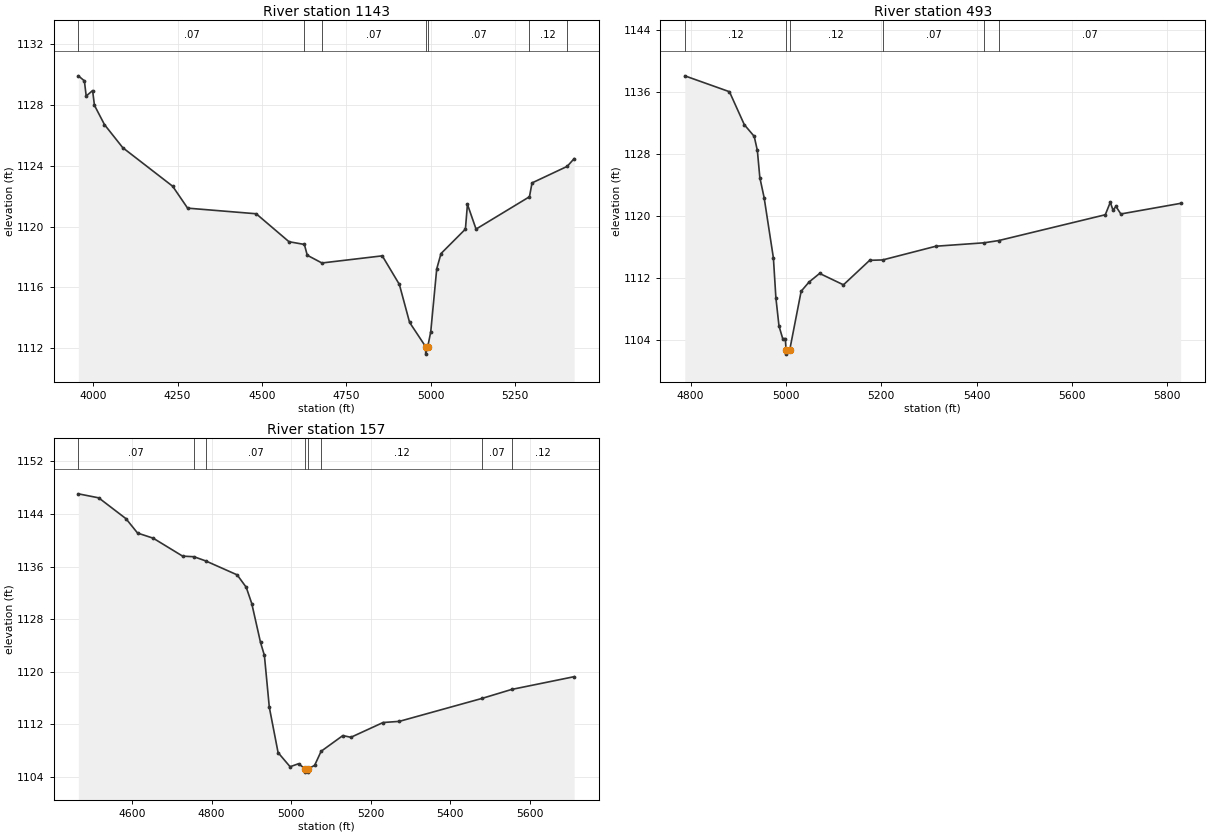
Type RM Length L Ch R = 1,1143,650,650,650
BEGIN DESCRIPTION:
Swine Tributary 4 2.0
END DESCRIPTION:
XS GIS Cut Line= 5
      2141375.01     13852672.75      2142012.55     13852924.31
      2142366.98     13852978.31      2142455.97     13852940.77
      2142557.94     13852628.79
#Sta/Elev= 30
  3956.1 1129.93  3974.0 1129.60  3979.4 1128.60  3998.4 1128.96  4003.8 1127.99
  4033.5 1126.72  4087.7 1125.20  4235.6 1122.66  4279.8 1121.22  4482.9 1120.85
  4580.1 1119.01  4625.7 1118.83  4634.2 1118.12  4677.6 1117.61  4856.4 1118.08
  4907.0 1116.20  4937.3 1113.70  4984.6 1112.11  4985.1 1111.61  4991.2 1112.11
  5000.0 1113.08  5017.7 1117.22  5030.4 1118.23  5102.7 1119.84  5108.7 1121.47
  5134.2 1119.84  5292.4 1121.97  5300.0 1122.88  5404.2 1123.97  5424.8 1124.48
#Mann=7,-1,0
  3956.1    0.07       0  4625.7   0.035       0  4677.6    0.07       0
  4984.6    0.05       0  4991.2    0.07       0  5292.4    0.12       0
  5404.2    0.07       0
Bank Sta=4984.6,4991.2
Exp/Cntr=0.3,0.1

Type RM Length L Ch R = 1,493,336,336,336
BEGIN DESCRIPTION:
Swine Tributary 4 1.0
END DESCRIPTION:
XS GIS Cut Line= 3
      2141974.90     13853582.25      2142175.00     13853525.00
      2142555.19     13852784.31
#Sta/Elev= 30
  4787.7 1138.11  4881.4 1136.06  4912.6 1131.81  4933.4 1130.30  4940.0 1128.48
  4945.2 1124.98  4954.2 1122.40  4973.7 1114.60  4978.9 1109.47  4985.4 1105.84
  4993.2 1104.21  4998.6 1104.21  5000.4 1102.71  5000.9 1102.21  5007.8 1102.71
  5031.9 1110.32  5048.5 1111.51  5070.7 1112.62  5120.7 1111.15  5175.7 1114.31
  5203.0 1114.36  5314.8 1116.13  5415.8 1116.57  5446.6 1116.86  5670.3 1120.19
  5680.8 1121.80  5686.4 1120.79  5692.7 1121.26  5702.9 1120.29  5828.4 1121.66
#Mann=6,-1,0
  4787.7    0.12       0  5000.4    0.05       0  5007.8    0.12       0
  5203.0    0.07       0  5415.8    0.12       0  5446.6    0.07       0
Bank Sta=5000.4,5007.8
Exp/Cntr=0.3,0.1

Type RM Length L Ch R = 1,157,0,0,0
BEGIN DESCRIPTION:
Swine Tributary 4 0.0
END DESCRIPTION:
XS GIS Cut Line= 3
      2141949.99     13853950.01      2142434.81     13853723.32
      2142545.97     13853020.46
#Sta/Elev= 30
  4464.8 1147.07  4516.0 1146.46  4584.6 1143.29  4613.8 1141.10  4653.1 1140.32
  4727.1 1137.59  4755.6 1137.50  4784.8 1136.87  4864.2 1134.74  4887.0 1132.85
  4900.9 1130.38  4922.9 1124.47  4932.7 1122.48  4945.0 1114.61  4967.1 1107.70
  4997.3 1105.55  5018.6 1106.01  5035.0 1105.23  5035.5 1104.73  5042.0 1104.73
  5042.5 1105.23  5059.0 1105.76  5075.3 1107.90  5129.9 1110.29  5150.2 1110.03
  5231.2 1112.28  5271.7 1112.45  5479.6 1115.94  5554.4 1117.31  5711.6 1119.25
#Mann=8,-1,0
  4464.8    0.07       0  4755.6   0.035       0  4784.8    0.07       0
  5035.0    0.05       0  5042.5    0.07       0  5075.3    0.12       0
  5479.6    0.07       0  5554.4    0.12       0
Bank Sta=5035,5042.5
Exp/Cntr=0.3,0.1

Chan Stop Cuts=-1