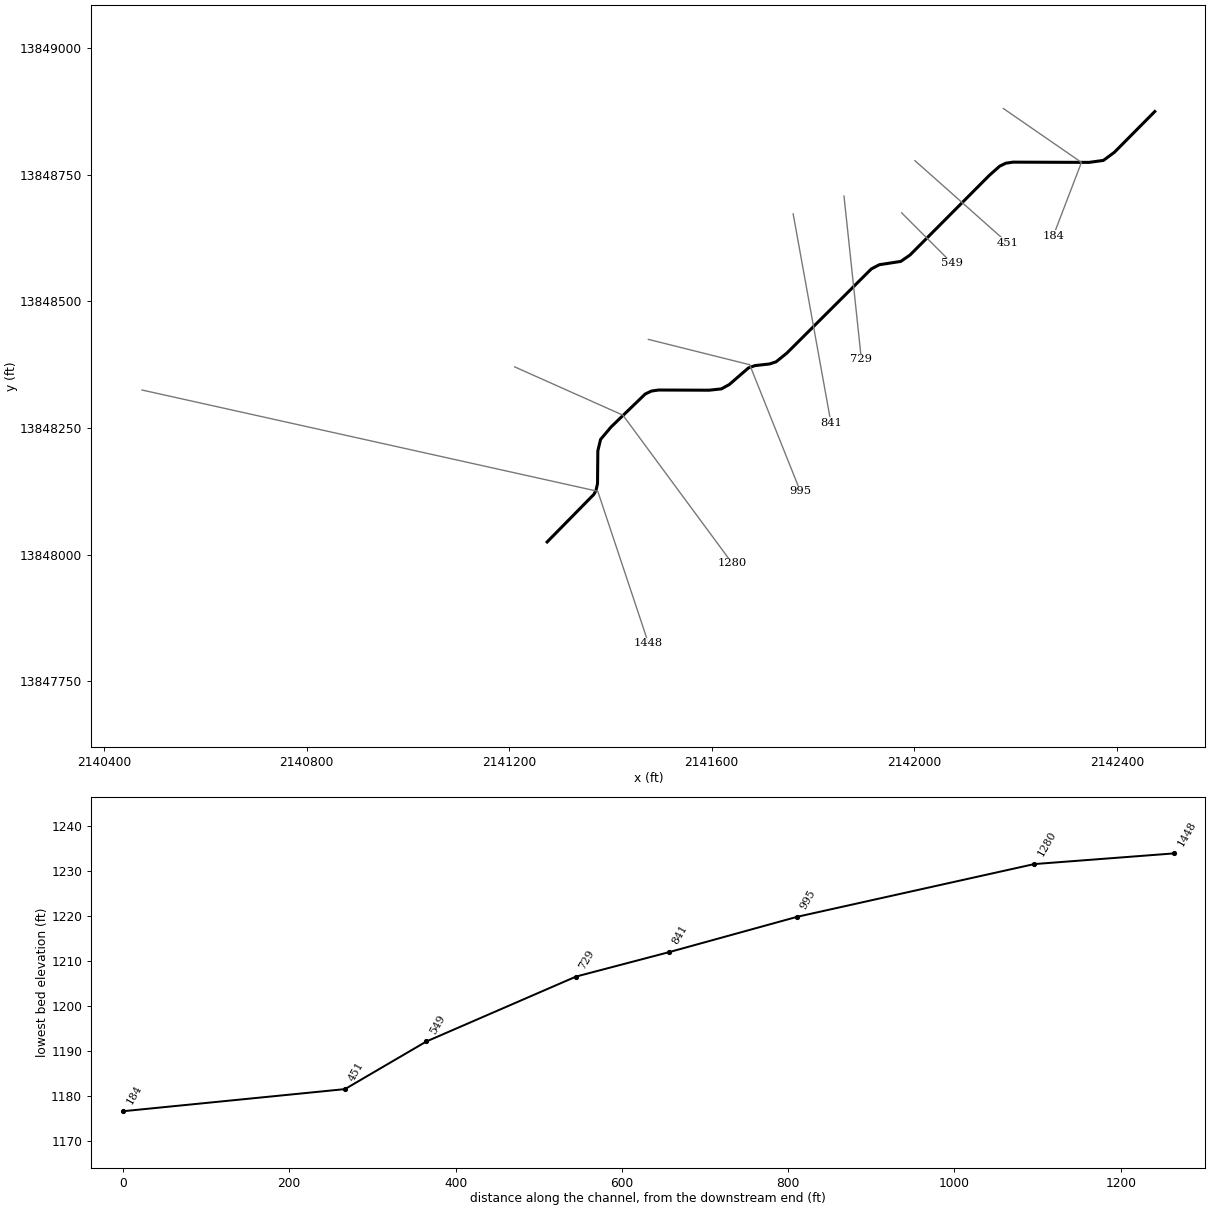
--- Swine Tributary 6.prj (project) ---

Proj Title=Swine Tributary 6 Base Level Engineering
Current Plan=p01
Default Exp/Contr=0.3,0.1
English Units
Geom File=g01
Flow File=f01
Plan File=p01
BEGIN DESCRIPTION:
Swine Tributary 6
END DESCRIPTION:

--- Swine Tributary 6.p01 (plan) ---

Plan Title=Multiple Run
Short Identifier=Multiple
Geom File=g01
Flow File=f01
Subcritical Flow
K Sum by GR= 0
Std Step Tol= 0.01
Critical Tol= 0.01
Num of Std Step Trials= 20
Max Error Tol= 0.3
Flow Tol Ratio= 0.001
Split Flow NTrial= 30
Split Flow Tol= 0.02
Split Flow Ratio= 0.02
Log Output Level= 0
Friction Slope Method= 1
Unsteady Friction Slope Method= 2
Unsteady Bridges Friction Slope Method= 1
Parabolic Critical Depth
Global Vel Dist=  1 , 1 , 1
Global Log Level= 0
CheckData=True
Encroach Param= -1, 0, 0, 0
BEGIN DESCRIPTION:
Multiple Run
END DESCRIPTION:

--- Swine Tributary 6.f01 (steady flow) ---

Flow Title=Multiple
Number of Profiles=7
Profile Names=10-year,25-year,50-year,1pct_min,100-year,1pct_plu,500-year
River Rch & RM= Swine Tributary ,Reach-1,1448
     140     206     260     160     320     639     477
Boundary for River Rch & Prof#=Swine Tributary ,Reach-1,1
Up Type=0
Dn Type=3
Dn Slope=0.005
Boundary for River Rch & Prof#=Swine Tributary ,Reach-1,2
Up Type=0
Dn Type=3
Dn Slope=0.005
Boundary for River Rch & Prof#=Swine Tributary ,Reach-1,3
Up Type=0
Dn Type=3
Dn Slope=0.005
Boundary for River Rch & Prof#=Swine Tributary ,Reach-1,4
Up Type=0
Dn Type=3
Dn Slope=0.005
Boundary for River Rch & Prof#=Swine Tributary ,Reach-1,5
Up Type=0
Dn Type=3
Dn Slope=0.005
Boundary for River Rch & Prof#=Swine Tributary ,Reach-1,6
Up Type=0
Dn Type=3
Dn Slope=0.005
Boundary for River Rch & Prof#=Swine Tributary ,Reach-1,7
Up Type=0
Dn Type=3
Dn Slope=0.005

--- Swine Tributary 6.g01 (geometry) ---

Geom Title=Existing Conditions

River Reach=Swine Tributary ,Reach-1
Reach XY= 30
      2141275.00     13848025.00      2141367.21     13848118.80
      2141371.43     13848126.48      2141374.49     13848140.21
      2141375.13     13848204.95      2141380.52     13848227.44
      2141401.15     13848251.94      2141468.79     13848317.19
      2141480.85     13848322.94      2141494.99     13848325.02
      2141595.14     13848324.67      2141619.07     13848327.25
      2141634.67     13848335.80      2141672.83     13848368.86
      2141685.71     13848373.28      2141714.38     13848376.50
      2141727.30     13848380.83      2141748.47     13848398.01
      2141915.32     13848564.22      2141931.05     13848572.47
      2141973.35     13848578.98      2141991.67     13848591.65
      2142148.13     13848748.83      2142168.81     13848767.19
      2142180.85     13848772.94      2142194.98     13848775.04
      2142345.18     13848774.57      2142373.56     13848778.48
      2142395.21     13848794.50      2142475.00     13848875.00

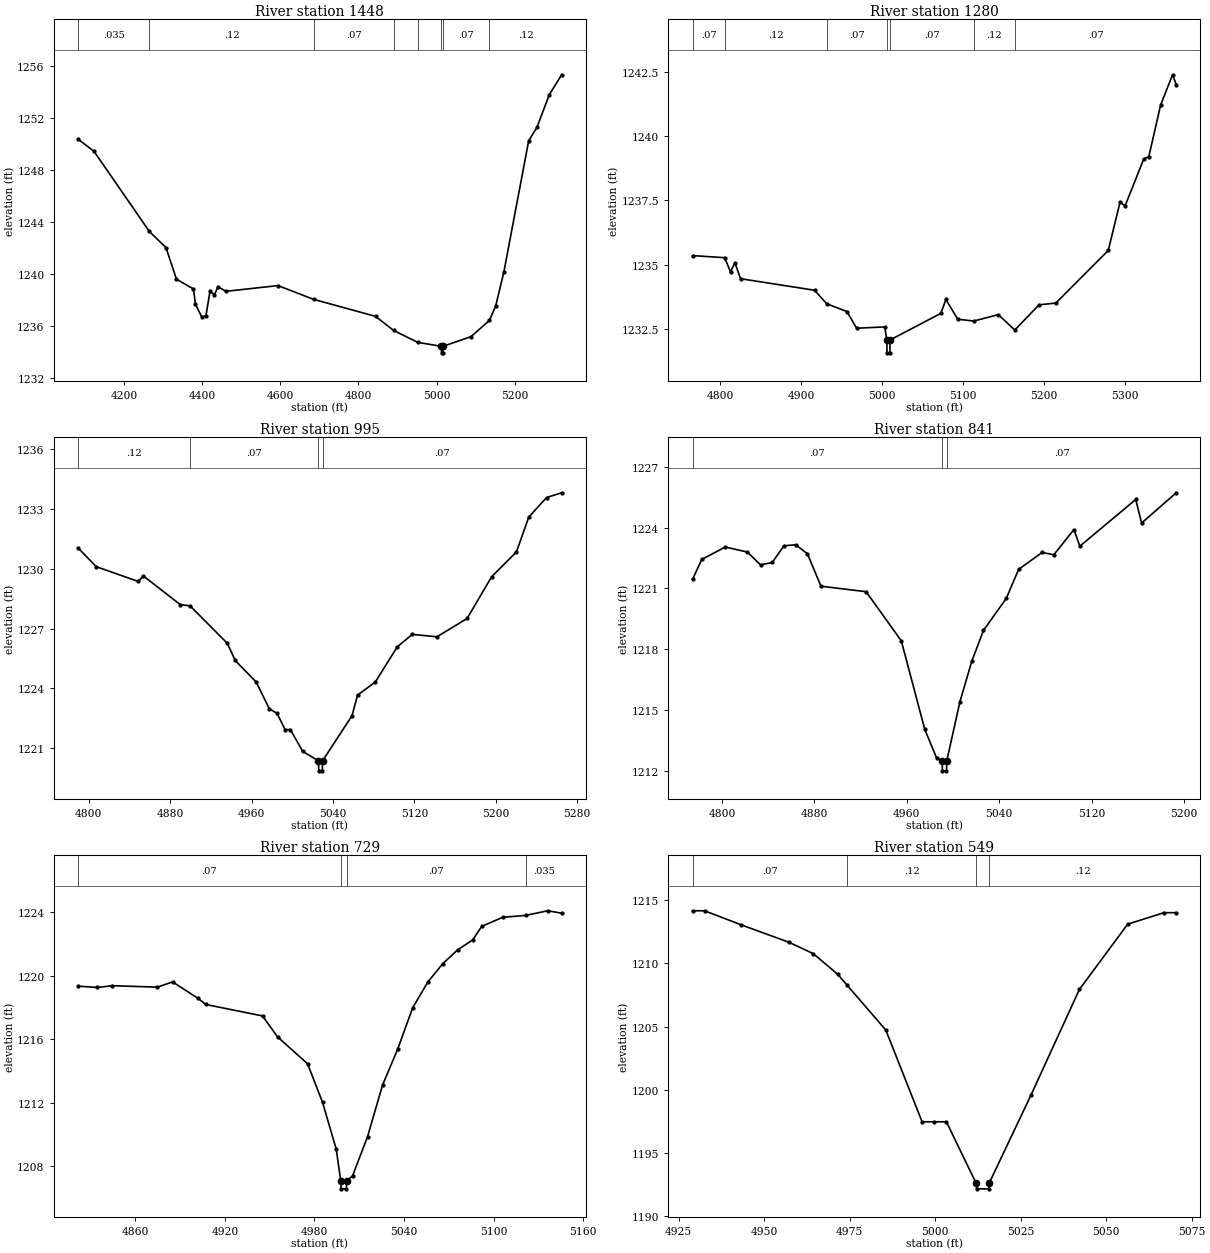
Type RM Length L Ch R = 1,1448,168,168,168
BEGIN DESCRIPTION:
Swine Tributary 6 3.0
END DESCRIPTION:
XS GIS Cut Line= 3
      2140475.00     13848325.00      2141375.00     13848125.00
      2141475.00     13847824.99
#Sta/Elev= 30
  4082.0 1250.40  4123.0 1249.46  4264.9 1243.28  4307.4 1242.04  4334.3 1239.60
  4377.8 1238.85  4382.9 1237.67  4399.6 1236.66  4409.8 1236.80  4420.1 1238.67
  4431.6 1238.41  4440.5 1239.02  4461.0 1238.67  4594.2 1239.11  4685.3 1238.05
  4843.9 1236.74  4889.9 1235.66  4951.4 1234.74  5012.5 1234.43  5012.8 1233.93
  5016.3 1233.93  5016.5 1234.43  5088.3 1235.18  5135.4 1236.43  5151.5 1237.55
  5172.6 1240.19  5235.9 1250.27  5256.9 1251.29  5288.6 1253.81  5320.2 1255.35
#Mann=8,-1,0
  4082.0   0.035       0  4264.9    0.12       0  4685.3    0.07       0
  4889.9    0.12       0  4951.4    0.07       0  5012.5    0.05       0
  5016.5    0.07       0  5135.4    0.12       0
Bank Sta=5012.5,5016.5
Exp/Cntr=0.3,0.1

Type RM Length L Ch R = 1,1280,285,285,285
BEGIN DESCRIPTION:
Swine Tributary 6 2.5
END DESCRIPTION:
XS GIS Cut Line= 3
      2141210.86     13848370.72      2141424.66     13848275.35
      2141640.33     13847982.99
#Sta/Elev= 30
  4765.9 1235.35  4805.5 1235.27  4812.8 1234.72  4818.2 1235.07  4825.2 1234.45
  4916.6 1234.00  4931.7 1233.47  4956.6 1233.17  4968.5 1232.52  5003.3 1232.57
  5005.8 1232.06  5006.1 1231.56  5009.6 1231.56  5009.8 1232.06  5072.6 1233.10
  5078.8 1233.64  5093.4 1232.87  5113.4 1232.80  5143.5 1233.05  5163.9 1232.45
  5193.7 1233.43  5214.5 1233.50  5279.3 1235.55  5293.9 1237.44  5300.1 1237.29
  5323.2 1239.12  5329.4 1239.21  5344.0 1241.22  5358.7 1242.40  5363.3 1242.02
#Mann=7,-1,0
  4765.9    0.07       0  4805.5    0.12       0  4931.7    0.07       0
  5005.8    0.05       0  5009.8    0.07       0  5113.4    0.12       0
  5163.9    0.07       0
Bank Sta=5005.8,5009.8
Exp/Cntr=0.3,0.1

Type RM Length L Ch R = 1,995,154,154,154
BEGIN DESCRIPTION:
Swine Tributary 6 2.0
END DESCRIPTION:
XS GIS Cut Line= 3
      2141475.03     13848424.99      2141675.00     13848375.00
      2141775.01     13848124.99
#Sta/Elev= 30
  4789.3 1231.06  4807.3 1230.11  4848.5 1229.37  4853.7 1229.64  4889.8 1228.21
  4899.6 1228.14  4936.2 1226.26  4943.9 1225.40  4964.5 1224.32  4977.4 1222.98
  4985.1 1222.74  4992.9 1221.93  4998.1 1221.93  5010.2 1220.84  5025.7 1220.36
  5026.0 1219.86  5029.5 1219.86  5029.7 1220.36  5058.7 1222.63  5064.1 1223.66
  5081.6 1224.32  5103.1 1226.08  5117.9 1226.71  5142.2 1226.59  5171.8 1227.51
  5196.0 1229.61  5220.3 1230.85  5232.4 1232.60  5249.9 1233.58  5264.7 1233.82
#Mann=4,-1,0
  4789.3    0.12       0  4899.6    0.07       0  5025.7    0.05       0
  5029.7    0.07       0
Bank Sta=5025.7,5029.7
Exp/Cntr=0.3,0.1

Type RM Length L Ch R = 1,841,112,112,112
BEGIN DESCRIPTION:
Swine Tributary 6 1.2
END DESCRIPTION:
XS GIS Cut Line= 2
      2141760.85     13848672.91      2141835.39     13848260.70
#Sta/Elev= 30
  4774.4 1221.45  4782.4 1222.43  4802.8 1223.04  4821.9 1222.79  4833.3 1222.16
  4843.4 1222.28  4853.6 1223.10  4863.7 1223.15  4873.9 1222.71  4885.6 1221.11
  4924.7 1220.84  4955.2 1218.42  4975.5 1214.06  4985.7 1212.66  4990.6 1212.52
  4990.8 1212.02  4994.3 1212.02  4994.6 1212.52  5006.0 1215.43  5016.2 1217.41
  5026.3 1218.93  5046.1 1220.51  5056.8 1221.94  5077.1 1222.77  5087.3 1222.66
  5104.7 1223.90  5109.8 1223.08  5158.2 1225.38  5163.3 1224.22  5193.3 1225.71
#Mann=3,-1,0
  4774.4    0.07       0  4990.6    0.05       0  4994.6    0.07       0
Bank Sta=4990.6,4994.6
Exp/Cntr=0.3,0.1

Type RM Length L Ch R = 1,729,180,180,180
BEGIN DESCRIPTION:
Swine Tributary 6 1.1
END DESCRIPTION:
XS GIS Cut Line= 2
      2141861.24     13848708.00      2141895.54     13848385.72
#Sta/Elev= 30
  4821.5 1219.33  4834.6 1219.25  4844.6 1219.36  4874.8 1219.27  4884.9 1219.60
  4902.1 1218.56  4907.1 1218.18  4945.2 1217.46  4955.3 1216.14  4975.4 1214.45
  4985.4 1212.03  4994.6 1209.08  4997.6 1207.09  4997.9 1206.59  5001.4 1206.59
  5001.6 1207.09  5005.5 1207.40  5015.6 1209.88  5025.6 1213.11  5035.7 1215.36
  5045.8 1217.97  5055.8 1219.57  5065.9 1220.74  5075.9 1221.61  5086.0 1222.24
  5092.1 1223.09  5106.1 1223.66  5121.5 1223.78  5136.3 1224.07  5145.6 1223.92
#Mann=4,-1,0
  4821.5    0.07       0  4997.6    0.05       0  5001.6    0.07       0
  5121.5   0.035       0
Bank Sta=4997.6,5001.6
Exp/Cntr=0.3,0.1

Type RM Length L Ch R = 1,549,98,98,98
BEGIN DESCRIPTION:
Swine Tributary 6 1.0
END DESCRIPTION:
XS GIS Cut Line= 3
      2141975.03     13848674.97      2142025.00     13848625.00
      2142075.02     13848574.98
#Sta/Elev= 20
  4929.1 1214.16  4932.6 1214.16  4943.2 1213.06  4957.3 1211.67  4964.4 1210.77
  4971.5 1209.15  4974.3 1208.27  4985.6 1204.73  4996.2 1197.48  4999.8 1197.48
  5003.3 1197.48  5011.9 1192.68  5012.2 1192.18  5015.7 1192.18  5015.9 1192.68
  5028.0 1199.57  5042.2 1207.95  5056.3 1213.10  5066.9 1214.01  5070.5 1214.01
#Mann=4,-1,0
  4929.1    0.07       0  4974.3    0.12       0  5011.9    0.05       0
  5015.9    0.12       0
Bank Sta=5011.9,5015.9
Exp/Cntr=0.3,0.1

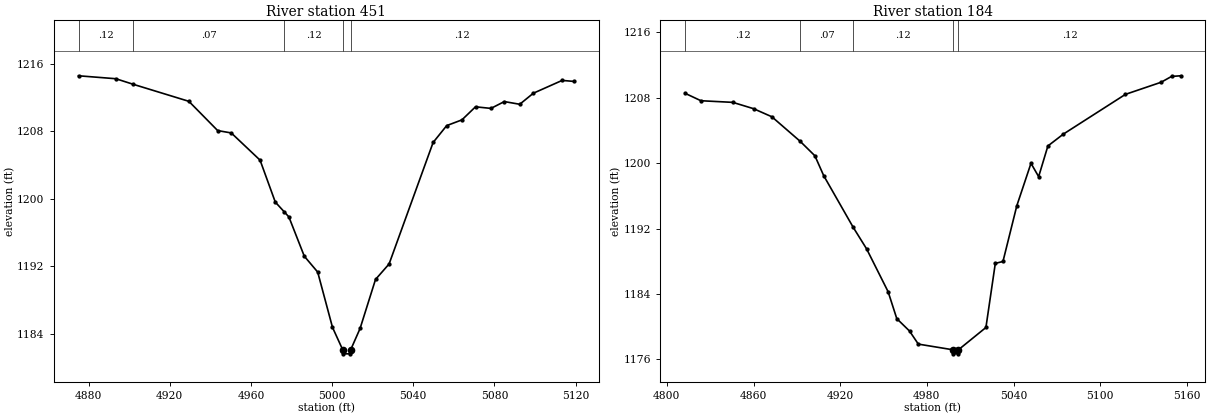
Type RM Length L Ch R = 1,451,267,267,267
BEGIN DESCRIPTION:
Swine Tributary 6 0.2
END DESCRIPTION:
XS GIS Cut Line= 2
      2142001.38     13848777.93      2142184.08     13848615.75
#Sta/Elev= 30
  4875.0 1214.58  4893.4 1214.23  4902.1 1213.56  4929.4 1211.55  4943.6 1208.08
  4950.3 1207.80  4964.5 1204.57  4972.0 1199.60  4976.5 1198.42  4978.7 1197.84
  4986.3 1193.18  4992.9 1191.30  5000.2 1184.74  5005.2 1182.10  5005.4 1181.60
  5008.9 1181.60  5009.2 1182.10  5013.8 1184.61  5021.4 1190.42  5028.1 1192.26
  5049.8 1206.67  5056.5 1208.67  5064.0 1209.35  5070.7 1210.90  5078.3 1210.71
  5084.9 1211.52  5092.5 1211.20  5099.2 1212.51  5113.4 1214.03  5119.3 1213.91
#Mann=5,-1,0
  4875.0    0.12       0  4902.1    0.07       0  4976.5    0.12       0
  5005.2    0.05       0  5009.2    0.12       0
Bank Sta=5005.2,5009.2
Exp/Cntr=0.3,0.1

Type RM Length L Ch R = 1,184,0,0,0
BEGIN DESCRIPTION:
Swine Tributary 6 0.1
END DESCRIPTION:
XS GIS Cut Line= 3
      2142175.97     13848880.99      2142330.19     13848774.53
      2142274.47     13848629.15
#Sta/Elev= 30
  4812.6 1208.54  4823.6 1207.63  4845.7 1207.43  4860.0 1206.66  4872.7 1205.67
  4892.3 1202.67  4902.5 1200.90  4908.6 1198.47  4929.0 1192.16  4938.3 1189.52
  4953.2 1184.28  4959.2 1180.99  4968.0 1179.48  4974.1 1177.88  4997.9 1177.19
  4998.1 1176.69  5001.6 1176.69  5001.9 1177.19  5020.9 1179.91  5027.4 1187.75
  5032.7 1187.98  5042.3 1194.80  5052.1 1199.98  5057.4 1198.35  5063.8 1202.10
  5074.5 1203.55  5117.5 1208.41  5142.2 1209.89  5149.4 1210.60  5155.7 1210.68
#Mann=5,-1,0
  4812.6    0.12       0  4892.3    0.07       0  4929.0    0.12       0
  4997.9    0.05       0  5001.9    0.12       0
Bank Sta=4997.9,5001.9
Exp/Cntr=0.3,0.1

Chan Stop Cuts=-1