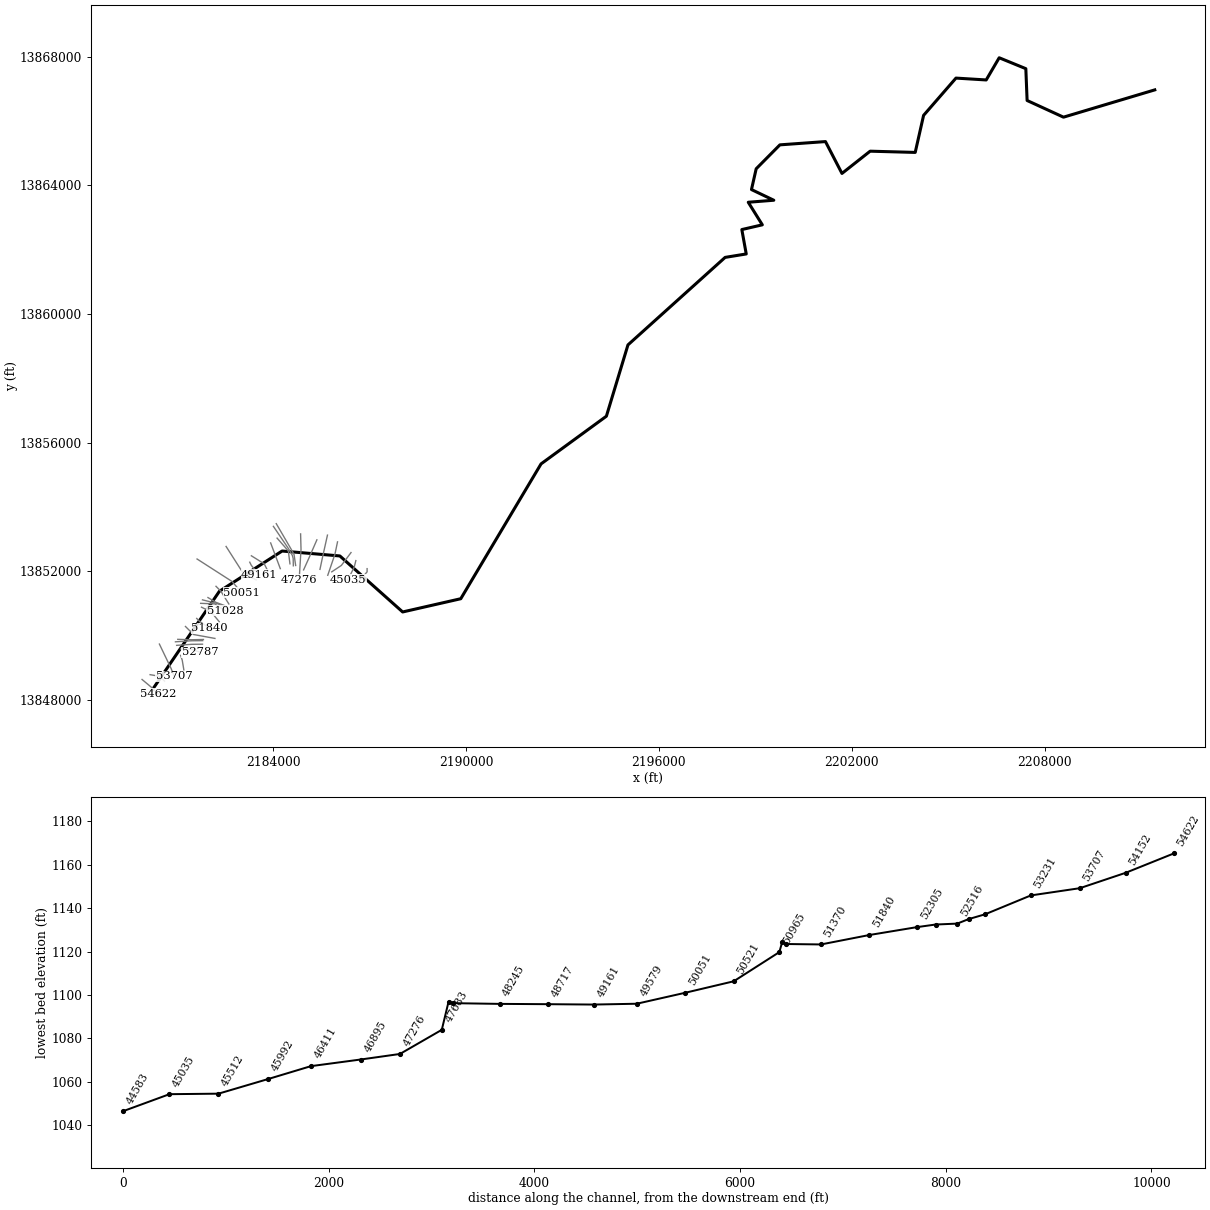
--- Tom Creek.prj (project) ---

Proj Title=Tom Creek Base Level Engineering
Current Plan=p01
Default Exp/Contr=0.3,0.1
English Units
Geom File=g01
Flow File=f01
Plan File=p01
Y Axis Title=Elevation
X Axis Title(PF)=Main Channel Distance
X Axis Title(XS)=Station
BEGIN DESCRIPTION:
Tom Creek
END DESCRIPTION:
DSS Export Rating Curves= 0
DSS Export Rating Curve Sorted= 0
DSS Export Volume Flow Curves= 0
DXF OffsetX= 0
DXF OffsetY= 0
DXF ScaleX= 1
DXF ScaleY= 10

--- Tom Creek.p01 (plan) ---

Plan Title=Multiple Run
Short Identifier=Multiple
Geom File=g01
Flow File=f01
Subcritical Flow
K Sum by GR= 0
Std Step Tol= 0.01
Critical Tol= 0.01
Num of Std Step Trials= 20
Max Error Tol= 0.3
Flow Tol Ratio= 0.001
Split Flow NTrial= 30
Split Flow Tol= 0.02
Split Flow Ratio= 0.02
Log Output Level= 0
Friction Slope Method= 1
Unsteady Friction Slope Method= 2
Unsteady Bridges Friction Slope Method= 1
Parabolic Critical Depth
Global Vel Dist=  1 , 1 , 1
Global Log Level= 0
CheckData=True
Encroach Param= -1, 0, 0, 0
BEGIN DESCRIPTION:
Multiple Run
END DESCRIPTION:

--- Tom Creek.f01 (steady flow) ---

Flow Title=Multiple
Program Version=4.10
Number of Profiles= 7
Profile Names=10-year,25-year,50-year,1pct_min,100-year,1pct_plu,500-year
River Rch & RM=Tom Creek,Reach-1         ,54622
    1169    1992    2780    1880    3751    7484    6756
River Rch & RM=Tom Creek,Reach-1         ,50521
    1870    3263    4626    3171    6328   12626   11724
River Rch & RM=Tom Creek,Reach-1         ,46411
    2200    3866    5503    3786    7555   15074   14101
River Rch & RM=Tom Creek,Reach-1         ,42253
    2956    5268    7572    5254   10484   20918   19910
River Rch & RM=Tom Creek,Reach-1         ,40388
    3796    6824    9864    6877   13722   27378   26312
River Rch & RM=Tom Creek,Reach-1         ,35082
    4430    7994   11586    8094   16150   32223   31092
River Rch & RM=Tom Creek,Reach-1         ,29369
    4760    8607   12488    8732   17423   34764   33605
River Rch & RM=Tom Creek,Reach-1         ,26225
    4861    8766   12694    8857   17671   35259   33932
River Rch & RM=Tom Creek,Reach-1         ,20248
    4932    8866   12811    8915   17789   35493   33983
Boundary for River Rch & Prof#=Tom Creek,Reach-1         , 1
Up Type= 0
Dn Type= 3
Dn Slope=0.002
Boundary for River Rch & Prof#=Tom Creek,Reach-1         , 2
Up Type= 0
Dn Type= 3
Dn Slope=0.002
Boundary for River Rch & Prof#=Tom Creek,Reach-1         , 3
Up Type= 0
Dn Type= 3
Dn Slope=0.002
Boundary for River Rch & Prof#=Tom Creek,Reach-1         , 4
Up Type= 0
Dn Type= 3
Dn Slope=0.002
Boundary for River Rch & Prof#=Tom Creek,Reach-1         , 5
Up Type= 0
Dn Type= 3
Dn Slope=0.002
Boundary for River Rch & Prof#=Tom Creek,Reach-1         , 6
Up Type= 0
Dn Type= 3
Dn Slope=0.002
Boundary for River Rch & Prof#=Tom Creek,Reach-1         , 7
Up Type= 0
Dn Type= 3
Dn Slope=0.002
DSS Import GetInterval= 0
DSS Import GetPeak= 0
DSS Import FillOption= 0

--- Tom Creek.g01 (geometry) ---

Geom Title=Existing Conditions
Program Version=4.10

River Reach=Tom Creek       ,Reach-1
Reach XY= 30
        2180225.       13848275.      2182330.18     13851369.59
      2184280.86     13852622.93      2186077.71      13852469.6
      2188030.83     13850726.53      2189838.23     13851138.57
      2192335.52     13855334.79      2194367.61     13856818.67
      2195038.62     13859038.22       2198061.2     13861761.64
      2198717.66     13861868.61      2198580.35     13862627.74
      2199218.11       13862775.      2198780.34     13863477.74
      2199575.19     13863540.28      2198880.45     13863872.53
      2199027.05     13864519.55      2199764.57     13865264.08
      2201182.01     13865365.97      2201695.06     13864374.49
      2202571.66     13865067.01       2203973.5     13865028.62
      2204234.01     13866182.02      2205241.29     13867341.74
      2206181.68     13867283.95      2206585.64     13867974.44
      2207414.05       13867635.      2207453.92     13866644.78
      2208585.61      13866125.6        2211425.       13866975.

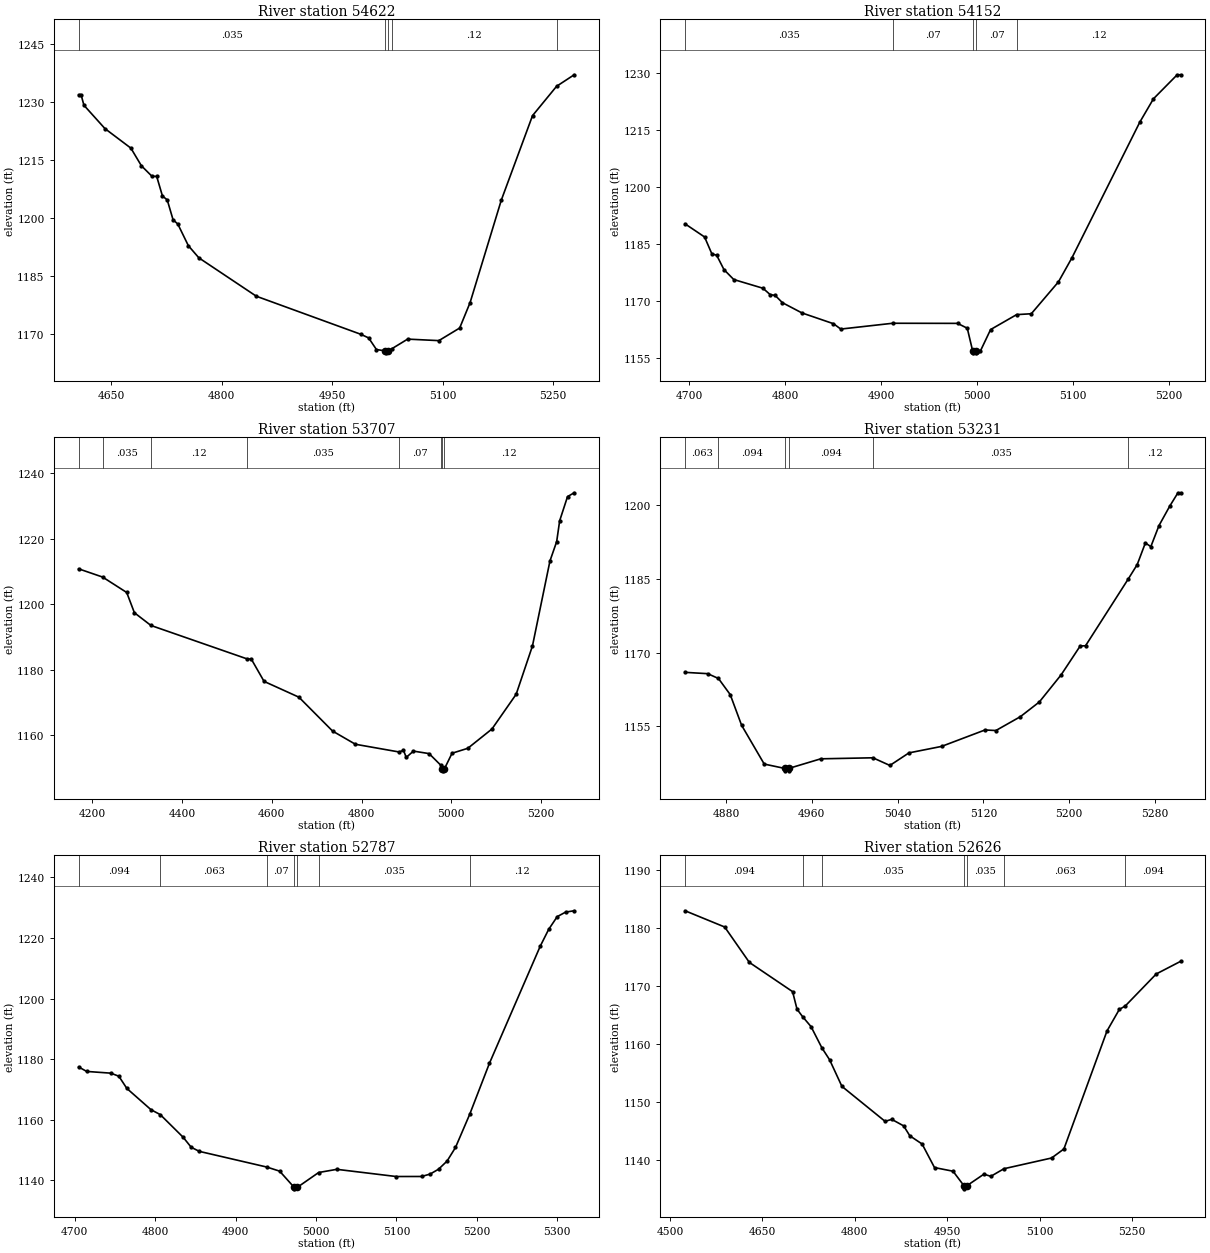
Type RM Length L Ch R = 1 ,54622   ,470,470,470
BEGIN DESCRIPTION:
Tom Creek 96.0
END DESCRIPTION:
XS GIS Cut Line= 3
      2179924.97     13848625.02        2180225.       13848375.
        2180425.       13848175.
#Sta/Elev= 30
  4605.4 1231.83  4608.7 1231.83  4612.6 1229.11  4641.2 1223.08  4676.4 1218.05
  4690.7  1213.5    4705  1210.8  4711.5 1210.75  4719.3  1205.7  4725.8  1204.7
  4733.7 1199.59  4740.2 1198.46  4754.5 1192.89  4768.8 1189.75  4846.9 1179.85
  4988.8 1170.04  4999.5  1169.1  5010.1  1166.1  5022.2 1165.75  5022.5 1165.25
  5026.2 1165.75  5031.4 1166.35  5052.5 1168.79  5094.9  1168.4  5123.2 1171.65
  5137.4 1178.23  5179.8 1204.65  5222.2 1226.43  5254.9    1234  5278.8 1236.97
#Mann= 5 ,-1 , 0
  4605.4    .035       0  5022.2    .035       0  5026.2    .035       0
  5031.4     .12       0  5254.9    .035       0
Bank Sta=5022.2,5026.2
XS Rating Curve= 0 ,0
Exp/Cntr=0.3,0.1

Type RM Length L Ch R = 1 ,54152   ,445,445,445
BEGIN DESCRIPTION:
Tom Creek 95.0
END DESCRIPTION:
XS GIS Cut Line= 3
      2180175.01       13848775.        2180475.       13848725.
      2180625.02     13848574.98
#Sta/Elev= 30
  4695.9 1190.21  4716.2 1186.76  4723.8 1182.31  4728.8 1181.96  4736.4 1178.18
  4746.6 1175.57    4777 1173.28  4784.6 1171.59  4789.7  1171.4  4797.3 1169.48
  4817.6 1166.79  4850.5 1163.95  4858.1 1162.54  4912.2 1164.07  4979.8 1164.04
  4989.9 1162.76  4995.5 1156.79  4995.7 1156.29  4999.2 1156.29  4999.5 1156.79
  5003.6 1156.79  5014.2 1162.41  5041.3 1166.34  5056.6 1166.57  5084.9 1174.96
    5099 1181.31  5169.7 1216.98  5183.9 1223.11  5208.6 1229.42  5212.2 1229.42
#Mann= 5 ,-1 , 0
  4695.9    .035       0  4912.2     .07       0  4995.5     .05       0
  4999.5     .07       0  5041.3     .12       0
Bank Sta=4995.5,4999.5
XS Rating Curve= 0 ,0
Exp/Cntr=0.3,0.1

Type RM Length L Ch R = 1 ,53707   ,476,476,476
BEGIN DESCRIPTION:
Tom Creek 94.0
END DESCRIPTION:
XS GIS Cut Line= 3
      2180464.09     13849727.35        2180825.       13848975.
        2180925.       13848725.
#Sta/Elev= 30
  4169.9 1210.86  4223.3 1208.35    4277 1203.64  4294.1 1197.46  4330.9 1193.58
    4546 1183.33  4554.3 1183.36  4582.9 1176.51  4660.5 1171.69  4735.5 1161.35
  4786.4 1157.32  4883.5 1154.97  4893.4 1155.46  4899.6 1153.32  4915.6 1155.23
  4950.5 1154.47  4976.3 1150.95  4980.2 1149.71  4980.4 1149.21  4984.2 1149.71
  5001.6 1154.58  5036.7 1156.09  5090.5 1161.98  5144.4 1172.58  5180.7 1187.33
  5219.7 1213.28  5234.6 1219.15  5241.3 1225.54  5258.8  1232.9  5273.6 1234.07
#Mann= 8 ,-1 , 0
  4169.9    .063       0  4223.3    .035       0  4330.9     .12       0
    4546    .035       0  4883.5     .07       0  4976.3     .12       0
  4980.2     .05       0  4984.2     .12       0
Bank Sta=4980.2,4984.2
XS Rating Curve= 0 ,0
Exp/Cntr=0.3,0.1

Type RM Length L Ch R = 1 ,53231   ,444,444,444
BEGIN DESCRIPTION:
Tom Creek 93.0
END DESCRIPTION:
XS GIS Cut Line= 3
      2181125.01     13849374.98        2181175.       13849225.
      2181224.99     13848925.03
#Sta/Elev= 30
  4841.8 1165.96  4862.9 1165.69  4872.9 1164.71  4883.9 1161.42  4894.5 1155.17
  4915.6 1147.26  4934.6 1146.38  4934.9 1145.88  4938.4 1145.88  4938.6 1146.38
  4968.3 1148.33    5017 1148.54  5032.8 1146.98  5050.6 1149.54    5081 1150.86
  5121.5 1154.21  5131.7  1154.1  5154.5 1156.92  5172.2 1159.92  5192.5 1165.44
  5210.3 1171.33  5215.3 1171.38  5255.3 1185.05  5263.5 1187.93  5271.1 1192.34
  5276.2 1191.59  5283.8 1195.88  5293.9 1199.87  5301.5 1202.57    5304 1202.57
#Mann= 6 ,-1 , 0
  4841.8    .063       0  4872.9    .094       0  4934.6     .05       0
  4938.6    .094       0    5017    .035       0  5255.3     .12       0
Bank Sta=4934.6,4938.6
XS Rating Curve= 0 ,0
Exp/Cntr=0.3,0.1

Type RM Length L Ch R = 1 ,52787   ,161,161,161
BEGIN DESCRIPTION:
Tom Creek 92.0
END DESCRIPTION:
XS GIS Cut Line= 3
      2181124.96       13849575.        2181425.       13849575.
      2181725.03     13849474.99
#Sta/Elev= 30
  4704.7 1177.44  4714.7 1175.96  4744.7 1175.39  4754.7 1174.38  4764.7 1170.34
  4794.7 1163.32  4806.2 1161.71  4834.7 1154.22  4844.7 1150.92  4854.7 1149.57
  4938.8 1144.38  4954.7 1143.03  4972.7 1137.69    4973 1137.19  4976.7 1137.69
  5003.2 1142.58  5025.8 1143.63  5099.6 1141.26  5131.2 1141.27  5141.8 1142.06
  5152.3 1143.67  5162.9 1146.35  5173.4 1150.85    5191 1161.75  5215.6 1178.64
  5278.8 1217.32  5289.3 1222.87  5299.9 1227.07  5310.4 1228.58    5321 1229.01
#Mann= 7 ,-1 , 0
  4704.7    .094       0  4806.2    .063       0  4938.8     .07       0
  4972.7     .05       0  4976.7     .07       0  5003.2    .035       0
    5191     .12       0
Bank Sta=4972.7,4976.7
XS Rating Curve= 0 ,0
Exp/Cntr=0.3,0.1

Type RM Length L Ch R = 1 ,52626   ,110,110,110
BEGIN DESCRIPTION:
Tom Creek 91.2
END DESCRIPTION:
XS GIS Cut Line= 3
      2181000.84     13849687.51      2181475.44     13849719.82
      2181804.62     13849723.31
#Sta/Elev= 30
  4524.3 1182.93  4588.6 1180.13  4628.7 1174.02  4698.9 1168.98  4706.1 1165.95
  4715.1 1164.67  4728.9 1162.94  4746.5 1159.28    4759 1157.23    4779 1152.64
  4849.2  1146.6  4859.9 1146.95  4879.3 1145.82  4889.3 1144.11  4909.3 1142.69
  4929.4 1138.63  4959.5    1138  4977.5 1135.46  4977.8 1134.96  4981.5 1135.46
  5009.6 1137.49  5020.9 1137.12  5042.2 1138.43  5119.6 1140.28  5139.6 1141.84
  5209.6  1162.2  5229.6 1165.91  5239.2  1166.5  5289.6 1172.03  5329.2 1174.21
#Mann= 7 ,-1 , 0
  4524.3    .094       0  4715.1    .063       0  4746.5    .035       0
  4977.5    .035       0  4981.5    .035       0  5042.2    .063       0
  5239.2    .094       0
Bank Sta=4977.5,4981.5
XS Rating Curve= 0 ,0
Exp/Cntr=0.3,0.1

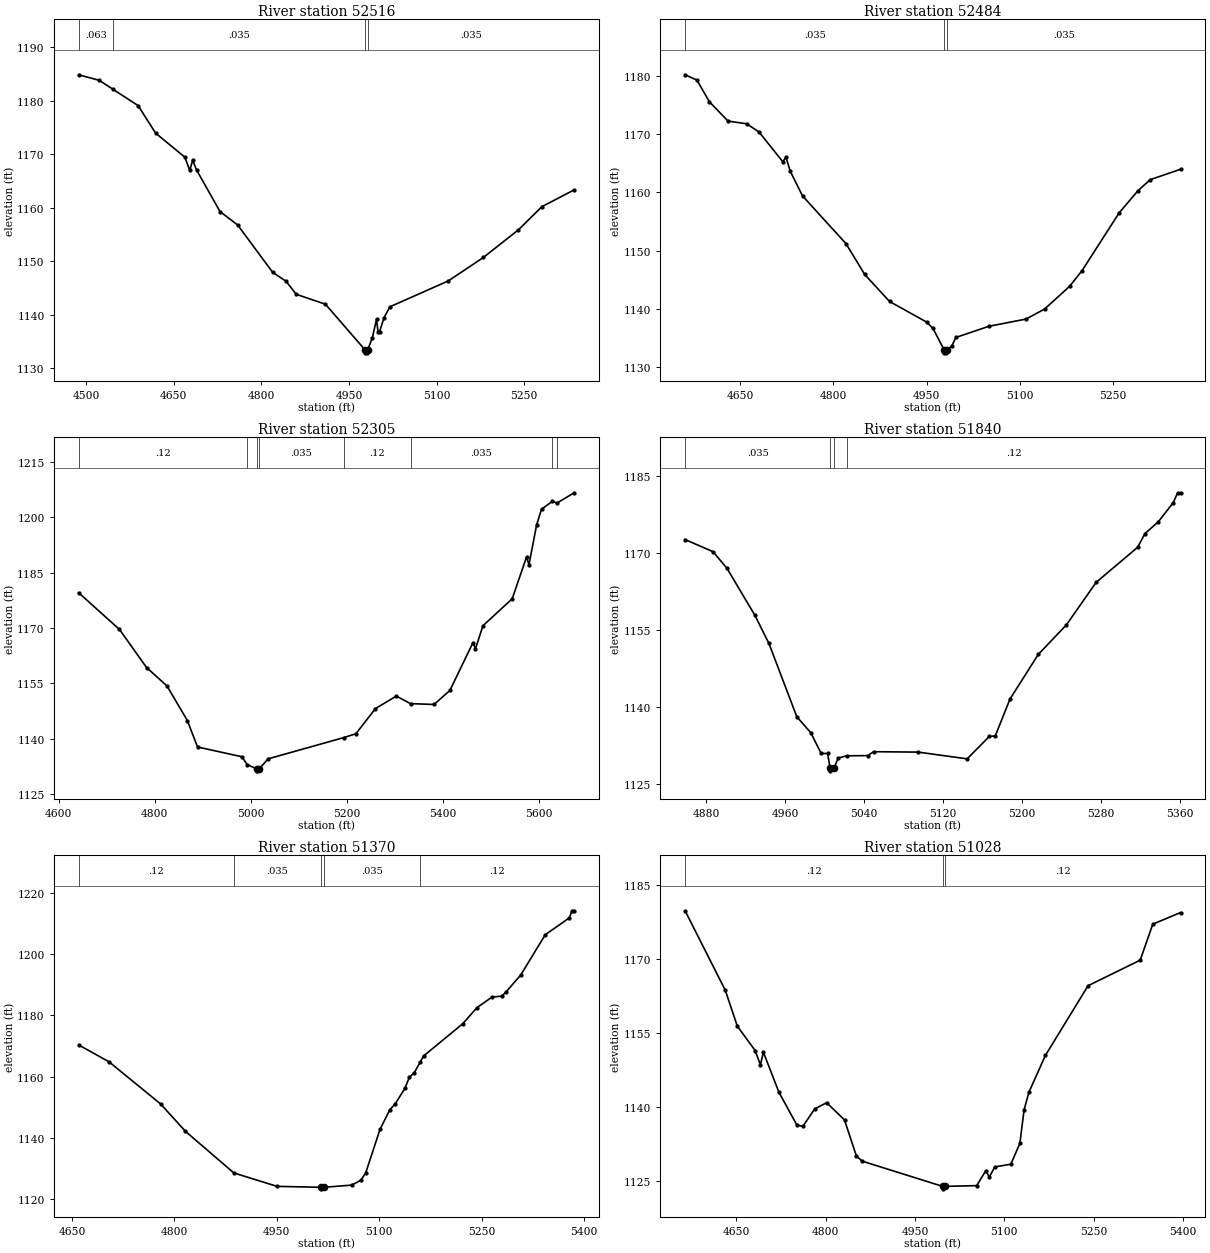
Type RM Length L Ch R = 1 ,52516   ,211,211,211
BEGIN DESCRIPTION:
Tom Creek 91.1
END DESCRIPTION:
XS GIS Cut Line= 3
      2180963.52     13849797.86      2181474.91     13849830.04
      2181810.29     13849833.84
#Sta/Elev= 30
  4487.6 1184.89  4522.9 1183.85  4546.7 1182.15  4589.3 1179.13  4619.3 1173.98
  4669.4 1169.47  4677.7    1167  4682.7  1168.9  4689.5 1167.06  4729.6 1159.29
  4759.6 1156.81  4819.7 1147.93  4842.5 1146.28  4859.8 1143.84  4909.9 1141.98
    4978 1133.39  4978.3 1132.89  4981.8 1132.89    4982 1133.39  4990.1 1135.72
  4997.3 1139.17  4999.7 1136.87  5002.5 1136.87  5010.1 1139.46  5020.1  1141.5
  5120.1 1146.34  5180.1 1150.73  5240.1  1155.9  5280.1 1160.22  5335.4 1163.37
#Mann= 4 ,-1 , 0
  4487.6    .063       0  4546.7    .035       0    4978    .035       0
    4982    .035       0
Bank Sta=4978,4982
XS Rating Curve= 0 ,0
Exp/Cntr=0.3,0.1

Type RM Length L Ch R = 1 ,52484   ,179,179,179
BEGIN DESCRIPTION:
Tom Creek 91.1
END DESCRIPTION:
XS GIS Cut Line= 3
      2181035.86     13849874.58      2181474.07     13849862.08
       2181833.9     13849870.03
#Sta/Elev= 30
    4561 1180.13  4580.1 1179.21  4600.2 1175.49  4630.2 1172.19  4660.2 1171.73
  4680.2 1170.31  4718.5 1165.21  4723.5 1166.03  4730.2 1163.64  4750.2 1159.36
  4820.2 1151.18  4850.3  1145.9  4890.3 1141.27  4950.3 1137.72  4960.3 1136.65
  4978.3 1132.96  4978.6 1132.46  4982.1 1132.46  4982.3 1132.96  4990.3 1133.58
  4997.3  1135.1  5050.3 1137.01  5110.3 1138.25  5140.3 1139.98  5180.4 1143.86
  5200.4 1146.54  5260.4 1156.48  5290.4 1160.24  5310.4 1162.15  5359.3 1163.94
#Mann= 3 ,-1 , 0
    4561    .035       0  4978.3    .035       0  4982.3    .035       0
Bank Sta=4978.3,4982.3
XS Rating Curve= 0 ,0
Exp/Cntr=0.3,0.1

Type RM Length L Ch R = 1 ,52305   ,465,465,465
BEGIN DESCRIPTION:
Tom Creek 91.0
END DESCRIPTION:
XS GIS Cut Line= 3
      2181274.97     13850275.03        2181525.       13850025.
      2182191.93     13849902.96
#Sta/Elev= 30
  4641.7 1179.59  4726.6 1169.65  4783.2 1159.29  4825.6 1154.31    4868 1144.93
  4889.2 1137.75  4981.2 1135.11    4993 1132.93  5013.6 1131.78  5013.9 1131.28
  5017.6 1131.78    5036 1134.53  5193.5 1140.29    5219 1141.35  5259.6 1148.17
  5303.1 1151.56  5332.6 1149.51  5381.6 1149.28  5414.6 1153.09  5462.7 1166.07
  5467.8 1164.36  5483.3 1170.63  5544.3 1177.95  5574.1 1189.28  5579.2  1187.2
  5595.1 1197.96  5605.3 1202.24    5628 1204.39  5637.3  1203.9  5673.3  1206.7
#Mann= 8 ,-1 , 0
  4641.7     .12       0    4993    .035       0  5013.6    .035       0
  5017.6    .035       0  5193.5     .12       0  5332.6    .035       0
    5628     .12       0  5637.3    .035       0
Bank Sta=5013.6,5017.6
XS Rating Curve= 0 ,0
Exp/Cntr=0.3,0.1

Type RM Length L Ch R = 1 ,51840   ,470,470,470
BEGIN DESCRIPTION:
Tom Creek 90.0
END DESCRIPTION:
XS GIS Cut Line= 3
      2181624.99     13850525.01        2181725.       13850425.
      2182025.01       13850225.
#Sta/Elev= 30
  4858.8 1172.58  4887.1 1170.22  4901.2    1167  4929.5 1157.86  4943.7  1152.4
    4972 1138.13  4986.1 1135.05  4996.7    1131  5003.2    1131  5005.7 1128.13
    5006 1127.63  5009.7 1128.13  5013.8  1130.1  5022.4 1130.55  5043.8 1130.59
  5049.8 1131.35  5094.9 1131.27  5144.5 1129.96    5167 1134.31    5173 1134.42
    5188 1141.61  5216.6 1150.26  5245.1    1156  5275.2 1164.26  5317.2 1171.07
  5324.7 1173.74  5338.3 1176.06  5353.3 1179.76  5357.8 1181.67  5360.8 1181.67
#Mann= 4 ,-1 , 0
  4858.8    .035       0  5005.7    .035       0  5009.7    .035       0
  5022.4     .12       0
Bank Sta=5005.7,5009.7
XS Rating Curve= 0 ,0
Exp/Cntr=0.3,0.1

Type RM Length L Ch R = 1 ,51370   ,342,342,342
BEGIN DESCRIPTION:
Tom Creek 89.0
END DESCRIPTION:
XS GIS Cut Line= 3
      2181774.99       13850875.        2182075.       13850725.
      2182324.98     13850425.03
#Sta/Elev= 30
  4659.7 1170.33  4704.4 1164.77  4779.9    1151  4816.2 1142.07  4887.1 1128.47
  4950.4 1124.09  5014.6 1123.78  5014.8 1123.28  5018.6 1123.78  5059.6  1124.5
  5073.2 1126.07  5080.4 1128.61  5101.2 1142.73  5115.5 1149.11  5123.3 1151.01
  5137.7 1156.15  5144.2 1159.79  5151.3 1161.19  5160.3 1164.81    5165  1166.7
  5222.3 1177.23  5243.1 1182.49  5265.2 1185.96  5279.5 1186.28  5286.1 1187.71
  5307.5 1193.24  5343.3 1206.36  5378.5 1211.84  5382.4 1214.17  5385.6 1214.17
#Mann= 5 ,-1 , 0
  4659.7     .12       0  4887.1    .035       0  5014.6    .035       0
  5018.6    .035       0  5160.3     .12       0
Bank Sta=5014.6,5018.6
XS Rating Curve= 0 ,0
Exp/Cntr=0.3,0.1

Type RM Length L Ch R = 1 ,51028   ,35,35,35
BEGIN DESCRIPTION:
Tom Creek 88.5
END DESCRIPTION:
XS GIS Cut Line= 3
       2181747.4     13850995.02      2182183.28     13850978.22
      2182515.39     13850761.99
#Sta/Elev= 30
  4563.8 1179.74  4631.4 1163.64  4651.5  1156.4  4681.5 1151.46  4690.3 1148.54
  4695.3 1151.13  4721.5 1143.01  4751.5  1136.4  4761.5 1136.11  4781.6 1139.66
  4801.6  1140.9  4831.6 1137.43  4851.6 1130.11  4861.6 1129.07  4996.4 1123.98
  4996.6 1123.48  5000.4 1123.98  5053.7 1124.13  5068.9 1127.14  5074.8 1125.85
    5084 1127.91  5111.1 1128.47  5126.2 1132.68  5133.3 1139.46  5141.3 1142.99
  5169.1 1150.47  5240.8 1164.58  5328.4 1169.75  5349.5 1177.03  5396.3 1179.39
#Mann= 3 ,-1 , 0
  4563.8     .12       0  4996.4     .05       0  5000.4     .12       0
Bank Sta=4996.4,5000.4
XS Rating Curve= 0 ,0
Exp/Cntr=0.3,0.1

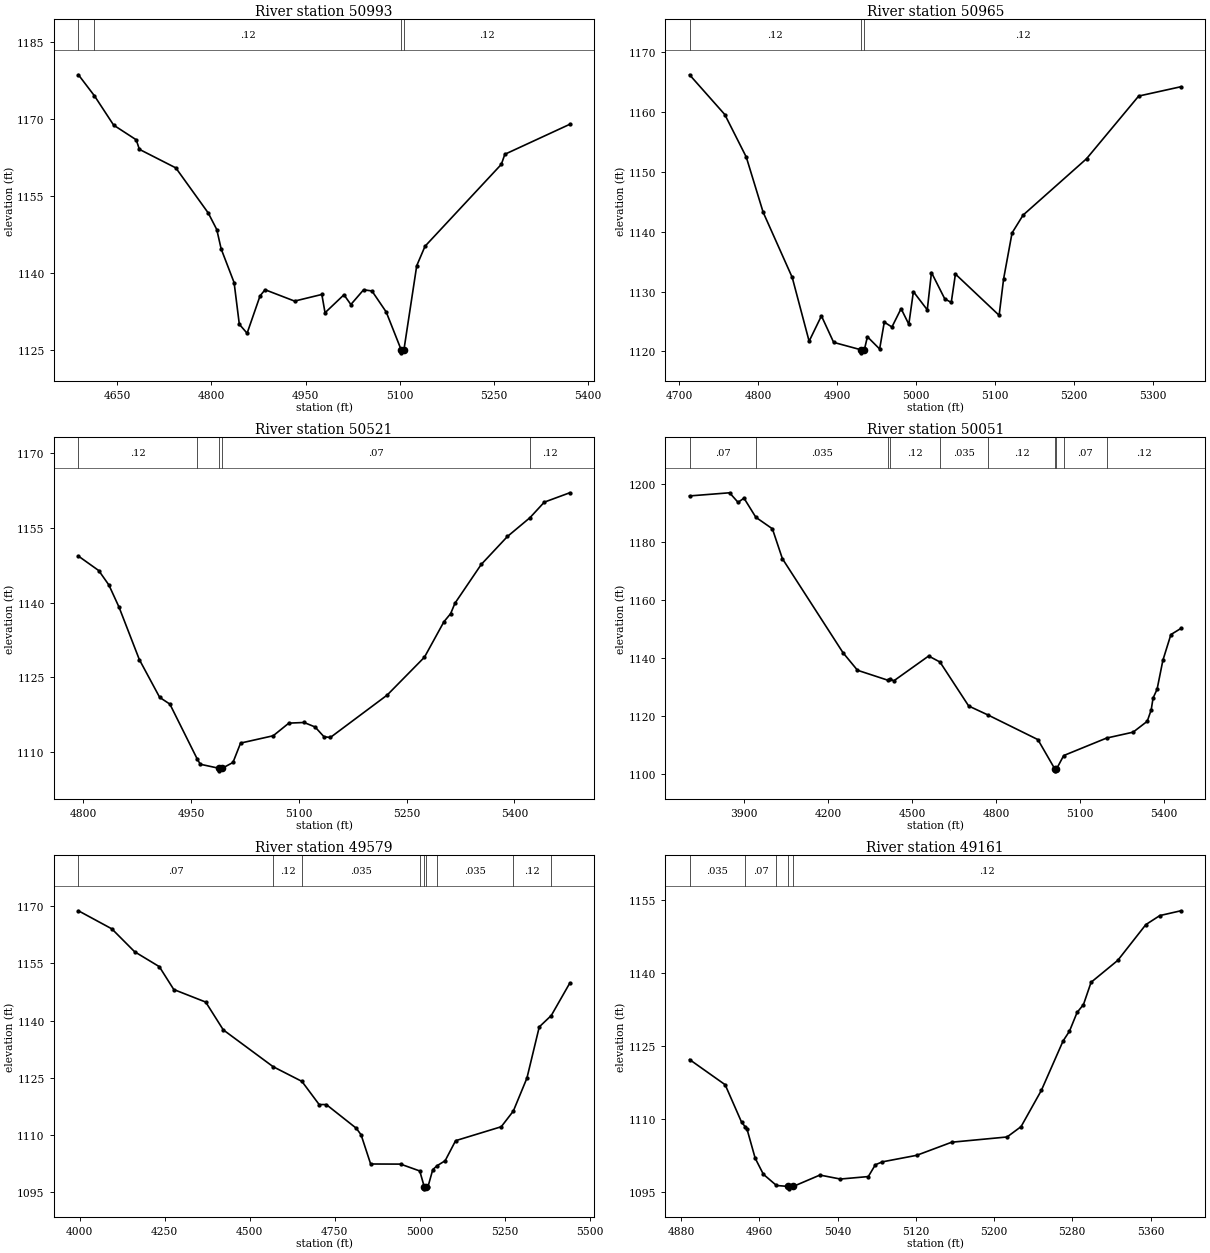
Type RM Length L Ch R = 1 ,50993   ,28,28,28
BEGIN DESCRIPTION:
Tom Creek 88.25
END DESCRIPTION:
XS GIS Cut Line= 5
       2181804.6     13851103.47      2182121.25     13851023.52
       2182204.5     13851004.84       2182279.6       13850983.
      2182541.69     13850853.84
#Sta/Elev= 30
  4588.1 1178.59  4613.7 1174.48  4644.2 1168.79  4680.1 1165.94  4685.2 1164.08
  4743.2 1160.47  4794.8  1151.7  4808.4 1148.47  4815.4  1144.7    4836 1138.15
  4844.3 1130.04  4856.7 1128.29  4877.3 1135.56  4885.3 1136.76  4932.3 1134.55
  4975.7 1135.84  4980.8 1132.28  5010.9 1135.78  5021.9 1133.88  5042.2 1136.75
  5055.5 1136.52  5078.2 1132.43  5102.3 1124.98  5102.5 1124.48  5106.3 1124.98
  5126.8 1141.44    5140 1145.22  5261.5 1161.16  5267.1 1163.12  5370.4 1168.95
#Mann= 4 ,-1 , 0
  4588.1    .035       0  4613.7     .12       0  5102.3     .05       0
  5106.3     .12       0
Bank Sta=5102.3,5106.3
XS Rating Curve= 0 ,0
Exp/Cntr=0.3,0.1

Type RM Length L Ch R = 1 ,50965   ,444,444,444
BEGIN DESCRIPTION:
Tom Creek 88.0
END DESCRIPTION:
XS GIS Cut Line= 3
      2181974.99     13851175.01        2182225.       13851025.
      2182535.64     13850909.72
#Sta/Elev= 30
  4712.8 1166.24  4757.5 1159.59  4784.7 1152.49  4806.1 1143.26    4843 1132.35
  4864.4 1121.69    4880 1125.93  4895.5  1121.5  4930.4 1120.25  4930.7 1119.75
  4934.4 1120.25  4938.3 1122.44  4953.8 1120.39  4959.7 1124.88  4969.4 1124.07
    4981 1127.14  4990.8 1124.53  4996.6 1129.98  5014.2 1126.94  5019.5 1133.18
  5036.4 1128.77  5044.6 1128.18  5049.9 1132.92  5105.3 1126.02    5111 1132.13
  5121.7  1139.8  5135.7 1142.78  5216.1  1152.2  5282.2 1162.68  5335.7 1164.24
#Mann= 3 ,-1 , 0
  4712.8     .12       0  4930.4     .05       0  4934.4     .12       0
Bank Sta=4930.4,4934.4
XS Rating Curve= 0 ,0
Exp/Cntr=0.3,0.1

Type RM Length L Ch R = 1 ,50521   ,470,470,470
BEGIN DESCRIPTION:
Tom Creek 87.0
END DESCRIPTION:
XS GIS Cut Line= 3
      2182225.01     13851524.99        2182375.       13851375.
      2182624.99     13850975.01
#Sta/Elev= 30
  4793.3 1149.32  4821.6 1146.42  4835.7 1143.53  4849.8  1139.1  4878.1 1128.58
  4906.4 1121.01  4920.6 1119.66  4958.9 1108.59    4963 1107.61  4989.3 1106.79
  4989.5 1106.29  4993.3 1106.79  5008.4 1107.97    5019 1111.85  5064.4 1113.32
  5086.2 1115.85  5107.4 1115.98  5122.7 1115.08  5135.1 1113.12    5144 1112.98
    5223 1121.47  5274.9 1129.06    5302 1136.16  5311.4  1137.8  5317.3 1139.86
  5353.9 1147.64  5390.4 1153.25  5421.7 1157.01  5441.7 1160.13  5477.1 1162.01
#Mann= 5 ,-1 , 0
  4793.3     .12       0  4958.9     .07       0  4989.3     .05       0
  4993.3     .07       0  5421.7     .12       0
Bank Sta=4989.3,4993.3
XS Rating Curve= 0 ,0
Exp/Cntr=0.3,0.1

Type RM Length L Ch R = 1 ,50051   ,472,472,472
BEGIN DESCRIPTION:
Tom Creek 86.0
END DESCRIPTION:
XS GIS Cut Line= 3
      2181635.95      13852374.9        2182725.       13851675.
      2183024.97     13851325.03
#Sta/Elev= 30
  3705.2    1196  3848.2 1197.09  3878.6 1193.78  3899.7 1195.24  3942.1 1188.62
  4001.2 1184.65  4036.9 1174.33  4253.7 1141.81  4305.3 1135.77  4413.2 1132.35
  4419.9 1132.76  4435.4 1132.14  4559.5 1140.69    4600 1138.62  4702.6 1123.42
    4772  1120.3  4949.9 1111.81  5011.3 1101.52  5011.6 1101.02  5015.6 1101.52
  5042.1  1106.3  5195.2 1112.34  5290.1 1114.38  5340.6 1118.14  5354.8  1122.1
  5361.4 1126.17  5375.7 1129.17  5396.5 1139.21  5425.1  1148.1  5460.7 1150.21
#Mann= 10 ,-1 , 0
  3705.2     .07       0  3942.1    .035       0  4413.2     .07       0
  4419.9     .12       0    4600    .035       0    4772     .12       0
  5011.3     .05       0  5015.6     .12       0  5042.1     .07       0
  5195.2     .12       0
Bank Sta=5011.3,5015.6
XS Rating Curve= 0 ,0
Exp/Cntr=0.3,0.1

Type RM Length L Ch R = 1 ,49579   ,418,418,418
BEGIN DESCRIPTION:
Tom Creek 85.0
END DESCRIPTION:
XS GIS Cut Line= 3
      2182538.77     13852765.49        2183075.       13851925.
      2183475.01       13851725.
#Sta/Elev= 30
  3996.6  1168.8  4094.9 1164.06  4161.8 1158.07  4234.4 1154.16  4276.9 1148.17
  4370.8 1144.88  4422.4  1137.6  4568.8 1127.96  4653.6  1124.1  4704.2 1118.04
  4725.3 1118.03  4813.3 1111.83  4827.5 1110.11  4855.6 1102.46  4943.6 1102.43
    5000 1100.63  5013.3 1096.45  5013.7 1095.95  5018.6 1096.45  5024.3 1096.56
  5038.3    1101  5051.3 1102.03  5074.6 1103.31  5105.4 1108.57  5239.5 1112.22
    5275 1116.32    5315 1124.96  5351.3 1138.38  5386.6 1141.36  5440.8 1149.82
#Mann= 9 ,-1 , 0
  3996.6     .07       0  4568.8     .12       0  4653.6    .035       0
    5000     .12       0  5013.3    .035       0  5018.6     .12       0
  5051.3    .035       0    5275     .12       0  5386.6     .07       0
Bank Sta=5013.3,5018.6
XS Rating Curve= 0 ,0
Exp/Cntr=0.3,0.1

Type RM Length L Ch R = 1 ,49161   ,444,444,444
BEGIN DESCRIPTION:
Tom Creek 84.0
END DESCRIPTION:
XS GIS Cut Line= 3
      2183274.98     13852275.04        2183325.       13852175.
      2183575.02     13851874.97
#Sta/Elev= 30
  4888.6 1122.22    4925 1117.03  4941.8 1109.31  4945.7 1108.32  4947.3 1107.92
  4955.7 1101.89  4964.1 1098.57  4977.5 1096.26  4989.4 1096.07  4989.8 1095.57
  4994.7 1096.07  5021.9 1098.41  5042.8 1097.59  5071.4  1098.1  5078.6 1100.53
  5085.7 1101.13  5120.9 1102.48  5156.7 1105.18  5213.3 1106.26  5227.6 1108.39
  5248.4 1115.88  5270.6 1126.06  5277.1 1128.06  5284.9 1131.93  5291.4 1133.54
  5299.2 1138.14  5326.5 1142.66  5355.2 1150.03  5369.5 1151.89    5391 1152.88
#Mann= 5 ,-1 , 0
  4888.6    .035       0  4945.7     .07       0  4977.5     .12       0
  4989.4     .05       0  4994.7     .12       0
Bank Sta=4989.4,4994.7
XS Rating Curve= 0 ,0
Exp/Cntr=0.3,0.1

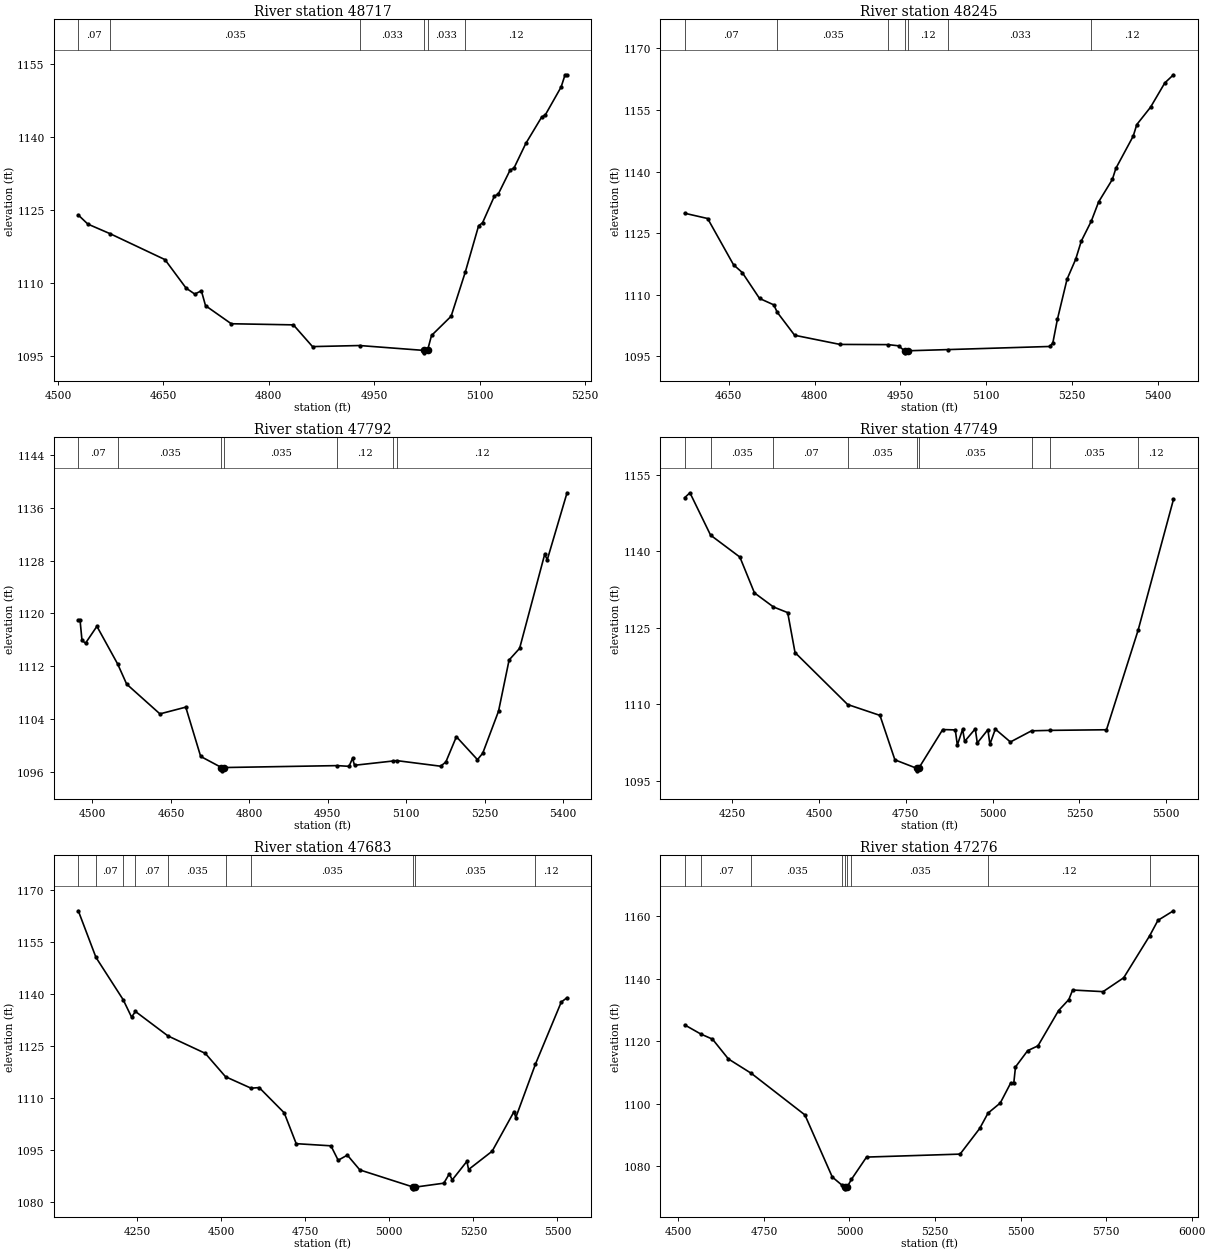
Type RM Length L Ch R = 1 ,48717   ,472,472,472
BEGIN DESCRIPTION:
Tom Creek 83.0
END DESCRIPTION:
XS GIS Cut Line= 3
      2183324.98     13852475.01        2183725.       13852225.
      2183824.99     13852025.02
#Sta/Elev= 30
  4528.9 1124.02  4542.5 1122.16  4574.6 1120.16  4652.2 1114.87  4682.2 1109.03
  4694.6  1107.8    4704 1108.47  4709.9 1105.42  4746.5 1101.71  4834.9 1101.48
  4862.1 1097.02  4929.1 1097.24  5020.3 1096.24  5020.7 1095.74  5025.7 1096.24
  5031.4  1099.3  5059.3 1103.25  5079.4 1112.29  5098.4 1121.82    5104 1122.43
  5120.8 1127.88  5126.4 1128.33  5143.2 1133.24  5148.8 1133.68  5165.5  1138.7
  5187.9 1144.07  5193.5 1144.62  5215.8  1150.3  5221.4  1152.8  5224.2  1152.8
#Mann= 6 ,-1 , 0
  4528.9     .07       0  4574.6    .035       0  4929.1    .033       0
  5020.3    .033       0  5025.7    .033       0  5079.4     .12       0
Bank Sta=5020.3,5025.7
XS Rating Curve= 0 ,0
Exp/Cntr=0.3,0.1

Type RM Length L Ch R = 1 ,48245   ,453,453,453
BEGIN DESCRIPTION:
Tom Creek 82.0
END DESCRIPTION:
XS GIS Cut Line= 3
        2183925.     13852875.01        2184075.       13852475.
        2184225.     13852075.01
#Sta/Elev= 30
  4572.8 1129.87  4612.9 1128.59  4658.2 1117.32  4673.4 1115.44  4703.6 1109.13
  4728.6 1107.56  4734.5 1105.77    4765 1100.16  4844.3 1097.93  4928.7 1097.88
  4946.6 1097.59  4957.1 1096.38  4957.6 1095.88  4962.8 1096.38  5032.6 1096.67
  5210.9 1097.43  5216.3 1098.26  5224.3 1104.01  5241.2 1113.81  5256.3 1118.67
  5266.1 1123.09  5283.6 1127.95  5296.4 1132.63  5320.4 1138.11  5326.6 1140.82
  5356.9 1148.66  5363.1 1151.46  5387.2  1155.7  5412.1 1161.61  5427.2 1163.59
#Mann= 7 ,-1 , 0
  4572.8     .07       0  4734.5    .035       0  4928.7     .12       0
  4957.1     .05       0  4962.8     .12       0  5032.6    .033       0
  5283.6     .12       0
Bank Sta=4957.1,4962.8
XS Rating Curve= 0 ,0
Exp/Cntr=0.3,0.1

Type RM Length L Ch R = 1 ,47792   ,43,43,43
BEGIN DESCRIPTION:
Tom Creek 81.0
END DESCRIPTION:
XS GIS Cut Line= 3
        2184125.       13853025.        2184475.       13852625.
        2184525.     13852225.02
#Sta/Elev= 30
  4472.9 1119.04  4476.2 1119.04    4480 1115.92  4486.7 1115.51  4508.5 1118.06
  4548.2 1112.36  4565.4 1109.32    4629 1104.82  4678.4 1105.84  4706.9 1098.39
  4746.7 1096.71  4747.2 1096.21  4752.4 1096.71  4968.2    1097  4990.6 1096.89
  4997.3  1098.1  5001.1 1097.05  5075.1  1097.7  5081.4 1097.76  5165.7 1096.91
  5175.7 1097.54  5195.9 1101.37  5236.2  1097.9  5246.3 1098.88  5276.5 1105.23
  5296.7 1112.97  5316.8 1114.73  5364.7 1128.93  5369.7 1128.13  5407.5 1138.25
#Mann= 7 ,-1 , 0
  4472.9     .07       0  4548.2    .035       0  4746.7     .05       0
  4752.4    .035       0  4968.2     .12       0  5075.1    .033       0
  5081.4     .12       0
Bank Sta=4746.7,4752.4
XS Rating Curve= 0 ,0
Exp/Cntr=0.3,0.1

Type RM Length L Ch R = 1 ,47749   ,66,66,66
BEGIN DESCRIPTION:
Tom Creek 80.6
END DESCRIPTION:
XS GIS Cut Line= 6
      2184010.22     13853390.56      2184441.88      13852753.1
      2184505.05     13852654.92      2184598.98     13852487.22
      2184625.38     13852391.99      2184630.65     13852162.29
#Sta/Elev= 30
  4113.4 1150.56  4128.5 1151.52  4187.9  1143.2  4272.3 1138.89  4314.3 1131.85
    4369 1129.09    4410 1127.98  4431.1 1120.14  4582.6 1109.93  4675.7 1107.79
  4718.7 1099.06  4781.5  1097.4  4781.9  1096.9  4787.2  1097.4  4856.4 1105.01
  4892.6 1104.94  4898.5 1101.96  4913.7 1105.07  4919.7 1102.69  4950.1 1105.15
    4956 1102.37  4986.4 1104.98  4992.3 1102.13  5007.9 1105.09  5051.3 1102.57
  5112.1 1104.76  5165.9 1104.85    5328 1104.97    5419 1124.51  5520.8  1150.2
#Mann= 9 ,-1 , 0
  4113.4     .07       0  4187.9    .035       0    4369     .07       0
  4582.6    .035       0  4781.5    .035       0  4787.2    .035       0
  5112.1     .12       0  5165.9    .035       0    5419     .12       0
Bank Sta=4781.5,4787.2
XS Rating Curve= 0 ,0
Exp/Cntr=0.3,0.1

Type RM Length L Ch R = 1 ,47683   ,407,407,407
BEGIN DESCRIPTION:
Tom Creek 80.5
END DESCRIPTION:
XS GIS Cut Line= 4
      2184099.09     13853474.87      2184564.96     13852675.75
      2184653.41     13852510.74      2184702.47     13852172.91
#Sta/Elev= 30
    4075 1164.07  4127.5 1150.64  4208.4 1138.45  4233.4 1133.43    4245 1135.04
  4341.8 1127.99  4452.6 1122.98  4512.9 1116.24  4588.8 1112.93    4613 1113.11
  4687.4 1105.83  4723.1 1096.94  4826.4 1096.32  4847.9 1092.16  4875.2 1093.64
  4912.4 1089.37  5071.5 1084.42  5071.9 1083.92  5077.3 1084.42  5162.1 1085.55
  5178.4 1088.23  5187.2  1086.5  5230.7 1091.84  5235.8 1089.49  5305.9 1094.77
    5371 1106.19  5376.1 1104.45  5434.7 1119.89  5511.4 1137.76  5528.6 1139.02
#Mann= 10 ,-1 , 0
    4075     .12       0  4127.5     .07       0  4208.4    .035       0
    4245     .07       0  4341.8    .035       0  4512.9     .07       0
  4588.8    .035       0  5071.5    .035       0  5077.3    .035       0
  5434.7     .12       0
Bank Sta=5071.5,5077.3
XS Rating Curve= 0 ,0
Exp/Cntr=0.3,0.1

Type RM Length L Ch R = 1 ,47276   ,381,381,381
BEGIN DESCRIPTION:
Tom Creek 80.0
END DESCRIPTION:
XS GIS Cut Line= 3
      2184856.47     13853156.17      2184869.62     13852674.85
      2184811.76     13851729.82
#Sta/Elev= 30
  4518.5 1125.19  4565.8 1122.26  4599.7 1120.64  4646.3  1114.3  4713.4 1109.69
  4869.8 1096.42  4949.8 1076.57  4977.2 1074.05  4986.9 1073.29  4987.4 1072.79
  4992.8 1073.29  5005.8 1075.82  5049.9 1082.94  5323.3 1083.89  5380.6 1092.09
    5405    1097  5440.7 1100.22  5470.7 1106.51  5480.2 1106.59  5485.2 1111.75
  5520.8 1116.96  5550.9  1118.5    5611 1129.76  5641.1  1133.3  5652.2 1136.34
  5741.2 1135.82  5801.4 1140.26  5877.1 1153.64  5901.5 1158.61  5946.8 1161.67
#Mann= 9 ,-1 , 0
  4518.5    .035       0  4565.8     .07       0  4713.4    .035       0
  4977.2     .07       0  4986.9     .05       0  4992.8     .07       0
  5005.8    .035       0    5405     .12       0  5877.1    .035       0
Bank Sta=4986.9,4992.8
XS Rating Curve= 0 ,0
Exp/Cntr=0.3,0.1

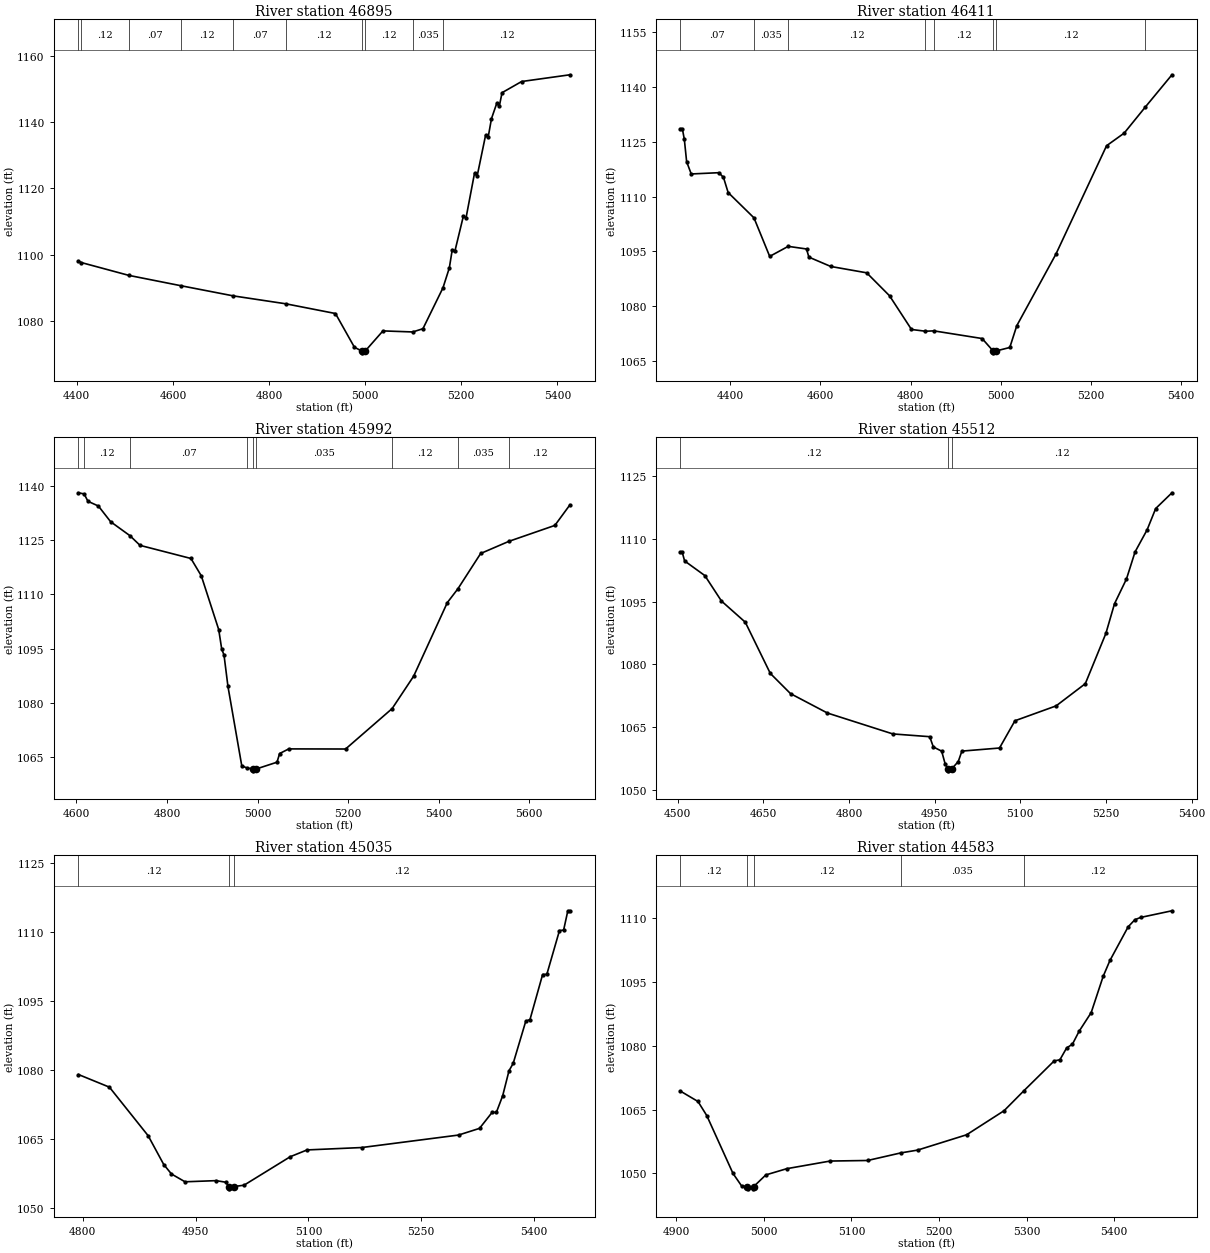
Type RM Length L Ch R = 1 ,46895   ,484,484,484
BEGIN DESCRIPTION:
Tom Creek 79.0
END DESCRIPTION:
XS GIS Cut Line= 3
      2185363.12      13852971.4        2185125.       13852425.
       2184949.6     13852036.28
#Sta/Elev= 30
  4403.5 1097.98  4409.8 1097.55  4508.4 1093.68  4617.1 1090.54  4725.9 1087.47
  4834.6 1085.09  4938.2 1082.14  4977.7 1071.92  4993.8 1070.74  4994.3 1070.24
  4999.8 1070.74    5037 1076.88  5098.9 1076.56  5120.2 1077.54  5161.9 1089.92
  5175.1 1095.94  5181.2 1101.48  5186.7 1101.02  5204.4 1111.67  5209.8 1111.04
  5227.5 1124.59    5233 1123.75  5250.6 1136.14  5256.1 1135.67  5262.8 1141.13
  5273.7 1145.72  5279.2 1144.98  5284.8 1148.97  5325.5 1152.35    5426 1154.39
#Mann= 10 ,-1 , 0
  4403.5    .035       0  4409.8     .12       0  4508.4     .07       0
  4617.1     .12       0  4725.9     .07       0  4834.6     .12       0
  4993.8     .05       0  4999.8     .12       0  5098.9    .035       0
  5161.9     .12       0
Bank Sta=4993.8,4999.8
XS Rating Curve= 0 ,0
Exp/Cntr=0.3,0.1

Type RM Length L Ch R = 1 ,46411   ,419,419,419
BEGIN DESCRIPTION:
Tom Creek 78.0
END DESCRIPTION:
XS GIS Cut Line= 3
      2185691.87     13853118.31      2185537.89     13852426.97
      2185458.75     13852053.03
#Sta/Elev= 30
  4289.6 1128.57  4293.8 1128.57  4298.2 1125.67  4303.3 1119.54  4313.5 1116.18
    4375 1116.53  4385.1 1115.22  4395.4 1111.09  4452.7 1104.16  4487.6  1093.6
  4528.7 1096.35  4569.3 1095.63  4574.5  1093.4  4623.1 1090.84  4702.8  1089.1
  4753.5 1082.81  4802.2 1073.58  4833.2  1073.1  4851.8  1073.2  4958.9  1071.1
  4983.4 1067.68  4983.9 1067.18  4989.4 1067.68  5020.3 1068.65  5035.8 1074.61
  5122.6 1094.21    5235 1123.91  5274.1 1127.37  5320.9  1134.5  5380.1 1143.35
#Mann= 8 ,-1 , 0
  4289.6     .07       0  4452.7    .035       0  4528.7     .12       0
  4833.2     .07       0  4851.8     .12       0  4983.4     .05       0
  4989.4     .12       0  5320.9    .035       0
Bank Sta=4983.4,4989.4
XS Rating Curve= 0 ,0
Exp/Cntr=0.3,0.1

Type RM Length L Ch R = 1 ,45992   ,480,480,480
BEGIN DESCRIPTION:
Tom Creek 77.0
END DESCRIPTION:
XS GIS Cut Line= 3
      2186004.77     13852908.17        2185925.       13852525.
      2185701.03     13851868.44
#Sta/Elev= 30
  4604.5 1138.14  4617.1 1137.82  4625.5 1135.79  4648.6 1134.47  4675.6 1130.13
  4718.2 1126.27  4740.5 1123.59  4852.9 1119.96  4875.8 1115.15  4914.2 1100.29
  4920.8 1094.91  4925.9 1093.25  4934.6 1084.56  4965.2 1062.53  4977.3 1061.99
  4990.1  1061.7  4990.6  1061.2  4996.6  1061.7  5042.9 1063.59  5048.7 1065.99
  5068.9 1067.27  5194.3 1067.24  5297.1 1078.43  5344.6  1087.4  5418.9 1107.75
  5442.3 1111.58  5492.5 1121.34    5555 1124.71  5656.3 1129.11  5689.6  1134.8
#Mann= 9 ,-1 , 0
  4604.5     .07       0  4617.1     .12       0  4718.2     .07       0
  4977.3    .035       0  4990.1    .035       0  4996.6    .035       0
  5297.1     .12       0  5442.3    .035       0    5555     .12       0
Bank Sta=4990.1,4996.6
XS Rating Curve= 0 ,0
Exp/Cntr=0.3,0.1

Type RM Length L Ch R = 1 ,45512   ,477,477,477
BEGIN DESCRIPTION:
Tom Creek 76.0
END DESCRIPTION:
XS GIS Cut Line= 3
      2186424.98     13852574.97        2186125.       13852175.
      2185825.02     13851975.01
#Sta/Elev= 30
  4504.9 1106.77    4508 1106.77  4512.2  1104.7  4547.6  1101.2  4576.7 1095.11
  4618.4 1090.05  4662.2  1077.8  4697.6 1072.96  4762.2 1068.32  4876.7 1063.32
  4941.3 1062.66  4947.6  1060.2  4962.2  1059.2  4968.4 1056.11  4973.4 1054.99
  4973.9 1054.49    4980 1054.99  4991.3 1056.72  4997.6 1059.21  5063.5 1059.95
  5090.5 1066.47  5162.6 1070.03  5213.7 1075.34  5249.7 1087.36  5264.8 1094.46
  5285.8  1100.4  5300.8 1106.87  5321.9 1112.15  5336.9 1117.24  5365.4 1121.01
#Mann= 3 ,-1 , 0
  4504.9     .12       0  4973.4     .05       0    4980     .12       0
Bank Sta=4973.4,4980
XS Rating Curve= 0 ,0
Exp/Cntr=0.3,0.1

Type RM Length L Ch R = 1 ,45035   ,452,452,452
BEGIN DESCRIPTION:
Tom Creek 75.0
END DESCRIPTION:
XS GIS Cut Line= 3
      2186574.99     13852324.97        2186525.       13852125.
      2186325.02     13851725.03
#Sta/Elev= 30
  4794.3 1079.08  4835.5 1076.33    4887 1065.78  4907.7 1059.53    4918 1057.47
    4936 1055.78  4977.2 1056.03  4990.1 1055.69  4994.5 1054.75    4995 1054.25
  5001.2 1054.75  5014.4 1055.04  5075.9 1061.23  5098.2  1062.7  5170.9 1063.22
  5299.5 1065.93  5327.4 1067.38  5344.2 1070.86  5349.8 1070.85  5358.2 1074.46
  5366.6 1079.89  5372.2 1081.51  5388.9 1090.66  5394.5 1091.02  5411.3  1100.8
  5416.9 1100.84  5433.7 1110.35  5439.2 1110.44  5444.8 1114.64  5447.6 1114.64
#Mann= 3 ,-1 , 0
  4794.3     .12       0  4994.5     .05       0  5001.2     .12       0
Bank Sta=4994.5,5001.2
XS Rating Curve= 0 ,0
Exp/Cntr=0.3,0.1

Type RM Length L Ch R = 1 ,44583   ,475,475,475
BEGIN DESCRIPTION:
Tom Creek 74.0
END DESCRIPTION:
XS GIS Cut Line= 3
        2186925.     13852074.98        2186925.       13851975.
      2186624.97     13851624.97
#Sta/Elev= 30
  4904.8 1069.31  4924.8 1066.88  4934.8 1063.59  4964.8 1049.99  4974.8 1047.01
  4981.3 1046.89  4981.8 1046.39  4987.7 1046.39  4988.2 1046.89  5002.3 1049.66
  5026.2 1051.12  5075.6 1052.91  5118.4 1053.04  5156.1 1054.81  5175.5 1055.48
  5231.4 1059.07  5274.2 1064.72  5296.6 1069.36  5331.3 1076.39  5337.9 1076.67
  5345.6 1079.45  5352.2 1080.32  5359.8 1083.35  5373.6 1087.73  5387.3 1096.25
    5395 1099.96  5415.8 1107.86  5423.5 1109.53  5430.1 1110.06  5465.8 1111.62
#Mann= 5 ,-1 , 0
  4904.8     .12       0  4981.3     .05       0  4988.2     .12       0
  5156.1    .035       0  5296.6     .12       0
Bank Sta=4981.3,4988.2
XS Rating Curve= 0 ,0
Exp/Cntr=0.3,0.1