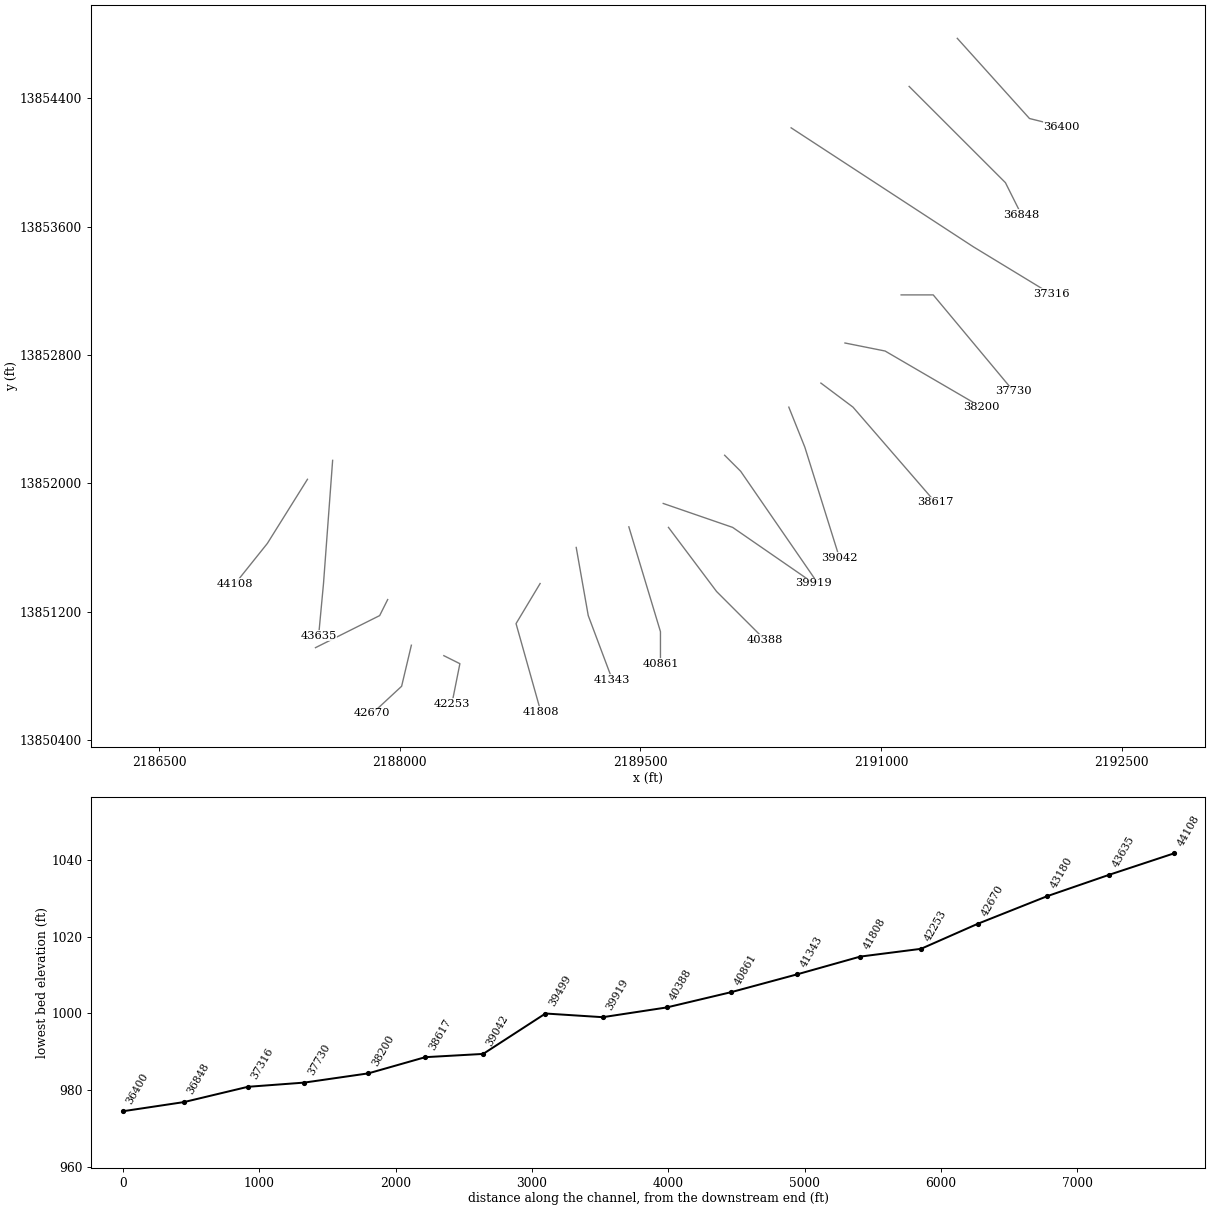
HEC-RAS study Tom Creek.prj: Tom Creek Base Level Engineering

--- Tom Creek.g01 (geometry) --- (continued)

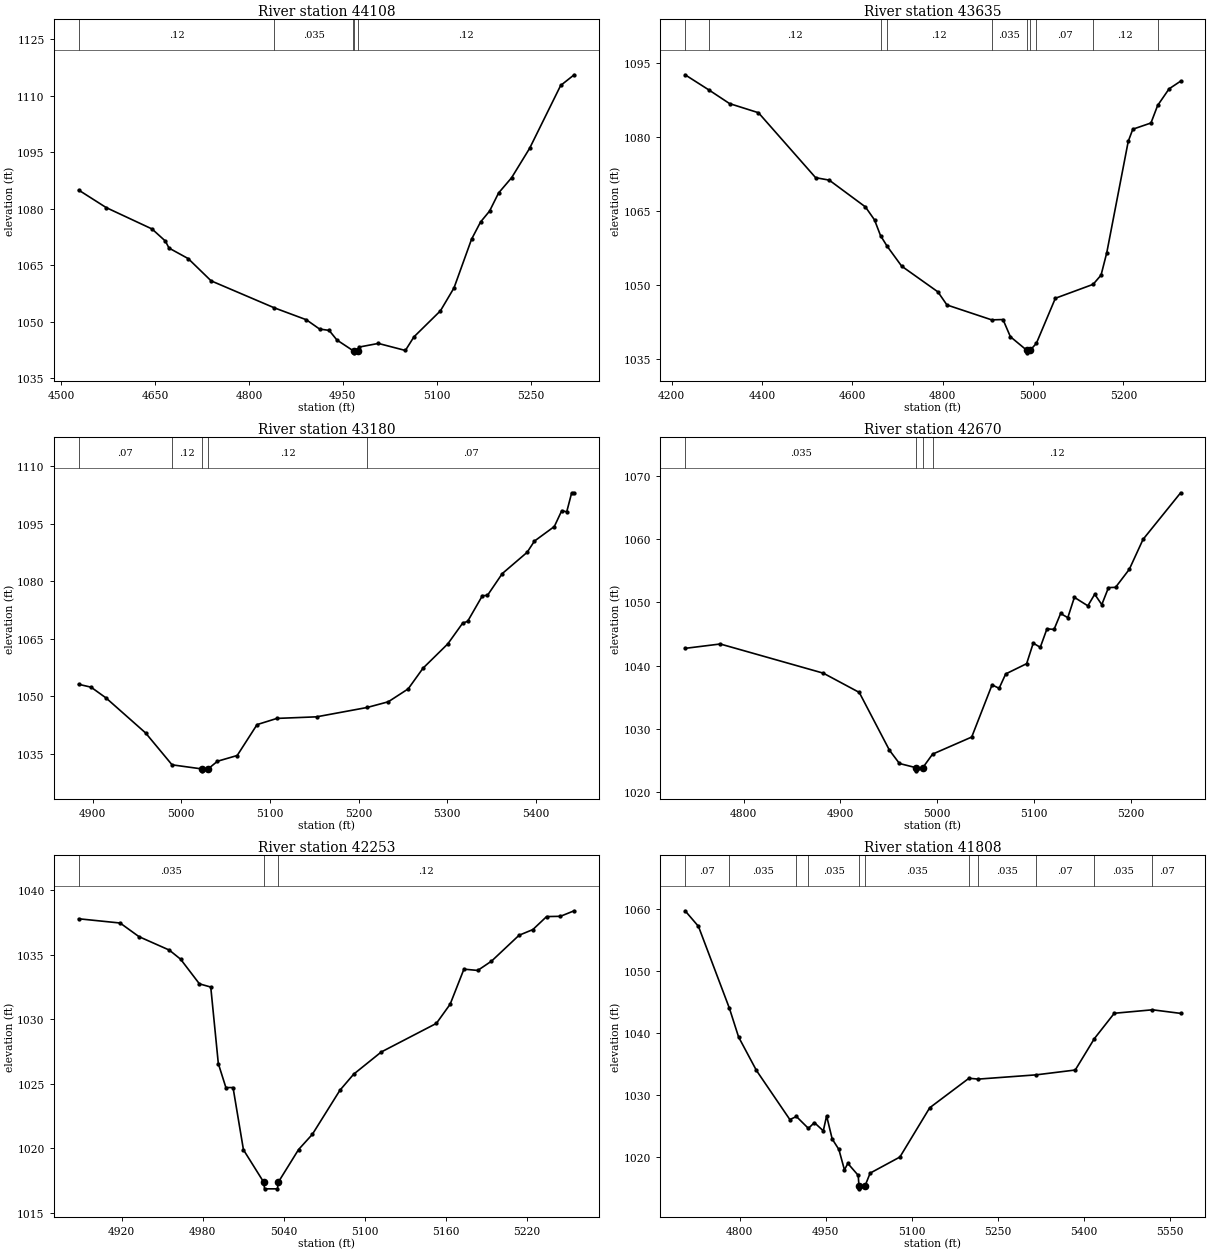
Type RM Length L Ch R = 1 ,44108   ,473,473,473
BEGIN DESCRIPTION:
Tom Creek 73.0
END DESCRIPTION:
XS GIS Cut Line= 3
      2187424.99     13852024.99        2187175.       13851625.
      2186975.03     13851375.03
#Sta/Elev= 30
  4527.8 1084.97    4572  1080.3  4645.1 1074.63  4666.4 1071.42  4672.2 1069.56
  4702.9 1066.76  4739.5 1060.85  4840.4 1053.69  4891.6 1050.52  4912.8 1048.05
  4928.1 1047.69  4940.5 1045.14  4966.8 1042.25  4967.1 1042.23  4967.6 1041.73
    4974 1042.23  4976.5 1043.28  5006.7 1044.23  5049.9 1042.36  5063.5 1045.96
  5105.9 1052.89  5127.6 1058.98  5155.6  1071.9    5170 1076.48  5184.4 1079.38
  5198.8 1084.19  5219.6 1088.24  5248.4 1096.05    5298 1112.75  5319.6 1115.59
#Mann= 5 ,-1 , 0
  4527.8     .12       0  4840.4    .035       0  4966.8     .12       0
  4967.1     .05       0    4974     .12       0
Bank Sta=4967.1,4974
XS Rating Curve= 0 ,0
Exp/Cntr=0.3,0.1

Type RM Length L Ch R = 1 ,43635   ,455,455,455
BEGIN DESCRIPTION:
Tom Creek 72.0
END DESCRIPTION:
XS GIS Cut Line= 3
      2187581.91     13852143.22        2187525.       13851375.
      2187494.56     13851049.54
#Sta/Elev= 30
  4229.6 1092.52  4282.9 1089.41  4328.1 1086.68    4392 1084.83  4518.6 1071.67
  4548.7 1071.17  4628.9 1065.74    4649 1063.11  4662.3 1059.93  4676.7 1057.81
  4709.1 1053.74  4789.3 1048.53  4809.4 1045.87  4908.5 1042.85  4933.5 1042.92
  4949.8 1039.44  4986.4 1036.67  4986.9 1036.17  4993.4 1036.67  5007.4  1038.1
  5049.4 1047.23    5133 1050.05  5150.6 1051.92  5163.3 1056.49  5210.8 1079.04
  5220.9 1081.49  5261.1 1082.75  5275.9 1086.31  5301.2 1089.67  5326.8 1091.23
#Mann= 10 ,-1 , 0
  4229.6     .07       0  4282.9     .12       0  4662.3     .07       0
  4676.7     .12       0  4908.5    .035       0  4986.4    .035       0
  4993.4    .035       0  5007.4     .07       0    5133     .12       0
  5275.9     .07       0
Bank Sta=4986.4,4993.4
XS Rating Curve= 0 ,0
Exp/Cntr=0.3,0.1

Type RM Length L Ch R = 1 ,43180   ,510,510,510
BEGIN DESCRIPTION:
Tom Creek 71.0
END DESCRIPTION:
XS GIS Cut Line= 3
      2187925.02     13851275.04        2187875.       13851175.
      2187474.97     13850974.98
#Sta/Elev= 30
  4884.2 1053.17  4898.2 1052.42    4915 1049.63  4959.7 1040.49  4989.6 1032.16
  5023.2 1031.09  5023.7 1030.59  5030.3 1031.09  5040.8 1033.09  5063.1 1034.59
  5085.5 1042.65  5107.9 1044.27  5152.6 1044.68  5209.7 1047.12  5233.6 1048.61
    5256 1051.97  5272.8 1057.38  5300.7 1063.71  5317.5 1069.13  5323.1  1069.6
  5339.8  1076.3  5345.4 1076.35  5362.2 1082.06  5390.2  1087.6  5398.5 1090.54
  5420.9 1094.33  5429.3 1098.48  5434.9 1098.17  5440.5 1103.14  5443.3 1103.14
#Mann= 5 ,-1 , 0
  4884.2     .07       0  4989.6     .12       0  5023.2     .05       0
  5030.3     .12       0  5209.7     .07       0
Bank Sta=5023.2,5030.3
XS Rating Curve= 0 ,0
Exp/Cntr=0.3,0.1

Type RM Length L Ch R = 1 ,42670   ,417,417,417
BEGIN DESCRIPTION:
Tom Creek 70.0
END DESCRIPTION:
XS GIS Cut Line= 3
       2188072.6     13850990.29      2188011.85     13850734.26
      2187829.78     13850565.19
#Sta/Elev= 30
  4739.7 1042.73    4776 1043.42  4882.4 1038.81  4919.5 1035.77  4950.7 1026.63
    4961 1024.54    4978 1023.88  4978.5 1023.38  4985.1 1023.88  4995.2 1026.02
  5035.6 1028.72  5056.6 1036.96  5063.9 1036.42  5070.7 1038.69  5092.3 1040.31
  5099.1 1043.55  5106.4  1042.9  5113.3 1045.82  5120.6 1045.72  5127.4 1048.24
  5134.8 1047.58  5141.6 1050.79  5155.5 1049.45  5162.6 1051.28  5169.9 1049.64
  5176.8 1052.33  5184.1 1052.37  5198.3 1055.22  5212.5 1059.95  5251.3 1067.31
#Mann= 4 ,-1 , 0
  4739.7    .035       0    4978     .05       0  4985.1    .035       0
  4995.2     .12       0
Bank Sta=4978,4985.1
XS Rating Curve= 0 ,0
Exp/Cntr=0.3,0.1

Type RM Length L Ch R = 1 ,42253   ,445,445,445
BEGIN DESCRIPTION:
Tom Creek 69.0
END DESCRIPTION:
XS GIS Cut Line= 3
        2188275.       13850925.        2188375.       13850875.
      2188324.99     13850624.95
#Sta/Elev= 30
  4888.2  1037.8  4918.9 1037.47  4932.9 1036.41  4955.3 1035.37  4963.7 1034.66
  4977.6 1032.75    4986  1032.5  4991.6 1026.56  4997.2  1024.7  5002.5  1024.7
  5010.2 1019.87  5025.3 1017.34  5025.8 1016.84  5035.4 1016.84  5035.9 1017.34
    5051 1019.89  5061.2 1021.07  5081.6 1024.49  5091.8 1025.74  5112.2 1027.46
    5153 1029.68  5163.2 1031.17  5173.4 1033.89  5183.6 1033.79  5193.8 1034.51
  5214.2 1036.52  5224.4 1036.96  5234.6 1037.97  5244.8 1037.99    5255 1038.42
#Mann= 3 ,-1 , 0
  4888.2    .035       0  5025.3    .035       0  5035.9     .12       0
Bank Sta=5025.3,5035.9
XS Rating Curve= 0 ,0
Exp/Cntr=0.3,0.1

Type RM Length L Ch R = 1 ,41808   ,465,465,465
BEGIN DESCRIPTION:
Tom Creek 68.0
END DESCRIPTION:
XS GIS Cut Line= 3
      2188874.99     13851374.99        2188725.       13851125.
       2188879.9     13850573.68
#Sta/Elev= 30
  4704.5 1059.75  4727.8 1057.23  4781.8 1043.99  4797.8 1039.35  4828.9 1033.95
  4887.2 1026.01  4898.6 1026.51  4919.5 1024.59    4930 1025.52  4945.5 1024.19
  4951.3 1026.61    4961 1022.88  4972.7 1021.18  4982.4 1017.88  4988.3 1018.93
  5006.4    1017  5007.7 1015.32  5008.2 1014.82  5018.4 1015.32  5027.2 1017.36
  5079.1 1019.96  5131.1 1027.92  5199.6 1032.69  5215.6 1032.55  5316.9 1033.24
  5384.9 1034.02  5418.3  1039.1    5453 1043.19  5519.6 1043.75  5568.7 1043.17
#Mann= 11 ,-1 , 0
  4704.5     .07       0  4781.8    .035       0  4898.6     .07       0
  4919.5    .035       0  5007.7    .035       0  5018.4    .035       0
  5199.6     .07       0  5215.6    .035       0  5316.9     .07       0
  5418.3    .035       0  5519.6     .07       0
Bank Sta=5007.7,5018.4
XS Rating Curve= 0 ,0
Exp/Cntr=0.3,0.1

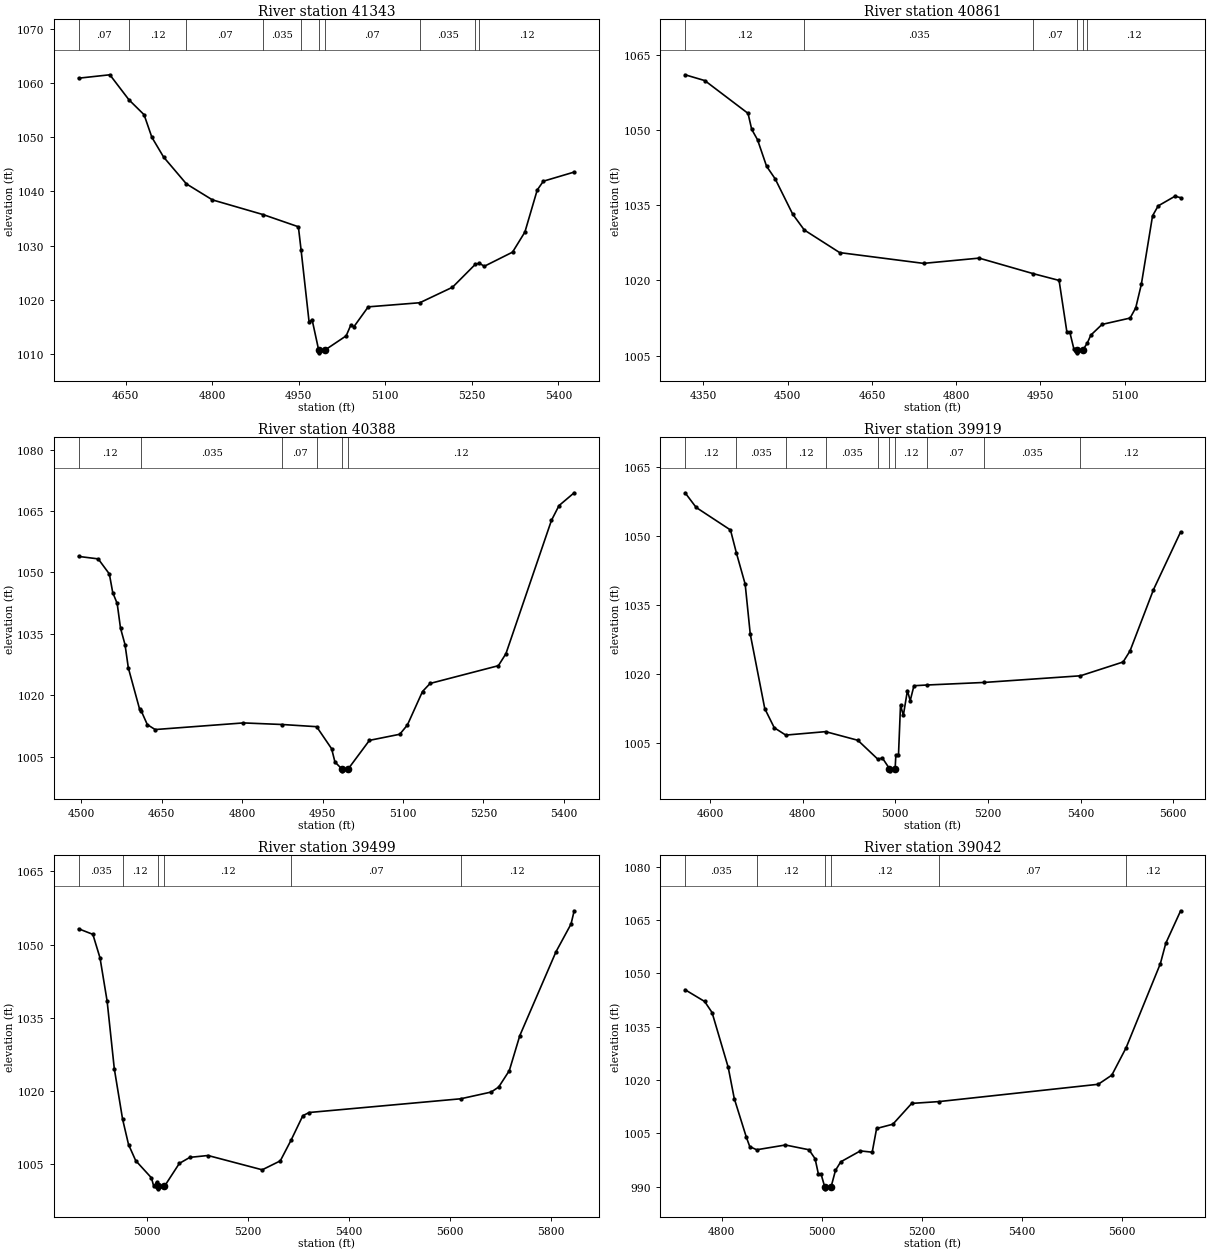
Type RM Length L Ch R = 1 ,41343   ,482,482,482
BEGIN DESCRIPTION:
Tom Creek 67.0
END DESCRIPTION:
XS GIS Cut Line= 3
        2189100.     13851599.97        2189175.       13851175.
      2189324.99     13850775.04
#Sta/Elev= 30
  4568.5 1060.93  4622.6 1061.56  4655.8 1056.92  4681.9 1054.18  4695.4 1050.01
  4715.7 1046.36  4755.2  1041.4  4800.3 1038.44  4888.8  1035.7  4949.3 1033.47
    4954 1029.16  4967.9 1015.82    4973 1016.33  4984.5 1010.67    4985 1010.17
  4995.2 1010.67  5032.1 1013.31  5040.1 1015.29  5045.4 1014.98  5070.3 1018.67
  5159.7 1019.43  5216.3 1022.29  5255.7 1026.51  5262.7 1026.74  5271.5 1026.17
  5320.4 1028.78  5341.8 1032.49  5363.2 1040.27  5373.8 1041.89  5427.2 1043.58
#Mann= 10 ,-1 , 0
  4568.5     .07       0  4655.8     .12       0  4755.2     .07       0
  4888.8    .035       0    4954     .07       0  4984.5     .05       0
  4995.2     .07       0  5159.7    .035       0  5255.7     .07       0
  5262.7     .12       0
Bank Sta=4984.5,4995.2
XS Rating Curve= 0 ,0
Exp/Cntr=0.3,0.1

Type RM Length L Ch R = 1 ,40861   ,473,473,473
BEGIN DESCRIPTION:
Tom Creek 66.0
END DESCRIPTION:
XS GIS Cut Line= 3
      2189428.03     13851728.56        2189625.       13851075.
        2189625.       13850875.
#Sta/Elev= 30
  4317.3 1061.02  4352.4 1059.86  4429.4 1053.32  4435.9 1050.14  4446.3 1048.06
  4462.4 1042.77  4477.7 1040.26    4509  1033.2  4529.6 1030.05  4592.6 1025.54
    4742 1023.39    4841 1024.44    4937 1021.35  4983.4 1019.99  4997.3  1009.7
  5002.4  1009.7  5009.9 1006.25  5014.5 1006.04    5015 1005.54  5025.3 1006.04
  5033.6 1007.48  5039.9 1009.07  5059.9 1011.21  5109.9 1012.48  5119.9 1014.51
  5129.9  1019.2  5149.9 1032.89  5159.9 1034.86  5189.9 1036.79  5199.9 1036.49
#Mann= 6 ,-1 , 0
  4317.3     .12       0  4529.6    .035       0    4937     .07       0
  5014.5     .05       0  5025.3     .07       0  5033.6     .12       0
Bank Sta=5014.5,5025.3
XS Rating Curve= 0 ,0
Exp/Cntr=0.3,0.1

Type RM Length L Ch R = 1 ,40388   ,469,469,469
BEGIN DESCRIPTION:
Tom Creek 65.0
END DESCRIPTION:
XS GIS Cut Line= 3
      2189674.99     13851725.01        2189975.       13851325.
      2190275.01     13851024.99
#Sta/Elev= 30
  4494.9  1053.9  4531.4  1053.3  4552.2 1049.62  4558.5 1045.08  4566.8 1042.41
    4573  1036.4  4581.4 1032.39  4587.6 1026.69  4608.5 1016.67    4612 1016.08
    4623 1012.84  4637.6 1011.63  4802.2 1013.25  4875.1 1012.86  4938.8 1012.33
  4966.8 1006.94    4973  1003.7  4985.6 1002.05  4986.1 1001.55  4997.9 1002.05
  5037.3 1008.99  5093.9 1010.48  5108.1 1012.74  5136.3 1020.92  5150.5 1022.89
  5277.8 1027.22  5291.9 1030.15  5376.8  1062.7  5390.9 1066.31  5419.2 1069.44
#Mann= 6 ,-1 , 0
  4494.9     .12       0    4612    .035       0  4875.1     .07       0
  4938.8     .12       0  4985.6     .05       0  4997.9     .12       0
Bank Sta=4985.6,4997.9
XS Rating Curve= 0 ,0
Exp/Cntr=0.3,0.1

Type RM Length L Ch R = 1 ,39919   ,420,420,420
BEGIN DESCRIPTION:
Tom Creek 64.0
END DESCRIPTION:
XS GIS Cut Line= 3
      2189642.37     13851874.27        2190075.       13851725.
      2190578.79     13851377.09
#Sta/Elev= 30
  4546.2 1059.45  4570.1 1056.26  4644.2 1051.36  4657.1 1046.32  4675.9 1039.59
  4686.9 1028.72  4718.2 1012.54  4738.7 1008.38  4763.5 1006.78  4849.5 1007.53
  4919.2 1005.65  4962.4 1001.53  4972.1 1001.81  4987.3  999.51  4987.8  999.01
  4999.7  999.51  5001.2 1002.38  5006.9 1002.38  5011.3 1013.31  5017.4 1011.06
  5026.2 1016.46  5032.2 1014.25  5040.3 1017.51  5069.2 1017.67  5191.5 1018.22
  5399.8 1019.67  5491.9 1022.67  5506.8 1025.07  5557.5  1038.4  5616.1 1050.95
#Mann= 10 ,-1 , 0
  4546.2     .12       0  4657.1    .035       0  4763.5     .12       0
  4849.5    .035       0  4962.4     .12       0  4987.3     .05       0
  4999.7     .12       0  5069.2     .07       0  5191.5    .035       0
  5399.8     .12       0
Bank Sta=4987.3,4999.7
XS Rating Curve= 0 ,0
Exp/Cntr=0.3,0.1

Type RM Length L Ch R = 1 ,39499   ,457,457,457
BEGIN DESCRIPTION:
Tom Creek 63.0
END DESCRIPTION:
XS GIS Cut Line= 3
      2190025.03     13852174.97        2190125.       13852075.
      2190601.81     13851382.44
#Sta/Elev= 30
  4863.8 1053.25    4892 1052.11  4906.2 1047.28  4920.3 1038.41  4934.5 1024.58
  4950.9 1014.26  4962.7 1009.05  4976.9 1005.75  5008.2 1002.21  5012.6  1000.5
  5018.7  1001.4  5021.3 1000.47  5021.8  999.97  5033.8 1000.47  5063.4 1005.18
  5084.3 1006.42  5120.2  1006.8  5227.7 1003.87  5263.5  1005.7  5285.2 1010.01
  5308.2 1014.96  5320.8 1015.61    5621 1018.42  5681.5  1019.8  5696.4 1020.83
  5717.4 1024.18  5738.3 1031.38    5810 1048.55  5839.8 1054.23    5846 1056.94
#Mann= 6 ,-1 , 0
  4863.8    .035       0  4950.9     .12       0  5021.3     .05       0
  5033.8     .12       0  5285.2     .07       0    5621     .12       0
Bank Sta=5021.3,5033.8
XS Rating Curve= 0 ,0
Exp/Cntr=0.3,0.1

Type RM Length L Ch R = 1 ,39042   ,425,425,425
BEGIN DESCRIPTION:
Tom Creek 62.0
END DESCRIPTION:
XS GIS Cut Line= 3
      2190424.99     13852475.02        2190525.       13852225.
      2190740.36     13851536.37
#Sta/Elev= 30
  4726.5 1045.38  4765.6 1042.08  4780.4 1038.98  4812.7 1023.58  4824.8 1014.81
    4849 1003.92  4855.8  1001.3  4869.6 1000.41  4927.1 1001.75  4974.2 1000.41
  4986.4   997.9  4993.1  993.54  4998.4  993.54  5005.8  989.93  5006.3  989.43
  5018.3  989.93  5027.2  994.63  5037.7  997.02  5076.9 1000.09  5100.6  999.73
  5109.4 1006.39  5141.9 1007.59  5179.6 1013.44  5234.2 1013.95  5552.5 1018.81
  5579.7 1021.38  5608.3 1029.09  5676.8 1052.73  5687.6 1058.44  5717.3 1067.57
#Mann= 6 ,-1 , 0
  4726.5    .035       0  4869.6     .12       0  5005.8     .05       0
  5018.3     .12       0  5234.2     .07       0  5608.3     .12       0
Bank Sta=5005.8,5018.3
XS Rating Curve= 0 ,0
Exp/Cntr=0.3,0.1

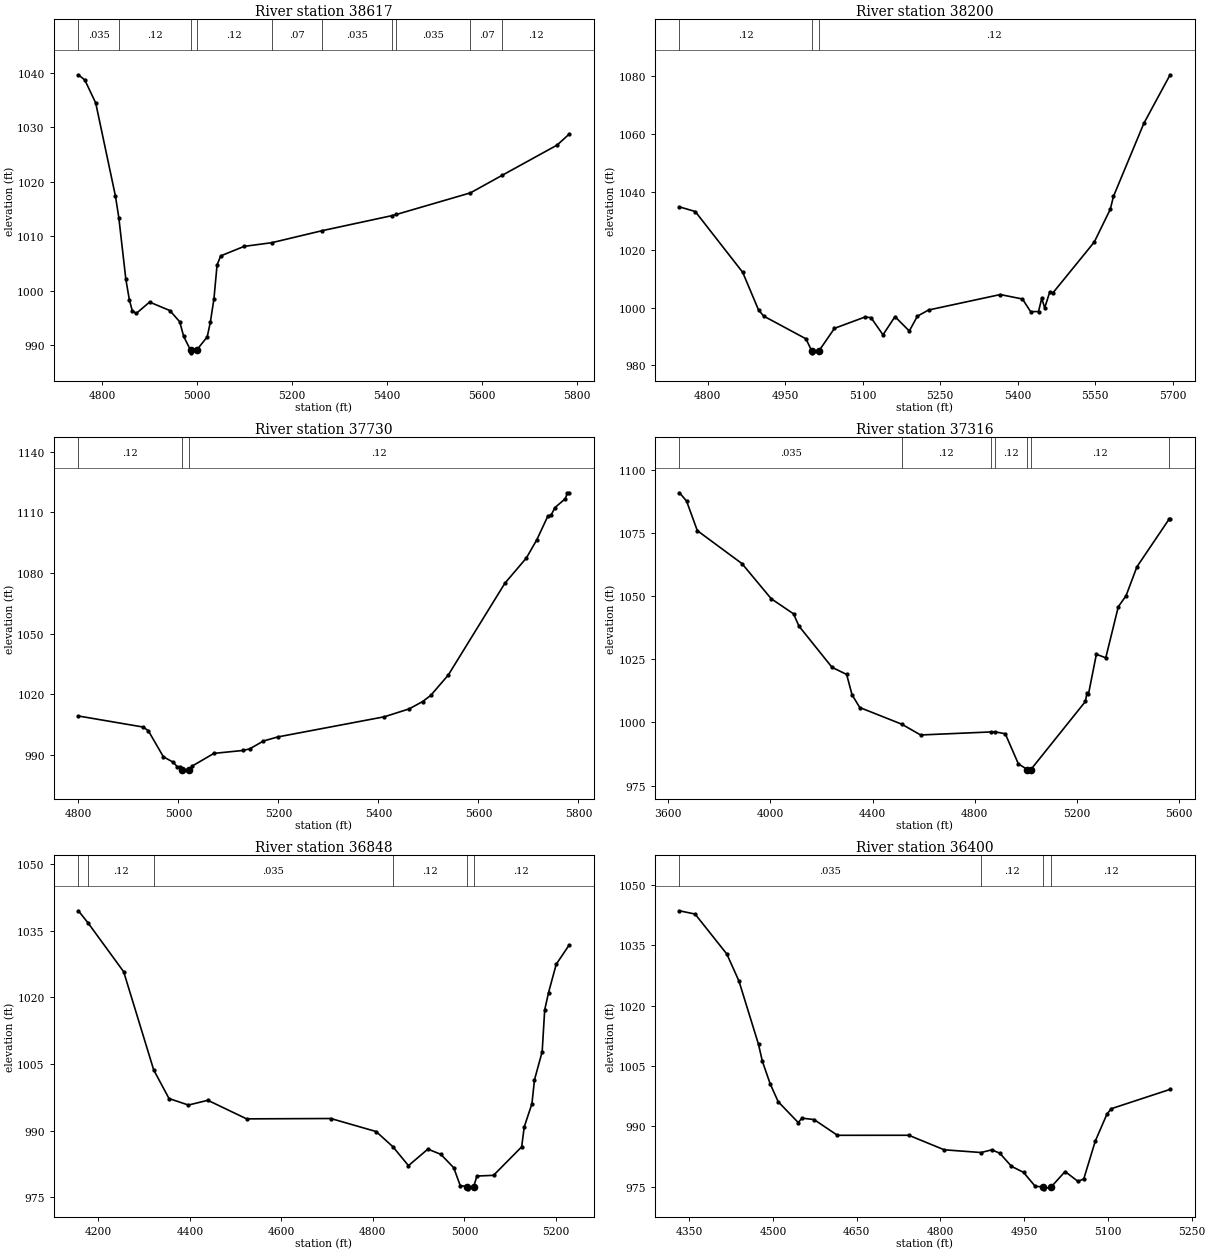
Type RM Length L Ch R = 1 ,38617   ,417,417,417
BEGIN DESCRIPTION:
Tom Creek 61.0
END DESCRIPTION:
XS GIS Cut Line= 3
        2190625.       13852625.        2190825.       13852475.
      2191337.97     13851882.38
#Sta/Elev= 30
    4750 1039.59  4763.5 1038.64  4786.5 1034.42  4828.1 1017.33  4835.2 1013.37
    4850 1002.08  4857.3  998.35  4863.5  996.31  4871.9   995.8    4900  997.89
  4942.7  996.34  4963.5  994.28  4971.9  991.58  4986.3  989.08  4986.8  988.58
  4999.2  989.08  5021.4   991.5    5028  994.18  5035.6  998.47  5042.2 1004.69
  5049.9 1006.37  5099.3 1008.11  5157.7 1008.79  5264.1    1011  5411.3 1013.76
  5420.1 1013.97  5576.1 1017.93  5643.6 1021.18  5758.4 1026.68  5783.8 1028.68
#Mann= 10 ,-1 , 0
    4750    .035       0  4835.2     .12       0  4986.3     .05       0
  4999.2     .12       0  5157.7     .07       0  5264.1    .035       0
  5411.3     .07       0  5420.1    .035       0  5576.1     .07       0
  5643.6     .12       0
Bank Sta=4986.3,4999.2
XS Rating Curve= 0 ,0
Exp/Cntr=0.3,0.1

Type RM Length L Ch R = 1 ,38200   ,470,470,470
BEGIN DESCRIPTION:
Tom Creek 60.0
END DESCRIPTION:
XS GIS Cut Line= 3
      2190774.98       13852875.        2191025.       13852825.
        2191625.       13852475.
#Sta/Elev= 30
  4745.3 1034.85  4775.9 1033.24  4867.7 1012.21  4898.3   999.2  4908.5  997.05
  4990.1  989.21  5001.7  984.86  5002.2  984.36  5014.6  984.86  5045.3  992.84
  5104.1  996.73    5116  996.54  5139.2  990.59  5162.4  996.88  5190.1  991.91
  5205.8  997.04  5227.3  999.17  5366.2 1004.52  5409.2 1002.98  5424.9  998.61
  5440.2  998.64  5446.4 1003.19  5452.2  999.93  5462.1 1005.49  5467.9 1005.06
  5548.1 1022.68  5579.1 1034.02  5585.3  1038.5    5644 1063.71  5694.9 1080.54
#Mann= 3 ,-1 , 0
  4745.3     .12       0  5001.7     .05       0  5014.6     .12       0
Bank Sta=5001.7,5014.6
XS Rating Curve= 0 ,0
Exp/Cntr=0.3,0.1

Type RM Length L Ch R = 1 ,37730   ,414,414,414
BEGIN DESCRIPTION:
Tom Creek 59.0
END DESCRIPTION:
XS GIS Cut Line= 3
      2191124.96       13853175.        2191325.       13853175.
      2191825.02     13852574.97
#Sta/Elev= 30
    4800 1009.13    4930 1003.63    4940 1001.74    4970  988.91    4990  986.17
  4997.5  984.01  5003.3  984.01  5007.1  982.45  5007.6  981.95  5020.4  982.45
    5028  984.38    5071   990.6  5128.3  992.03  5142.6  992.83  5169.9  996.72
  5198.5  998.74    5412 1008.75  5461.5 1012.66  5488.2 1016.27  5504.4 1019.29
  5539.6 1029.42  5652.8 1074.91  5695.8 1087.43  5716.6 1096.43  5738.8 1108.22
  5745.3 1108.76  5753.1 1112.44  5773.9 1116.88  5777.8 1119.75  5781.1 1119.75
#Mann= 3 ,-1 , 0
    4800     .12       0  5007.1     .05       0  5020.4     .12       0
Bank Sta=5007.1,5020.4
XS Rating Curve= 0 ,0
Exp/Cntr=0.3,0.1

Type RM Length L Ch R = 1 ,37316   ,468,468,468
BEGIN DESCRIPTION:
Tom Creek 58.0
END DESCRIPTION:
XS GIS Cut Line= 3
      2190439.45     13854216.85        2191575.       13853475.
       2192058.4     13853180.77
#Sta/Elev= 30
  3643.6 1090.95  3671.3  1087.7  3713.5 1075.96  3888.5 1062.91  4003.1 1048.99
  4090.6 1043.01  4111.7 1038.17  4241.4 1021.83  4298.6 1019.02  4319.7 1010.95
    4350 1005.92  4514.7  999.31  4588.3  995.05  4864.2  996.26    4881  996.26
    4920  995.54  4971.4  983.61  5006.9  981.35  5007.4  980.85  5020.2  981.35
  5234.1 1008.33  5240.2  1011.8  5246.1 1011.25    5277 1027.01  5313.8  1025.6
  5362.9 1045.83  5393.2 1050.17  5435.9 1061.64    5561 1080.38  5565.9 1080.38
#Mann= 7 ,-1 , 0
  3643.6    .035       0  4514.7     .12       0  4864.2    .035       0
    4881     .12       0  5006.9     .05       0  5020.2     .12       0
    5561    .094       0
Bank Sta=5006.9,5020.2
XS Rating Curve= 0 ,0
Exp/Cntr=0.3,0.1

Type RM Length L Ch R = 1 ,36848   ,448,448,448
BEGIN DESCRIPTION:
Tom Creek 57.0
END DESCRIPTION:
XS GIS Cut Line= 3
      2191174.99     13854475.01        2191775.       13853875.
      2191875.02     13853674.96
#Sta/Elev= 30
  4156.5 1039.46  4177.4 1036.76  4255.5 1025.73  4321.1 1003.63  4354.5   997.2
  4396.9  995.73  4439.4   996.8  4524.2  992.62  4708.1   992.7  4807.1  989.77
    4844  986.33  4877.8  982.09  4920.2  985.81  4948.5  984.64  4976.8  981.61
  4990.9  977.61  5006.5  977.37    5007  976.87  5020.4  977.37  5027.4  979.75
  5063.7  979.91  5125.2  986.32  5130.8  990.81  5147.6  996.02  5153.2 1001.41
    5170 1007.74  5175.5 1017.14  5183.9 1021.04  5200.7 1027.42  5228.7 1031.71
#Mann= 6 ,-1 , 0
  4156.5    .035       0  4177.4     .12       0  4321.1    .035       0
    4844     .12       0  5006.5     .05       0  5020.4     .12       0
Bank Sta=5006.5,5020.4
XS Rating Curve= 0 ,0
Exp/Cntr=0.3,0.1

Type RM Length L Ch R = 1 ,36400   ,417,417,417
BEGIN DESCRIPTION:
Tom Creek 56.0
END DESCRIPTION:
XS GIS Cut Line= 3
      2191474.99     13854775.01        2191925.       13854275.
      2192124.96     13854225.01
#Sta/Elev= 30
  4332.5 1043.56  4360.5 1042.74  4417.3 1032.82    4439 1026.12  4474.1 1010.35
  4480.9  1006.2  4495.1 1000.52  4509.3  996.13  4545.2  990.95  4551.9  992.04
  4573.6  991.69  4615.4  987.78  4743.2  987.79  4806.7  984.18  4872.8   983.5
    4892  984.18  4906.2  983.33  4927.1  980.08  4948.8  978.57  4969.7   975.1
  4984.4  974.98  4984.9  974.48  4998.4  974.98  5023.2  978.78  5046.4  976.32
  5056.7  976.97  5077.3  986.35    5098     993  5105.7  994.38  5211.3  999.19
#Mann= 4 ,-1 , 0
  4332.5    .035       0  4872.8     .12       0  4984.4     .05       0
  4998.4     .12       0
Bank Sta=4984.4,4998.4
XS Rating Curve= 0 ,0
Exp/Cntr=0.3,0.1