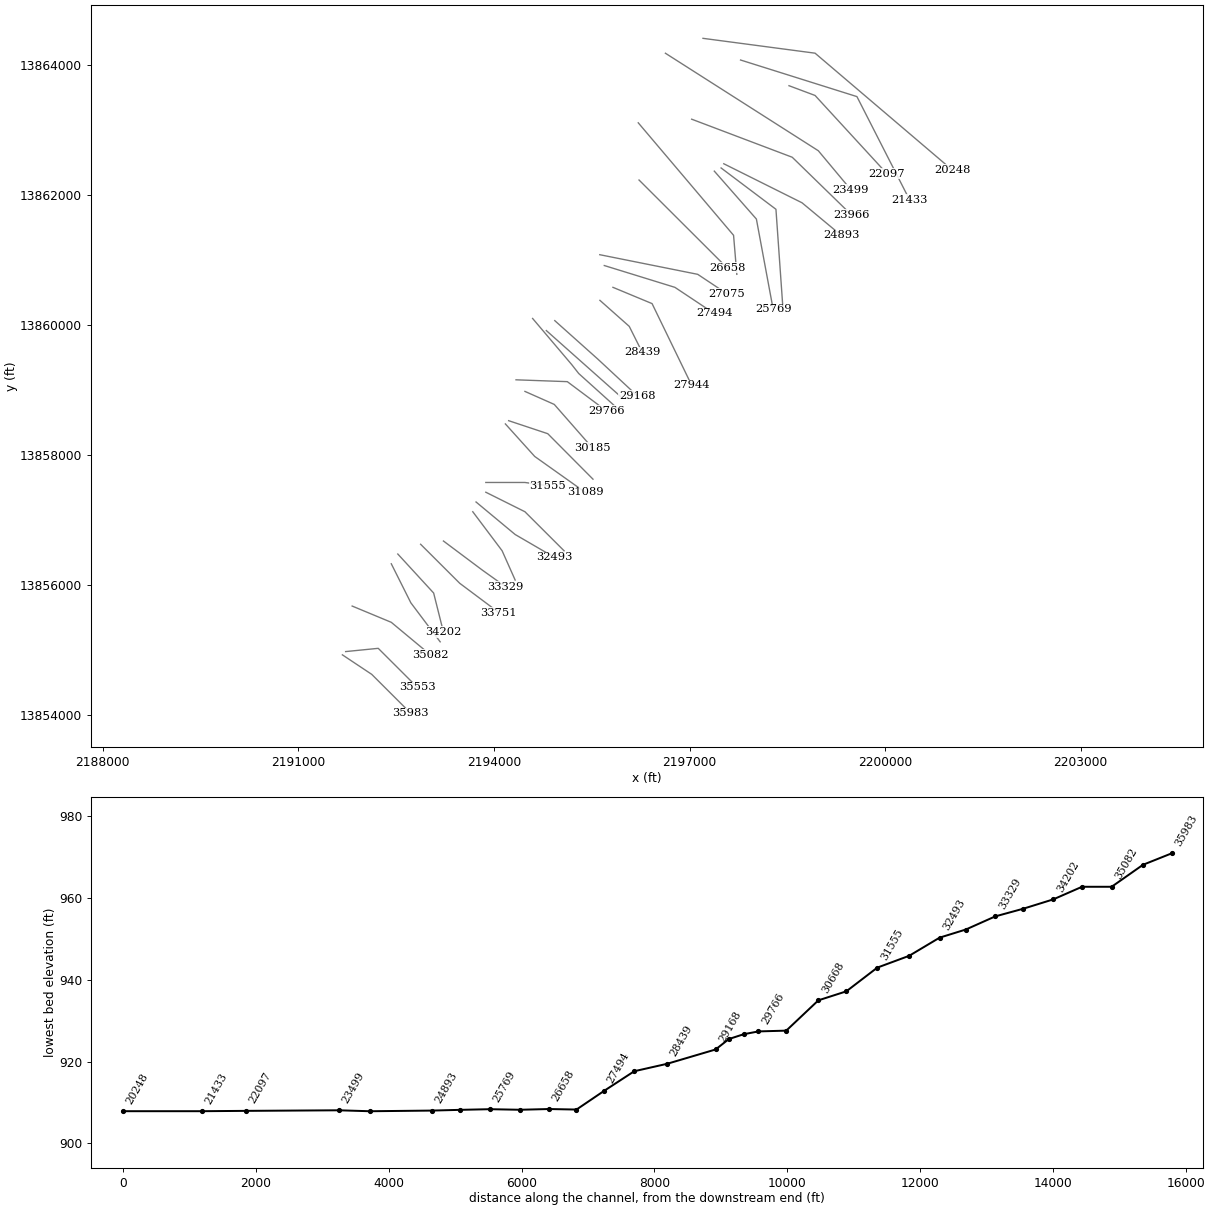
HEC-RAS study Tom Creek.prj: Tom Creek Base Level Engineering

--- Tom Creek.g01 (geometry) --- (continued)

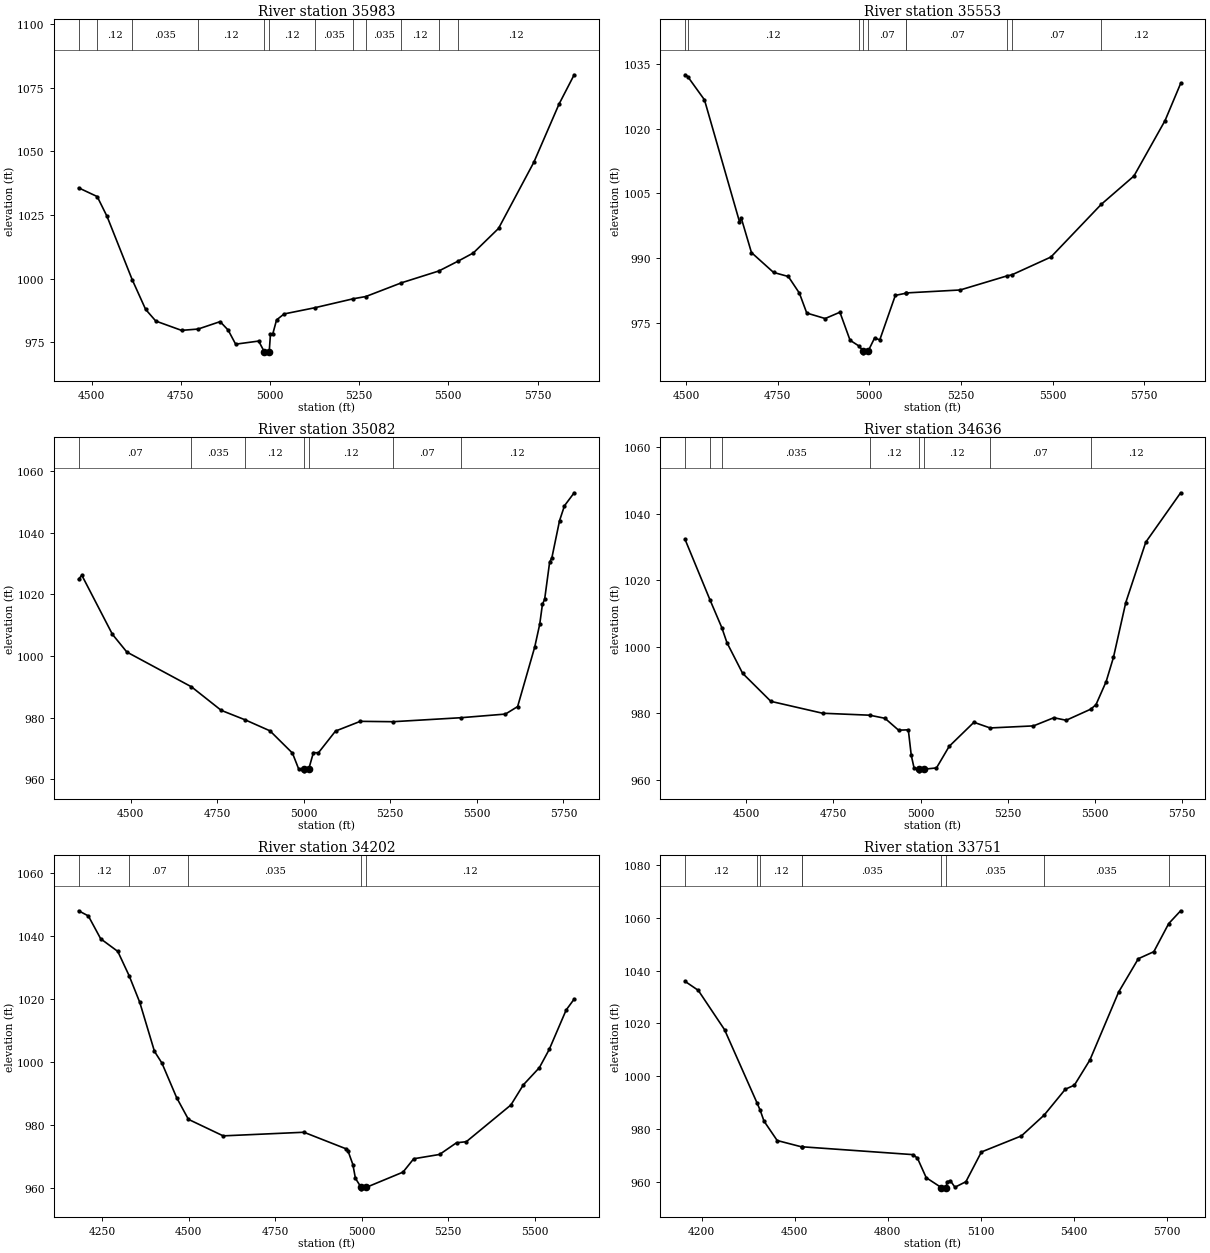
Type RM Length L Ch R = 1 ,35983   ,430,430,430
BEGIN DESCRIPTION:
Tom Creek 55.0
END DESCRIPTION:
XS GIS Cut Line= 3
      2191674.97     13854925.02        2192125.       13854625.
        2192725.       13854025.
#Sta/Elev= 30
  4463.4 1035.65  4515.5 1032.23  4543.1 1024.43  4613.5  999.64  4651.2  987.95
  4679.8  983.36  4751.9  979.71  4798.5  980.23  4860.1  983.14  4882.6  979.83
  4903.6  974.29  4968.2  975.51  4983.7  971.39  4984.2  970.89  4997.8  971.39
  5001.3  978.34  5007.8  978.34  5018.4  983.82  5039.6  986.16  5124.9  988.57
  5233.6  992.12  5268.6  992.99  5368.6  998.38  5473.4 1003.02    5528 1006.93
    5570 1010.09  5640.7 1019.72  5739.7 1045.69  5810.4 1068.54  5852.8 1080.03
#Mann= 12 ,-1 , 0
  4463.4     .07       0  4515.5     .12       0  4613.5    .035       0
  4798.5     .12       0  4983.7     .05       0  4997.8     .12       0
  5124.9    .035       0  5233.6     .07       0  5268.6    .035       0
  5368.6     .12       0  5473.4     .07       0    5528     .12       0
Bank Sta=4983.7,4997.8
XS Rating Curve= 0 ,0
Exp/Cntr=0.3,0.1

Type RM Length L Ch R = 1 ,35553   ,471,471,471
BEGIN DESCRIPTION:
Tom Creek 54.0
END DESCRIPTION:
XS GIS Cut Line= 3
      2191724.96       13854975.        2192225.       13855025.
      2192825.03     13854424.97
#Sta/Elev= 30
  4497.8 1032.46  4504.8 1032.06  4550.6 1026.66  4646.1  998.45  4651.1  999.24
  4678.7  991.31    4739  986.71  4779.2  985.77  4809.4  981.92  4829.5  977.31
  4879.7  976.04  4919.9   977.5  4947.6  971.01  4970.9  969.73  4983.2   968.6
  4983.7   968.1  4997.4   968.6  5014.5  971.54  5028.6   971.1    5071   981.4
  5099.3  981.89  5101.2  981.97  5247.8  982.65  5375.5  985.91  5388.6  986.15
  5495.3  990.28  5632.3 1002.46  5721.6 1009.03  5806.4 1021.86  5848.9 1030.45
#Mann= 10 ,-1 , 0
  4497.8     .07       0  4504.8     .12       0  4970.9     .07       0
  4983.2     .05       0  4997.4     .07       0  5099.3     .12       0
  5101.2     .07       0  5375.5    .035       0  5388.6     .07       0
  5632.3     .12       0
Bank Sta=4983.2,4997.4
XS Rating Curve= 0 ,0
Exp/Cntr=0.3,0.1

Type RM Length L Ch R = 1 ,35082   ,446,446,446
BEGIN DESCRIPTION:
Tom Creek 53.0
END DESCRIPTION:
XS GIS Cut Line= 3
      2191824.99       13855675.        2192425.       13855425.
      2193024.97     13854925.02
#Sta/Elev= 30
    4350 1024.96  4359.2 1026.23  4447.5 1007.06  4489.2  1001.3  4675.9     990
  4761.7  982.37  4831.2  979.27  4902.5  975.72  4967.5  968.48  4985.4  963.34
  5000.1  963.23  5000.6  962.73  5014.3  963.23    5028  968.66  5042.3  968.57
  5091.8  975.64  5163.4   978.8  5257.6  978.68  5453.1  979.97  5582.5  981.16
  5617.7  983.59  5667.1 1002.93  5681.5 1010.31  5689.3 1016.76  5695.8 1018.47
  5710.1 1030.45  5716.6 1031.89  5738.7 1043.92    5753 1048.79    5781    1053
#Mann= 7 ,-1 , 0
    4350     .07       0  4675.9    .035       0  4831.2     .12       0
  5000.1     .05       0  5014.3     .12       0  5257.6     .07       0
  5453.1     .12       0
Bank Sta=5000.1,5014.3
XS Rating Curve= 0 ,0
Exp/Cntr=0.3,0.1

Type RM Length L Ch R = 1 ,34636   ,434,434,434
BEGIN DESCRIPTION:
Tom Creek 52.0
END DESCRIPTION:
XS GIS Cut Line= 3
      2192425.02     13856324.96        2192725.       13855725.
      2193175.01     13855124.98
#Sta/Elev= 30
  4324.6 1032.21  4396.1 1014.04  4429.8 1005.75  4444.7  1001.2  4489.5  992.02
  4570.5   983.6  4718.7  980.03  4853.9  979.44  4897.6  978.51  4936.7  974.94
  4964.6  975.05    4973  967.41  4981.4  963.46  4994.9  963.23  4995.4  962.73
  5010.5  963.23  5045.4  963.61  5081.8  970.09  5152.7  977.31  5199.1  975.61
  5323.5  976.23  5381.8  978.68  5417.3  977.92  5487.7  981.25  5502.7  982.61
  5531.8  989.53  5552.7  996.78  5588.1 1013.28  5645.4  1031.4  5745.4 1046.24
#Mann= 8 ,-1 , 0
  4324.6     .12       0  4396.1     .07       0  4429.8    .035       0
  4853.9     .12       0  4994.9     .05       0  5010.5     .12       0
  5199.1     .07       0  5487.7     .12       0
Bank Sta=4994.9,5010.5
XS Rating Curve= 0 ,0
Exp/Cntr=0.3,0.1

Type RM Length L Ch R = 1 ,34202   ,451,451,451
BEGIN DESCRIPTION:
Tom Creek 51.0
END DESCRIPTION:
XS GIS Cut Line= 3
        2192525.     13856475.01        2193075.       13855875.
        2193225.     13855275.01
#Sta/Elev= 30
  4181.7 1048.04  4209.8  1046.4  4245.5 1039.13  4294.9 1035.12  4327.7 1027.39
  4358.4 1018.93  4400.9 1003.35  4422.5  999.61    4465  988.63    4499  981.74
  4599.5  976.48  4832.9  977.63  4953.4  972.42  4960.2  971.74  4974.4  967.37
  4981.8  962.98  4998.1  960.14  4998.6  959.64  5013.8  960.14  5119.3  964.95
  5150.3   969.2    5225  970.57    5274  974.29  5302.3  974.62  5431.2   986.3
  5467.2   992.7  5513.6  998.18    5542 1003.96  5590.9 1016.49  5614.1 1019.97
#Mann= 5 ,-1 , 0
  4181.7     .12       0  4327.7     .07       0    4499    .035       0
  4998.1    .035       0  5013.8     .12       0
Bank Sta=4998.1,5013.8
XS Rating Curve= 0 ,0
Exp/Cntr=0.3,0.1

Type RM Length L Ch R = 1 ,33751   ,422,422,422
BEGIN DESCRIPTION:
Tom Creek 50.0
END DESCRIPTION:
XS GIS Cut Line= 3
      2192875.02     13856624.98        2193475.       13856025.
        2194075.       13855575.
#Sta/Elev= 30
  4146.5  1035.9  4188.9 1032.52  4273.7 1017.63  4378.5   989.9    4389  987.03
    4401  983.01  4443.5  975.66  4522.2  973.26  4524.1  973.28  4881.9  970.31
    4896  968.98  4924.3  961.58  4972.8  957.86  4973.3  957.36  4988.9  957.86
  4991.5  960.05  5002.3  960.44  5016.9  957.97  5052.3  960.06  5102.3  971.31
  5231.5  977.41  5304.9   985.3  5373.1  995.08  5402.3  996.62  5452.3 1006.14
    5545 1031.87  5608.5 1044.49  5658.5 1047.15  5706.5 1057.79    5745 1062.64
#Mann= 9 ,-1 , 0
  4146.5     .12       0  4378.5     .07       0    4389     .12       0
  4522.2     .07       0  4524.1    .035       0  4972.8     .05       0
  4988.9    .035       0  5304.9    .035       0  5706.5     .12       0
Bank Sta=4972.8,4988.9
XS Rating Curve= 0 ,0
Exp/Cntr=0.3,0.1

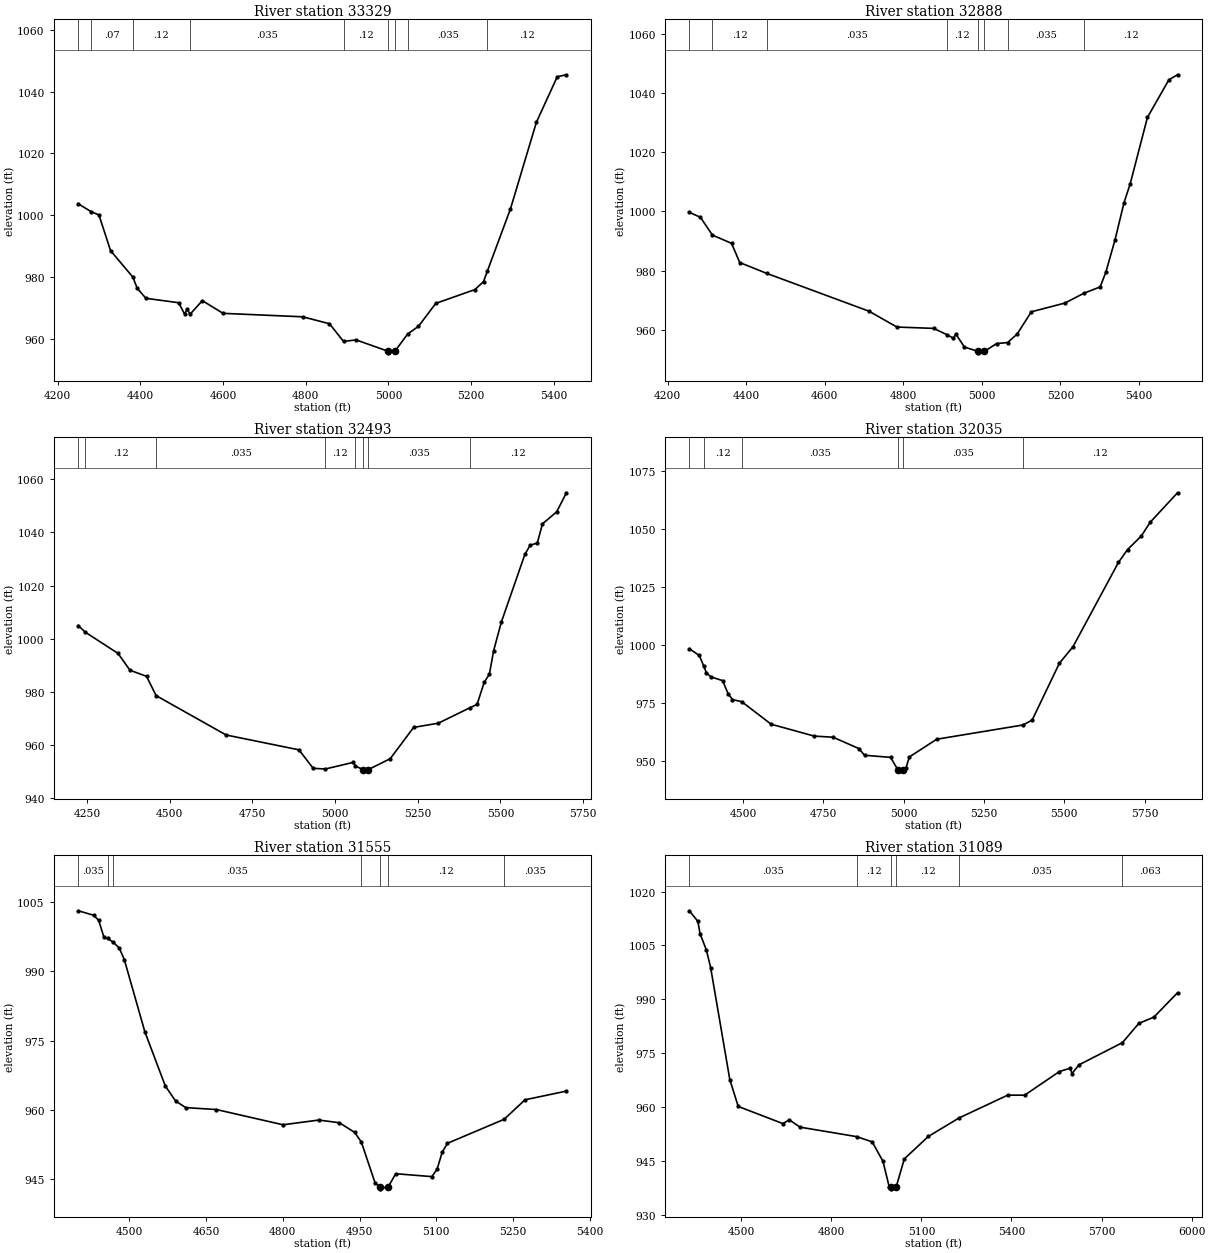
Type RM Length L Ch R = 1 ,33329   ,441,441,441
BEGIN DESCRIPTION:
Tom Creek 49.0
END DESCRIPTION:
XS GIS Cut Line= 3
      2193225.03     13856674.98        2193825.       13856225.
      2194175.01     13855974.99
#Sta/Elev= 30
    4250 1003.72    4281 1001.17    4300  1000.1  4328.1  988.55  4381.9     980
  4392.7  976.33  4413.5  973.13  4492.7   971.7  4507.3  967.96  4513.5  969.73
  4520.2  967.95    4550  972.37    4600  968.26  4792.7  967.14  4857.3   964.9
  4891.3  959.18  4921.8  959.66  4999.3  955.98  4999.8  955.48  5015.4  955.98
  5046.4  961.58  5072.5  964.06  5114.3  971.48  5208.9  975.95  5229.8  978.54
  5239.1  981.96  5294.9 1002.07  5357.6 1030.09    5408 1044.84  5430.1 1045.46
#Mann= 9 ,-1 , 0
    4250    .063       0    4281     .07       0  4381.9     .12       0
  4520.2    .035       0  4891.3     .12       0  4999.3     .05       0
  5015.4     .12       0  5046.4    .035       0  5239.1     .12       0
Bank Sta=4999.3,5015.4
XS Rating Curve= 0 ,0
Exp/Cntr=0.3,0.1

Type RM Length L Ch R = 1 ,32888   ,395,395,395
BEGIN DESCRIPTION:
Tom Creek 48.0
END DESCRIPTION:
XS GIS Cut Line= 3
      2193675.02     13857124.97        2194125.       13856525.
        2194325.       13856075.
#Sta/Elev= 30
  4255.6  999.69  4283.7  998.02  4314.1  992.03  4362.9  989.23  4383.7  982.75
  4451.9  979.12  4712.9  966.32  4783.7  960.99  4877.4  960.53  4910.4  958.44
  4927.4  957.23  4933.7  958.61  4955.6  954.23  4990.1  952.78  4990.6  952.28
  5006.5  952.78  5037.7  955.42  5065.5  955.75  5089.7  958.61  5125.9  966.13
  5211.4  969.08  5259.6  972.39    5301  974.52  5315.4  979.43  5338.6  990.28
  5361.9 1002.99  5377.6 1009.36  5421.4 1031.74  5476.1 1044.45    5498 1046.12
#Mann= 8 ,-1 , 0
  4255.6    .035       0  4314.1     .12       0  4451.9    .035       0
  4910.4     .12       0  4990.1     .05       0  5006.5     .12       0
  5065.5    .035       0  5259.6     .12       0
Bank Sta=4990.1,5006.5
XS Rating Curve= 0 ,0
Exp/Cntr=0.3,0.1

Type RM Length L Ch R = 1 ,32493   ,458,458,458
BEGIN DESCRIPTION:
Tom Creek 47.0
END DESCRIPTION:
XS GIS Cut Line= 3
      2193725.01     13857274.99        2194325.       13856775.
      2194924.98     13856425.01
#Sta/Elev= 30
  4223.9 1004.95  4244.9 1002.47  4344.3  994.44  4380.1  988.14  4430.2  985.84
  4459.3  978.58    4671  963.77    4891  958.19    4934  951.24  4970.5  950.98
  5055.8  953.49  5061.2  952.09  5084.7  950.79  5085.2  950.29  5101.2  950.79
    5167  954.86  5237.7  966.63  5312.1   968.2  5407.1  973.97  5429.5  975.28
    5451  983.57  5466.7  986.64  5479.6  995.49  5502.7 1006.18  5574.2 1031.78
    5590 1035.14  5611.5 1035.98  5627.2  1043.2  5670.2 1047.71  5699.5 1054.88
#Mann= 8 ,-1 , 0
  4223.9    .035       0  4244.9     .12       0  4459.3    .035       0
  4970.5     .12       0  5061.2    .035       0  5084.7     .05       0
  5101.2    .035       0  5407.1     .12       0
Bank Sta=5084.7,5101.2
XS Rating Curve= 0 ,0
Exp/Cntr=0.3,0.1

Type RM Length L Ch R = 1 ,32035   ,480,480,480
BEGIN DESCRIPTION:
Tom Creek 46.0
END DESCRIPTION:
XS GIS Cut Line= 3
      2193875.02     13857424.99        2194475.       13857125.
      2195074.98     13856525.02
#Sta/Elev= 30
  4333.4  998.44  4364.1  995.55  4378.4  990.92  4386.5  987.94  4400.5  986.34
  4436.8   984.7  4453.6  979.16  4467.5  976.54  4496.3  975.64  4587.7  965.94
  4721.9  960.82  4780.6  960.33  4861.6   955.4  4878.4  952.56  4959.5  951.66
  4981.9  946.35  4982.4  945.85  4998.5  946.35  5007.7  947.27  5018.3  951.87
  5103.2  959.47    5372  965.61  5400.2  967.72    5485   992.2  5527.5  999.36
  5668.9 1035.66  5697.2  1041.2  5739.6 1046.96  5767.9 1052.99  5852.7 1065.64
#Mann= 6 ,-1 , 0
  4333.4    .035       0  4378.4     .12       0  4496.3    .035       0
  4981.9    .035       0  4998.5    .035       0    5372     .12       0
Bank Sta=4981.9,4998.5
XS Rating Curve= 0 ,0
Exp/Cntr=0.3,0.1

Type RM Length L Ch R = 1 ,31555   ,466,466,466
BEGIN DESCRIPTION:
Tom Creek 45.0
END DESCRIPTION:
XS GIS Cut Line= 3
      2193874.99       13857575.        2194475.       13857575.
      2194825.03       13857525.
#Sta/Elev= 30
  4400.4 1003.07  4430.4 1002.11  4440.4 1000.99  4450.4  997.39  4457.7  997.08
  4467.4  996.39  4480.4  995.04  4490.4   992.5  4530.4  976.94  4570.4  965.21
  4590.4  961.96  4610.4  960.52  4670.4   960.1  4800.4  956.81  4870.4  957.83
  4910.4  957.25  4940.4  955.16  4953.4  953.08  4980.4   944.2  4989.6  943.46
  4990.1  942.96  5006.3  943.46  5020.6  946.23  5091.3   945.6  5101.4  947.21
  5111.5   950.9  5121.6   952.8  5232.3  957.99  5273.2  962.21    5354  964.09
#Mann= 7 ,-1 , 0
  4400.4    .035       0  4457.7     .12       0  4467.4    .035       0
  4953.4     .12       0  4989.6     .05       0  5006.3     .12       0
  5232.3    .035       0
Bank Sta=4989.6,5006.3
XS Rating Curve= 0 ,0
Exp/Cntr=0.3,0.1

Type RM Length L Ch R = 1 ,31089   ,421,421,421
BEGIN DESCRIPTION:
Tom Creek 44.0
END DESCRIPTION:
XS GIS Cut Line= 3
      2194174.97     13858475.03        2194625.       13857975.
       2195401.4      13857422.4
#Sta/Elev= 30
  4327.3 1014.67  4355.4 1011.72  4362.8 1008.28  4383.8 1003.75    4398  998.85
  4461.9   967.6  4489.9  960.13  4638.6  955.35  4660.3   956.4  4695.4  954.36
  4884.5  951.71  4936.1  950.25    4972  944.83  4992.9  937.66    4999  937.66
  4999.5  937.16  5015.8  937.66  5043.1  945.51  5122.8  951.75  5225.4  956.92
  5387.4  963.28  5443.9  963.27  5559.5  969.85  5595.2  970.79  5601.5  969.31
  5624.7  971.72  5769.5  977.91  5823.9  983.26  5874.3  985.03    5953  991.82
#Mann= 6 ,-1 , 0
  4327.3    .035       0  4884.5     .12       0    4999     .05       0
  5015.8     .12       0  5225.4    .035       0  5769.5    .063       0
Bank Sta=4999,5015.8
XS Rating Curve= 0 ,0
Exp/Cntr=0.3,0.1

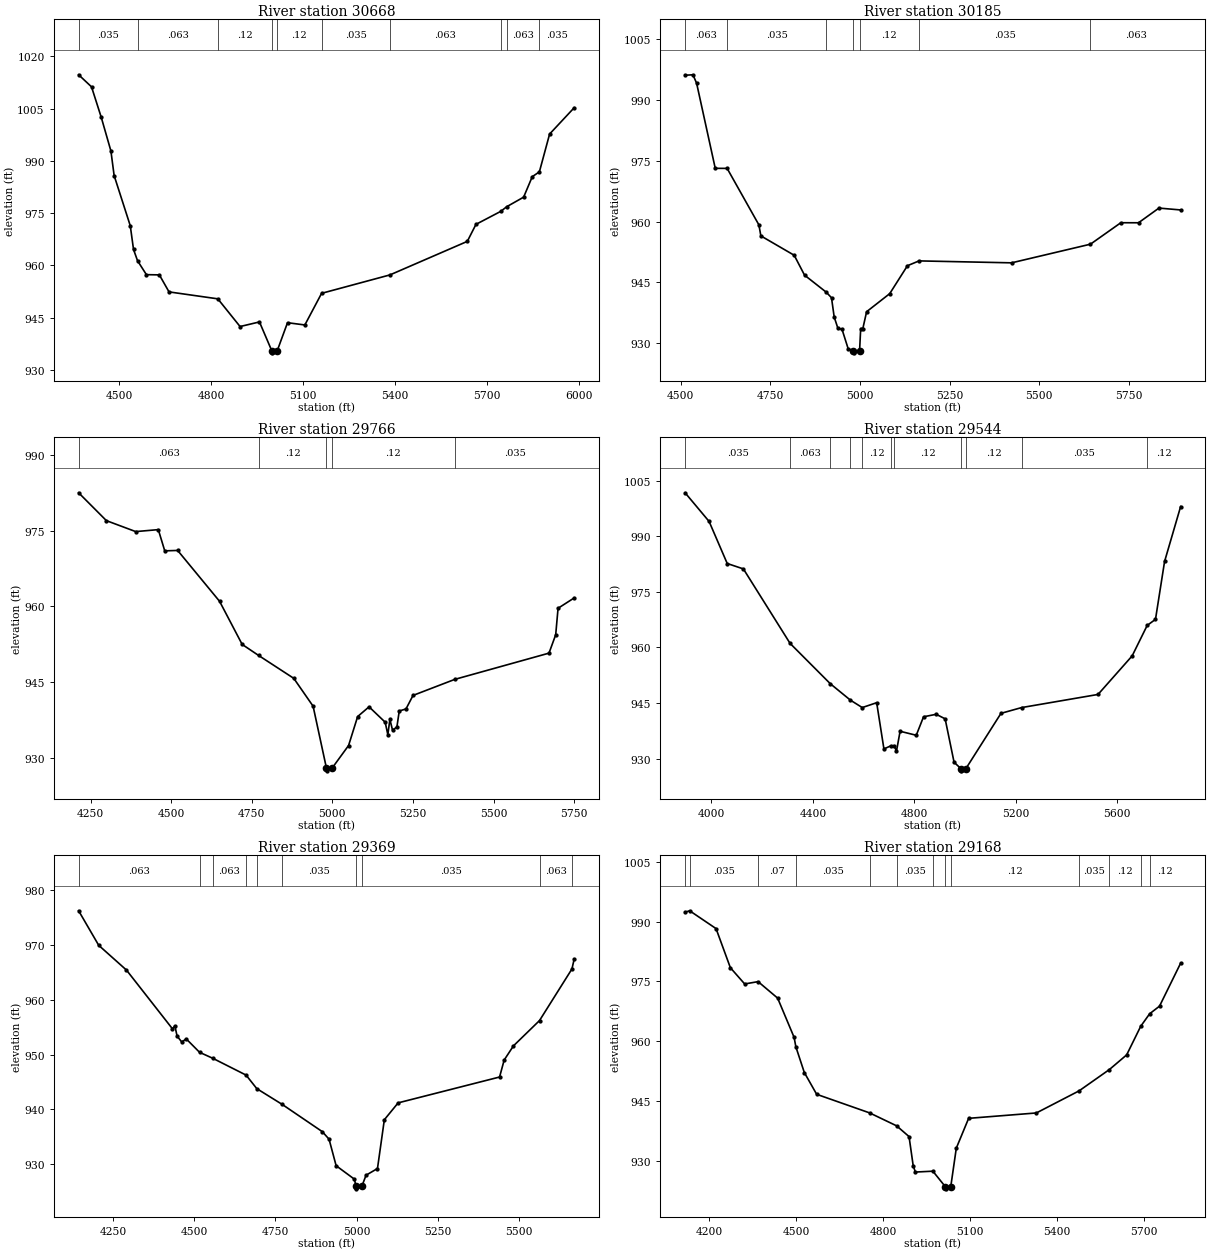
Type RM Length L Ch R = 1 ,30668   ,483,483,483
BEGIN DESCRIPTION:
Tom Creek 43.0
END DESCRIPTION:
XS GIS Cut Line= 3
      2194225.03     13858524.99        2194825.       13858325.
      2195518.95     13857625.57
#Sta/Elev= 30
    4367 1014.67  4409.1 1011.21  4440.8 1002.49  4472.4  992.82  4482.9  985.78
  4535.6  971.39  4546.2  964.59  4559.4  961.34  4588.3  957.37  4630.5  957.31
  4662.1  952.43  4821.4  950.44    4894   942.5  4957.3  943.82    4998  935.46
  4998.5  934.96  5014.9  935.46  5048.9   943.6  5105.5  942.95  5160.2  952.02
  5383.3   957.3  5635.8  966.91  5664.1  971.79  5744.9  975.51  5764.7  976.86
  5819.7  979.59  5847.9  985.46  5871.1  986.84  5904.5  997.68  5984.7 1005.22
#Mann= 10 ,-1 , 0
    4367    .035       0  4559.4    .063       0  4821.4     .12       0
    4998     .05       0  5014.9     .12       0  5160.2    .035       0
  5383.3    .063       0  5744.9    .035       0  5764.7    .063       0
  5871.1    .035       0
Bank Sta=4998,5014.9
XS Rating Curve= 0 ,0
Exp/Cntr=0.3,0.1

Type RM Length L Ch R = 1 ,30185   ,419,419,419
BEGIN DESCRIPTION:
Tom Creek 42.0
END DESCRIPTION:
XS GIS Cut Line= 3
      2194475.03     13858974.99        2194925.       13858775.
      2195510.79     13858105.51
#Sta/Elev= 30
  4512.1  996.15    4534  996.26  4544.2  994.18  4596.2  973.14  4629.3  973.13
  4717.9  959.17  4723.4  956.45  4816.4  951.66  4845.2  946.75  4905.7  942.54
  4920.4  941.16  4927.9   936.4  4938.2  933.63  4949.8  933.35  4966.9  928.56
  4981.7  928.05  4982.2  927.55  4998.7  928.05  5001.8  933.55  5007.8  933.55
  5018.3  937.71  5082.8  942.18  5132.2  949.08  5164.6  950.27  5422.6  949.79
  5642.6   954.4  5727.3   959.7  5776.6  959.69  5833.6  963.32  5894.1  962.86
#Mann= 7 ,-1 , 0
  4512.1    .063       0  4629.3    .035       0  4905.7     .12       0
  4981.7     .05       0  4998.7     .12       0  5164.6    .035       0
  5642.6    .063       0
Bank Sta=4981.7,4998.7
XS Rating Curve= 0 ,0
Exp/Cntr=0.3,0.1

Type RM Length L Ch R = 1 ,29766   ,222,222,222
BEGIN DESCRIPTION:
Tom Creek 41.0
END DESCRIPTION:
XS GIS Cut Line= 3
      2194337.97     13859153.24        2195125.       13859125.
      2195724.97     13858675.02
#Sta/Elev= 30
  4212.8  982.52    4299  976.99  4389.9  974.82    4460  975.21    4480     971
    4520  971.08  4650.1  960.99  4720.2  952.44  4771.2  950.25  4880.3  945.71
  4940.3  940.18  4981.8  927.86  4982.3  927.36  4998.8  927.86  5050.3  932.38
  5078.5  938.13  5113.9  940.06  5163.9  937.01  5172.2  934.53  5178.5  937.57
  5186.8  935.42  5200.3  936.07  5207.6  939.23  5228.5  939.64  5250.3  942.32
  5380.1  945.51  5672.2  950.71    5693  954.36  5700.3  959.61  5750.3  961.66
#Mann= 5 ,-1 , 0
  4212.8    .063       0  4771.2     .12       0  4981.8     .05       0
  4998.8     .12       0  5380.1    .035       0
Bank Sta=4981.8,4998.8
XS Rating Curve= 0 ,0
Exp/Cntr=0.3,0.1

Type RM Length L Ch R = 1 ,29544   ,222,222,222
BEGIN DESCRIPTION:
Tom Creek 40.5
END DESCRIPTION:
XS GIS Cut Line= 4
      2194592.63     13860096.58      2195191.58     13859388.54
        2195300.       13859250.      2195930.35     13858680.69
#Sta/Elev= 30
  3896.7 1001.72  3991.3  993.98  4062.7  982.63  4126.4  981.17  4310.4  961.07
  4469.1  950.17  4548.3  945.74  4594.8  943.75  4651.6  945.06  4680.2  932.58
  4706.6   933.4  4720.4  933.46  4729.6  931.96  4743.9  937.35  4807.6  936.27
  4836.3  941.26  4886.1  941.93  4921.4  940.71  4956.6  928.99    4985  927.17
  4985.5  926.67  5002.3  927.17  5141.5  942.19  5222.4  943.74  5523.9  947.29
  5658.4   957.7  5717.6  965.92  5750.3  967.56  5786.1  983.18  5849.4  998.01
#Mann= 11 ,-1 , 0
  3896.7    .035       0  4310.4    .063       0  4469.1     .12       0
  4548.3    .035       0  4594.8     .12       0  4706.6    .035       0
  4720.4     .12       0    4985     .05       0  5002.3     .12       0
  5222.4    .035       0  5717.6     .12       0
Bank Sta=4985,5002.3
XS Rating Curve= 0 ,0
Exp/Cntr=0.3,0.1

Type RM Length L Ch R = 1 ,29369   ,201,201,201
BEGIN DESCRIPTION:
Tom Creek 40.0
END DESCRIPTION:
XS GIS Cut Line= 3
      2194803.07     13859910.47      2195441.67     13859341.65
      2195941.06     13858897.24
#Sta/Elev= 30
  4144.8  976.28  4206.6  969.97  4291.9  965.45  4433.2  954.73  4440.8  955.26
  4447.5   953.4  4461.7  952.33  4475.9  952.87  4516.7  950.43    4557  949.35
  4659.7  946.27  4692.6   943.8  4770.7  940.92  4893.9  935.95  4914.8  934.57
  4936.6  929.72  4992.6  927.27  4997.7     926  4998.2   925.5  5015.9     926
  5028.6  927.99  5063.7  929.21  5084.8  938.12  5127.2   941.2  5439.1  945.92
  5453.3  949.03  5481.8  951.61  5561.9  956.23  5661.6  965.65  5668.5  967.44
#Mann= 10 ,-1 , 0
  4144.8    .063       0  4516.7    .035       0    4557    .063       0
  4659.7    .035       0  4692.6    .063       0  4770.7    .035       0
  4997.7    .035       0  5015.9    .035       0  5561.9    .063       0
  5661.6    .035       0
Bank Sta=4997.7,5015.9
XS Rating Curve= 0 ,0
Exp/Cntr=0.3,0.1

Type RM Length L Ch R = 1 ,29168   ,729,729,729
BEGIN DESCRIPTION:
Tom Creek 39.0
END DESCRIPTION:
XS GIS Cut Line= 3
      2194932.64     13860063.13      2195590.36     13859474.13
      2196194.11     13858911.15
#Sta/Elev= 30
  4117.1  992.36  4132.9  992.71  4223.8  988.24  4273.2  978.42  4322.5  974.35
  4368.8  974.93  4436.1   970.8    4493  960.93  4498.9  958.59  4528.1  952.13
  4570.7  946.66  4753.1     942  4846.3  938.75  4889.2  936.05  4903.4  928.78
  4910.9  927.15  4971.3  927.37  5014.7  923.44  5015.2  922.94  5032.9  923.44
  5052.1  933.15  5094.6  940.63  5328.1  941.98  5475.3  947.52    5580  952.88
  5639.4  956.55  5687.9  963.73  5718.7  966.87  5752.7  968.78  5825.5  979.56
#Mann= 13 ,-1 , 0
  4117.1     .12       0  4132.9    .035       0  4368.8     .07       0
  4498.9    .035       0  4753.1     .07       0  4846.3    .035       0
  4971.3     .12       0  5014.7     .05       0  5032.9     .12       0
  5475.3    .035       0    5580     .12       0  5687.9    .035       0
  5718.7     .12       0
Bank Sta=5014.7,5032.9
XS Rating Curve= 0 ,0
Exp/Cntr=0.3,0.1

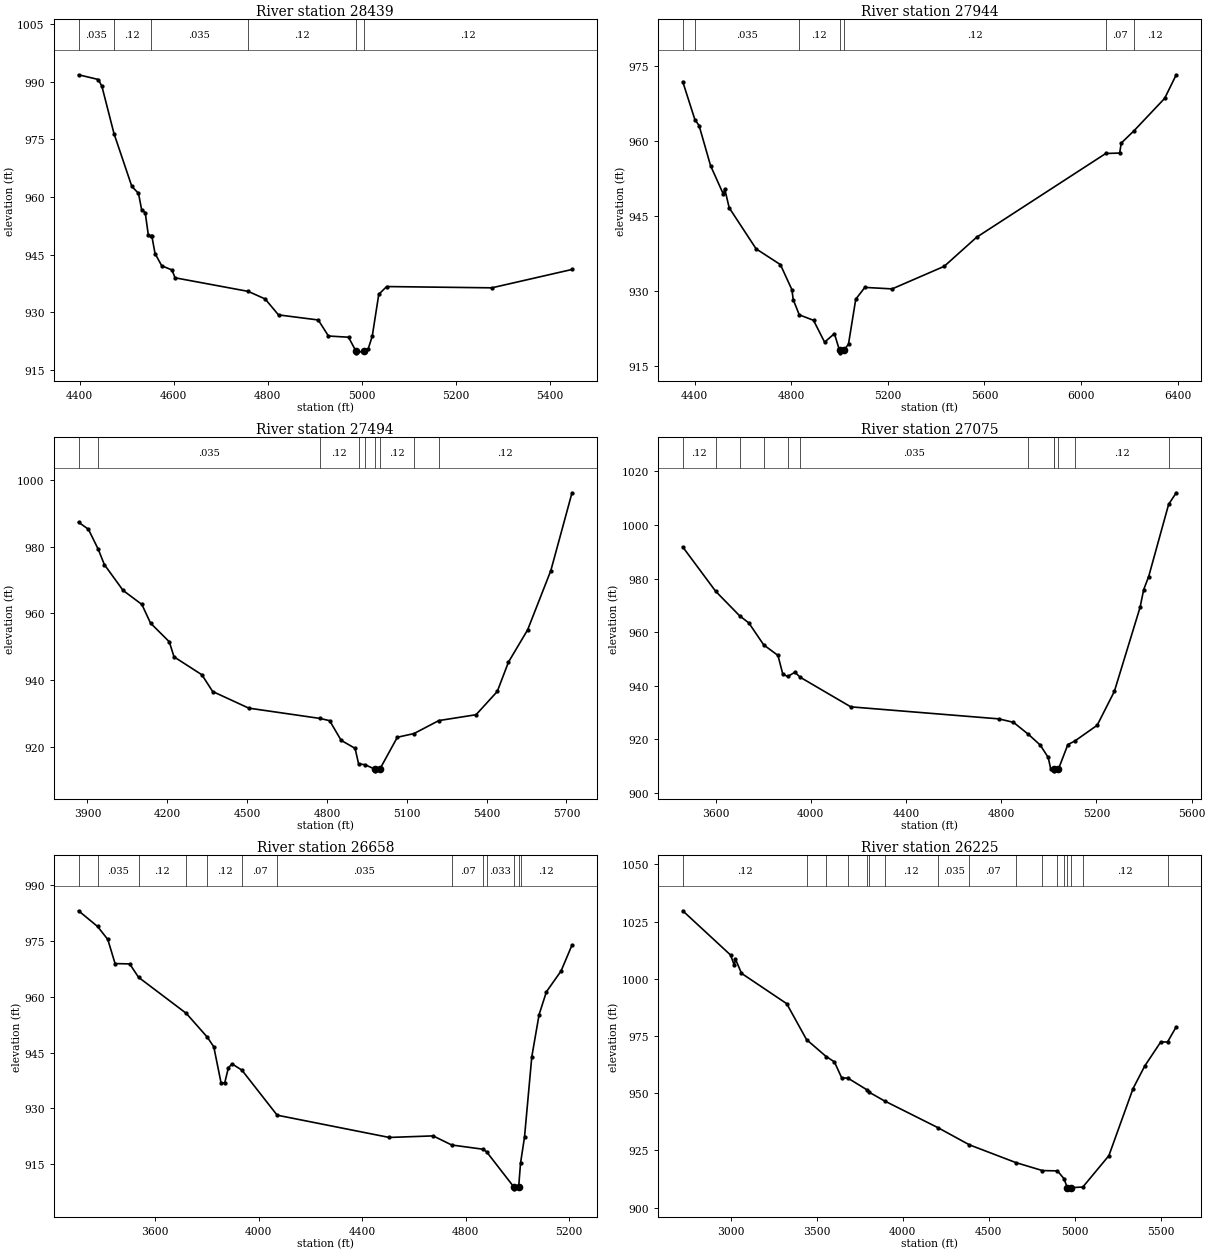
Type RM Length L Ch R = 1 ,28439   ,495,495,495
BEGIN DESCRIPTION:
Tom Creek 38.0
END DESCRIPTION:
XS GIS Cut Line= 3
      2195624.98     13860375.02        2196075.       13859975.
      2196274.99     13859575.02
#Sta/Elev= 30
  4397.9  991.85  4440.2  990.62  4447.7   988.8  4473.3  976.54  4511.2  962.79
  4525.4  960.98  4532.1  956.71  4539.7  955.94  4546.4  950.05    4551  949.88
  4553.9  949.77  4560.6   945.3  4574.8  942.11  4596.5  941.02  4603.2  938.98
  4758.8  935.44  4794.7  933.47  4823.1  929.32  4907.6     928  4929.3  923.82
    4972  923.51  4987.5  919.94    4988  919.44  5005.8  919.94    5014  920.55
  5022.4  923.74  5036.3  934.68  5053.1   936.7  5276.7  936.37  5447.2  941.15
#Mann= 6 ,-1 , 0
  4397.9    .035       0  4473.3     .12       0    4551    .035       0
  4758.8     .12       0  4987.5     .05       0  5005.8     .12       0
Bank Sta=4987.5,5005.8
XS Rating Curve= 0 ,0
Exp/Cntr=0.3,0.1

Type RM Length L Ch R = 1 ,27944   ,450,450,450
BEGIN DESCRIPTION:
Tom Creek 37.0
END DESCRIPTION:
XS GIS Cut Line= 3
      2195824.99       13860575.        2196425.       13860325.
      2197032.37     13859069.95
#Sta/Elev= 30
    4350  971.78  4400.3  964.19  4417.7  963.01  4465.4  954.98  4518.5  949.28
  4523.9  950.39  4542.3   946.6  4653.9  938.39  4754.6  935.24  4802.3  930.22
  4807.7  928.25  4832.7  925.21  4891.7  924.12  4937.7  919.75  4978.3  921.46
  4999.4  918.12  4999.9  917.62  5017.7  918.12  5036.7  919.38  5066.7  928.33
  5104.4  930.69  5217.4  930.39  5433.3   934.9  5567.3   940.7  6102.3  957.43
  6160.1  957.52  6166.5  959.51    6219  961.95  6346.4  968.44  6394.3  973.15
#Mann= 7 ,-1 , 0
    4350     .12       0  4400.3    .035       0  4832.7     .12       0
  4999.4     .05       0  5017.7     .12       0  6102.3     .07       0
    6219     .12       0
Bank Sta=4999.4,5017.7
XS Rating Curve= 0 ,0
Exp/Cntr=0.3,0.1

Type RM Length L Ch R = 1 ,27494   ,419,419,419
BEGIN DESCRIPTION:
Tom Creek 36.0
END DESCRIPTION:
XS GIS Cut Line= 3
      2195692.11     13860910.18        2196775.       13860575.
      2197375.01     13860174.99
#Sta/Elev= 30
  3866.4  987.33  3903.5  985.21  3940.4  979.24  3963.4  974.64  4033.9  966.89
  4104.4   962.7    4137  957.11  4207.4  951.52  4225.3     947    4330  941.63
  4370.5  936.62  4506.2  931.64  4773.4  928.56  4810.1  927.89  4853.4     922
  4905.8  919.59  4918.9  914.98  4943.6  914.68  4980.3  913.36  4980.8  912.86
  4998.8  913.36  5064.6  922.92  5127.2  924.02  5220.4  927.91  5360.5  929.67
  5440.2  936.63  5482.2  945.42  5554.3  955.09  5641.5  972.84  5721.1  996.14
#Mann= 9 ,-1 , 0
  3866.4     .12       0  3940.4    .035       0  4773.4     .12       0
  4918.9     .07       0  4943.6     .12       0  4980.3     .05       0
  4998.8     .12       0  5127.2     .07       0  5220.4     .12       0
Bank Sta=4980.3,4998.8
XS Rating Curve= 0 ,0
Exp/Cntr=0.3,0.1

Type RM Length L Ch R = 1 ,27075   ,417,417,417
BEGIN DESCRIPTION:
Tom Creek 35.0
END DESCRIPTION:
XS GIS Cut Line= 3
       2195622.7     13861076.84        2197125.       13860775.
      2197575.04     13860474.98
#Sta/Elev= 30
    3462  991.81    3600  975.29  3701.1   966.1  3739.7  963.45  3802.2  955.25
  3862.1  951.32  3882.5  944.28  3903.3  943.47  3933.5  945.06  3954.1  943.25
  4168.1  932.13  4790.3  927.64  4851.5  926.35  4914.5  921.85  4963.7  917.89
  4997.3  913.27  5007.8  909.01  5019.8  908.77  5021.1  908.75  5021.6  908.25
  5039.7  908.75    5080  918.05  5108.9  919.36  5203.1  925.25  5275.3   937.9
  5383.4  969.29  5398.4  975.86  5419.5  980.77  5503.3 1007.71  5535.2 1012.02
#Mann= 12 ,-1 , 0
    3462     .12       0    3600    .035       0  3701.1     .07       0
  3802.2    .035       0  3903.3     .07       0  3954.1    .035       0
  4914.5     .12       0  5019.8     .07       0  5021.1     .05       0
  5039.7     .07       0  5108.9     .12       0  5503.3    .035       0
Bank Sta=5021.1,5039.7
XS Rating Curve= 0 ,0
Exp/Cntr=0.3,0.1

Type RM Length L Ch R = 1 ,26658   ,433,433,433
BEGIN DESCRIPTION:
Tom Creek 34.0
END DESCRIPTION:
XS GIS Cut Line= 3
      2196224.99     13862225.01        2197425.       13861025.
        2197575.       13860875.
#Sta/Elev= 30
  3302.7  983.16  3376.3  978.94  3415.9  975.45  3444.1  968.96  3500.7  968.87
  3534.9  965.27  3719.5  955.58    3801  949.16    3826  946.57  3854.3  936.82
  3868.4  936.91  3882.5  940.94  3896.7  941.98  3934.8   940.3  4071.1  928.19
  4504.8   922.2  4674.5  922.62  4746.5  920.17    4869  919.02  4881.5  918.33
  4986.9  908.88  4987.4  908.38  5005.5  908.88  5012.7  915.27  5028.1   922.3
  5056.3   943.9  5084.6  955.26  5112.9  961.38  5169.5  966.96  5211.9  973.95
#Mann= 13 ,-1 , 0
  3302.7     .12       0  3376.3    .035       0  3534.9     .12       0
  3719.5    .035       0    3801     .12       0  3934.8     .07       0
  4071.1    .035       0  4746.5     .07       0    4869     .12       0
  4881.5    .033       0  4986.9    .033       0  5005.5    .033       0
  5012.7     .12       0
Bank Sta=4986.9,5005.5
XS Rating Curve= 0 ,0
Exp/Cntr=0.3,0.1

Type RM Length L Ch R = 1 ,26225   ,456,456,456
BEGIN DESCRIPTION:
Tom Creek 33.0
END DESCRIPTION:
XS GIS Cut Line= 3
      2196212.98     13863104.59        2197675.       13861375.
        2197725.     13860775.01
#Sta/Elev= 30
    2722 1029.71  2999.6 1010.39  3021.6 1005.88  3028.2  1008.6  3063.3 1002.38
  3325.9  989.12  3441.1  973.43  3555.3     966  3602.8  963.72  3645.7  956.66
  3680.9  956.61  3790.9  951.53  3806.5  950.35  3894.3  946.62  4206.7  934.85
  4387.3  927.43  4656.1   919.7  4811.5  916.18  4898.9  916.04  4937.2   912.6
  4955.8   908.7  4956.3   908.2  4974.7   908.7  5046.4     909  5197.5  922.69
  5337.9     952  5405.7  961.86  5498.5  972.34  5538.7   972.4  5588.8  979.01
#Mann= 17 ,-1 , 0
    2722     .12       0  3441.1    .035       0  3555.3     .12       0
  3680.9     .07       0  3790.9     .12       0  3806.5     .07       0
  3894.3     .12       0  4206.7    .035       0  4387.3     .07       0
  4656.1    .035       0  4811.5     .12       0  4898.9     .12       0
  4937.2    .033       0  4955.8    .033       0  4974.7    .033       0
  5046.4     .12       0  5538.7    .035       0
Bank Sta=4955.8,4974.7
XS Rating Curve= 0 ,0
Exp/Cntr=0.3,0.1

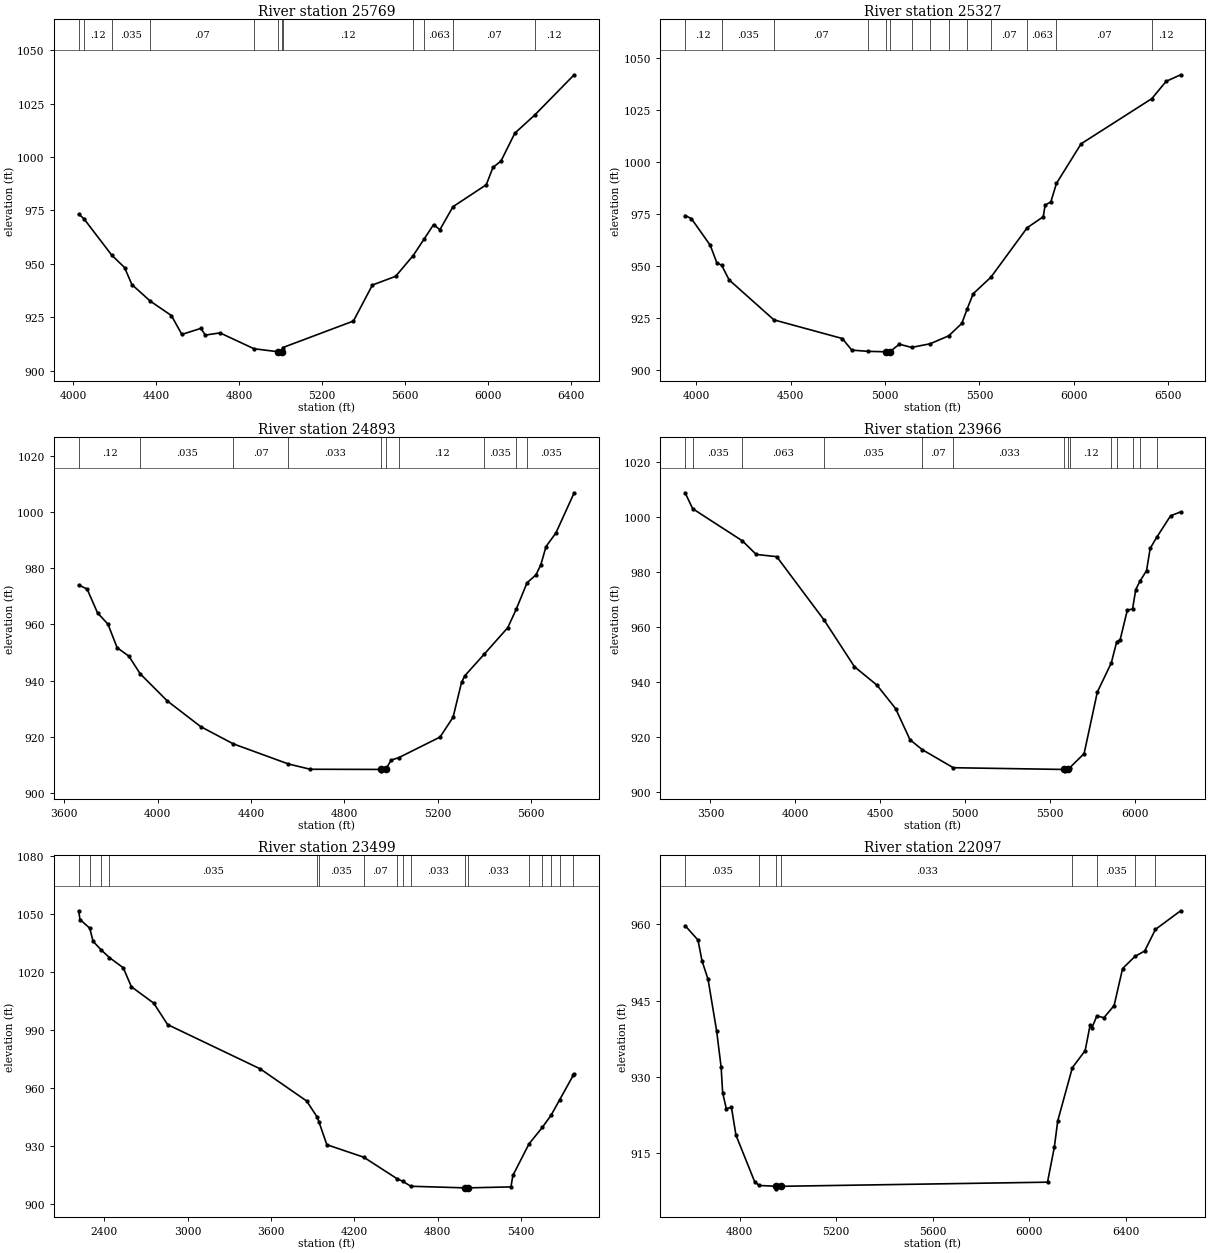
Type RM Length L Ch R = 1 ,25769   ,442,442,442
BEGIN DESCRIPTION:
Tom Creek 32.0
END DESCRIPTION:
XS GIS Cut Line= 3
      2197379.58     13862361.61        2198025.       13861625.
      2198282.07     13860238.29
#Sta/Elev= 30
    4025   973.3  4049.9  971.21  4185.2  954.01  4246.5  948.28  4281.7  940.32
  4371.3   932.5  4472.5   925.8  4522.7  916.96  4614.8   919.8  4635.7  916.64
  4706.8  917.68  4870.6  910.26  4987.7  908.84  4988.2  908.34  5006.7  908.84
  5008.3  910.76  5350.2  923.23  5441.7  940.09  5553.6  944.16  5638.1  953.86
  5692.5  961.82  5736.6  968.37  5767.1  965.99  5830.2  976.75  5990.9  987.05
  6022.9  995.12  6062.1  998.19  6128.6  1011.2  6223.9 1019.63  6414.7 1038.53
#Mann= 12 ,-1 , 0
    4025    .035       0  4049.9     .12       0  4185.2    .035       0
  4371.3     .07       0  4870.6    .033       0  4987.7    .033       0
  5006.7    .033       0  5008.3     .12       0  5638.1     .07       0
  5692.5    .063       0  5830.2     .07       0  6223.9     .12       0
Bank Sta=4987.7,5006.7
XS Rating Curve= 0 ,0
Exp/Cntr=0.3,0.1

Type RM Length L Ch R = 1 ,25327   ,434,434,434
BEGIN DESCRIPTION:
Tom Creek 31.0
END DESCRIPTION:
XS GIS Cut Line= 3
      2197483.78     13862410.18        2198325.       13861775.
      2198435.13     13860209.36
#Sta/Elev= 30
  3941.4  974.25  3974.6  972.77  4074.5  959.94  4109.9  951.39  4134.7  950.37
  4174.4  943.28  4411.6  924.04  4773.8  915.07  4823.8  909.49  4911.8  908.89
    5006  908.68  5006.5  908.18  5025.1  908.68  5075.7  912.33  5140.4  910.79
  5238.8  912.54  5337.2  916.37  5406.5  922.35  5435.6  929.51  5466.7  936.61
  5560.8   944.6  5752.7  968.38  5837.6  973.64  5847.6   979.3  5877.7  980.77
  5907.5  989.69  6038.1 1008.75  6412.5 1030.48    6488 1038.77    6565 1041.95
#Mann= 14 ,-1 , 0
  3941.4     .12       0  4134.7    .035       0  4411.6     .07       0
  4911.8    .033       0    5006    .033       0  5025.1    .033       0
  5140.4     .12       0  5238.8     .12       0  5337.2     .07       0
  5435.6     .12       0  5560.8     .07       0  5752.7    .063       0
  5907.5     .07       0  6412.5     .12       0
Bank Sta=5006,5025.1
XS Rating Curve= 0 ,0
Exp/Cntr=0.3,0.1

Type RM Length L Ch R = 1 ,24893   ,927,927,927
BEGIN DESCRIPTION:
Tom Creek 30.0
END DESCRIPTION:
XS GIS Cut Line= 3
        2197525.       13862475.        2198725.       13861875.
      2199325.03     13861374.98
#Sta/Elev= 30
  3661.7  974.04    3698  972.58  3742.8   964.1  3787.5   960.1  3826.6  951.75
  3876.9  948.74  3925.7  942.44  4041.8  932.82  4184.4  923.72  4323.8   917.6
  4560.6  910.43    4654  908.56  4957.4   908.5  4957.9     908  4976.7   908.5
  5000.5  911.81  5033.1  912.69  5209.7  919.99  5265.6  927.03  5302.1  939.46
  5315.8  941.77  5399.3  949.47  5499.9  958.86    5536  965.37  5582.6  974.84
    5621  977.63  5641.8   981.3    5664   987.7  5706.3  992.54  5784.4 1006.79
#Mann= 10 ,-1 , 0
  3661.7     .12       0  3925.7    .035       0  4323.8     .07       0
  4560.6    .033       0  4957.4    .033       0  4976.7    .033       0
  5033.1     .12       0  5399.3    .035       0    5536     .12       0
  5582.6    .035       0
Bank Sta=4957.4,4976.7
XS Rating Curve= 0 ,0
Exp/Cntr=0.3,0.1

Type RM Length L Ch R = 1 ,23966   ,467,467,467
BEGIN DESCRIPTION:
Tom Creek 29.0
END DESCRIPTION:
XS GIS Cut Line= 3
      2197032.38     13863160.19        2198575.       13862575.
      2199482.77     13861688.95
#Sta/Elev= 30
  3350.5  1008.7  3395.3 1002.91  3687.4  991.28  3769.5  986.33  3890.1  985.53
  4168.6  962.58    4348   945.6  4480.2  938.94  4590.1  930.44  4675.2  919.11
  4747.8   915.5  4930.2  908.97  5584.7  908.34  5585.2  907.84  5604.1  908.34
  5616.1  908.99  5700.4  914.09  5778.3   936.4  5860.3  946.96  5892.2  954.58
  5912.6  955.38    5955  966.16  5985.6  966.51  6004.6  973.61  6028.9  976.59
  6068.2  980.49  6089.5  988.54  6127.5  992.49  6209.6 1000.35  6268.9 1001.76
#Mann= 14 ,-1 , 0
  3350.5     .12       0  3395.3    .035       0  3687.4    .063       0
  4168.6    .035       0  4747.8     .07       0  4930.2    .033       0
  5584.7    .033       0  5604.1    .033       0  5616.1     .12       0
  5860.3    .063       0  5892.2    .035       0  5985.6    .063       0
  6028.9    .035       0  6127.5     .12       0
Bank Sta=5584.7,5604.1
XS Rating Curve= 0 ,0
Exp/Cntr=0.3,0.1

Type RM Length L Ch R = 1 ,23499   ,1402,1402,1402
BEGIN DESCRIPTION:
Tom Creek 28.0
END DESCRIPTION:
XS GIS Cut Line= 3
      2196629.66     13864174.05        2198975.       13862675.
      2199474.99     13862075.01
#Sta/Elev= 30
  2216.4 1051.54  2226.3 1047.04  2296.4 1042.53  2320.2 1035.81  2377.4 1031.41
  2438.4 1027.36  2537.2 1022.15  2595.9 1012.34  2756.6 1003.87  2856.5  992.81
    3523  969.96  3856.3  953.41  3932.9  945.04  3946.3  942.34  4001.8  930.84
    4267   924.4  4505.5  913.36    4550  911.88  4605.7   909.4  4997.3  908.57
  4997.8  908.07  5016.7  908.57    5326  909.07  5340.3  915.02  5455.7  931.23
  5552.2  939.81  5615.4   946.1  5677.2   954.1  5775.1  966.78  5780.9   967.4
#Mann= 17 ,-1 , 0
  2216.4    .063       0  2296.4    .035       0  2377.4    .063       0
  2438.4    .035       0  3932.9     .12       0  3946.3    .035       0
    4267     .07       0  4505.5    .035       0    4550     .07       0
  4605.7    .033       0  4997.3    .033       0  5016.7    .033       0
  5455.7     .12       0  5552.2    .033       0  5615.4    .035       0
  5677.2    .063       0  5775.1    .035       0
Bank Sta=4997.3,5016.7
XS Rating Curve= 0 ,0
Exp/Cntr=0.3,0.1

Type RM Length L Ch R = 1 ,22097   ,664,664,664
BEGIN DESCRIPTION:
Tom Creek 27.0
END DESCRIPTION:
XS GIS Cut Line= 3
      2198525.04     13863674.99        2198925.       13863525.
      2200024.97     13862325.03
#Sta/Elev= 30
  4573.1  959.75  4626.5  956.91  4643.4  952.78  4668.3  949.18  4703.9     939
  4722.6  931.87  4728.8  926.87  4743.9  923.72  4765.3  923.98    4784   918.5
  4861.4  909.35    4880   908.6  4950.5  908.43    4951  907.93    4970  908.43
    6076  909.24  6104.3  916.13  6118.5  921.33  6179.1  931.79    6232  935.13
  6252.9  940.21  6260.3  939.65  6281.1     942  6309.7  941.61  6352.2  944.01
  6387.4   951.3  6438.8  953.69  6479.2  954.76  6523.5     959  6628.1  962.67
#Mann= 8 ,-1 , 0
  4573.1    .035       0    4880    .033       0  4950.5    .033       0
    4970    .033       0  6179.1     .07       0  6281.1    .035       0
  6438.8    .063       0  6523.5    .035       0
Bank Sta=4950.5,4970
XS Rating Curve= 0 ,0
Exp/Cntr=0.3,0.1

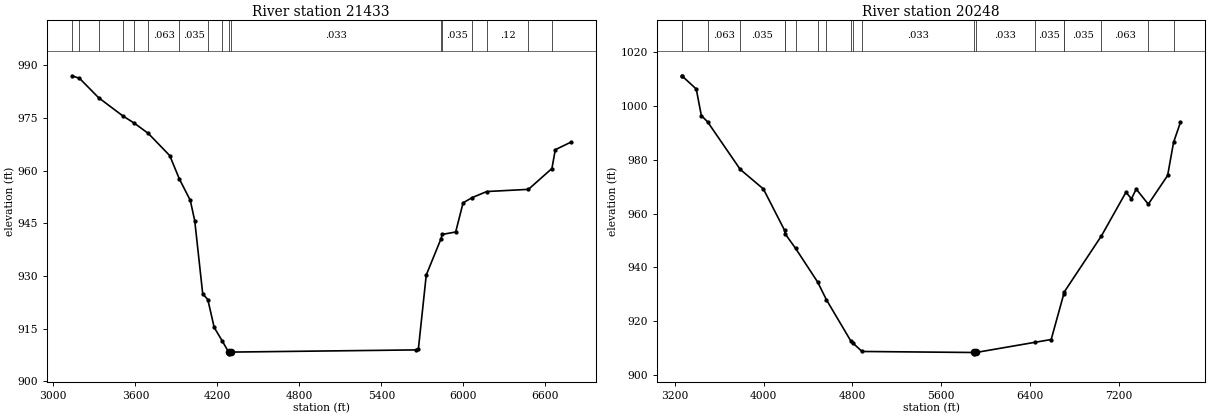
Type RM Length L Ch R = 1 ,21433   ,1185,1185,1185
BEGIN DESCRIPTION:
Tom Creek 26.0
END DESCRIPTION:
XS GIS Cut Line= 3
      2197782.35     13864069.92      2199567.12     13863507.41
      2200372.68     13861924.06
#Sta/Elev= 30
  3135.7  987.05    3191  986.33  3331.4  980.79  3506.1  975.68  3591.8  973.55
  3694.7  970.63  3851.5   964.3  3921.2   957.7  4001.9  951.54  4034.3  945.71
  4092.6  924.92  4129.8  923.32  4176.5  915.36  4234.1   911.6  4282.1  908.35
  4282.6  907.85  4301.6  908.35  5653.9  908.97  5670.5  909.36  5727.8  930.31
  5836.4   940.7  5844.3  941.86  5943.1  942.56  5997.1  950.85  6061.7  952.32
  6170.4  954.08  6475.2   954.7    6647  960.64  6671.6  965.99  6783.5   968.1
#Mann= 17 ,-1 , 0
  3135.7    .035       0    3191    .063       0  3331.4    .035       0
  3506.1    .063       0  3591.8    .035       0  3694.7    .063       0
  3921.2    .035       0  4129.8     .07       0  4234.1    .033       0
  4282.1    .033       0  4301.6    .033       0  5836.4     .12       0
  5844.3    .035       0  6061.7    .063       0  6170.4     .12       0
  6475.2    .035       0    6647    .063       0
Bank Sta=4282.1,4301.6
XS Rating Curve= 0 ,0
Exp/Cntr=0.3,0.1

Type RM Length L Ch R = 1 ,20248   ,0,0,0
BEGIN DESCRIPTION:
Tom Creek 25.0
END DESCRIPTION:
XS GIS Cut Line= 3
      2197206.01     13864403.24        2198925.       13864175.
      2201025.47     13862382.39
#Sta/Elev= 30
  3261.7 1011.19    3265 1011.08  3391.8 1006.27  3437.7   996.4  3493.5   994.1
  3788.4  976.39  3997.1  969.13  4187.6   953.8  4193.5  952.43  4287.4  947.04
    4487  934.48  4564.9  927.98  4786.4  912.56  4802.8  911.91  4886.2  908.73
  5893.3  908.35  5893.8  907.85  5913.2  908.35  6445.5  912.14  6591.6  913.17
  6706.1  930.26  6711.4  930.97  7044.9  951.71  7265.8  967.91  7315.2  965.48
    7358  969.08  7467.1  963.46  7641.2  974.13    7695  986.47  7757.2  993.93
#Mann= 20 ,-1 , 0
  3261.7    .063       0    3265    .035       0  3493.5    .063       0
  3788.4    .035       0  4187.6     .07       0  4193.5    .035       0
  4287.4     .07       0    4487    .035       0  4564.9     .07       0
  4786.4    .033       0  4802.8     .07       0  4886.2    .033       0
  5893.3    .033       0  5913.2    .033       0  6445.5    .035       0
  6706.1     .12       0  6711.4    .035       0  7044.9    .063       0
  7467.1    .035       0    7695     .12       0
Bank Sta=5893.3,5913.2
XS Rating Curve= 0 ,0
Exp/Cntr=0.3,0.1

Chan Stop Cuts=-1
Use User Specified Reach Order=0
Composite Channel Slope=5