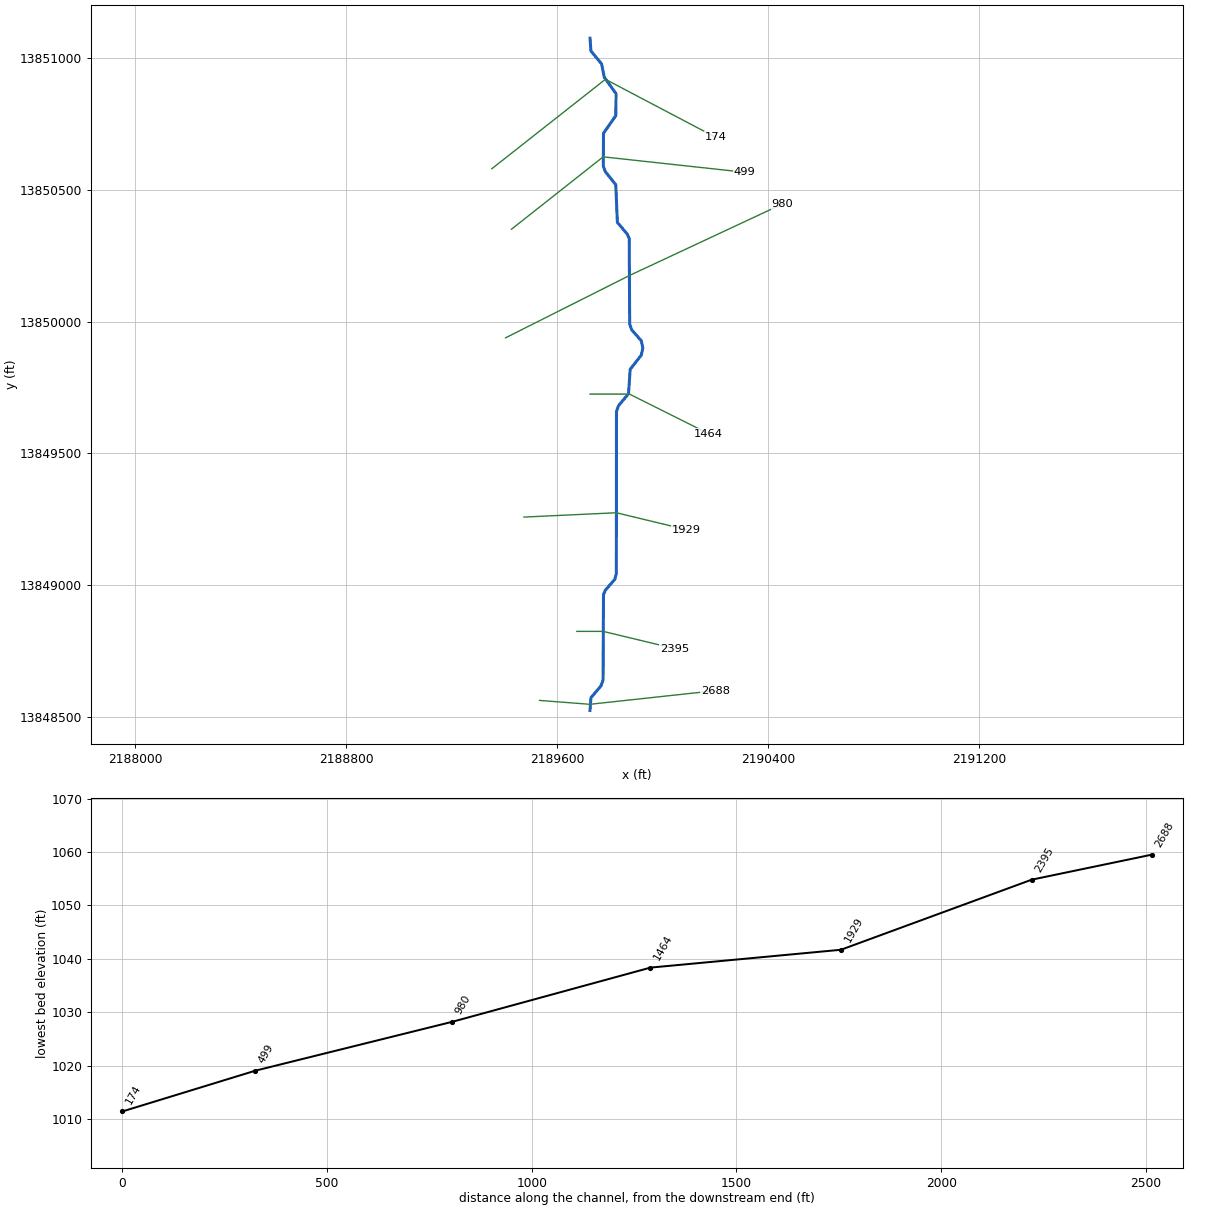
--- Tom Tributary 11.prj (project) ---

Proj Title=Tom Tributary 11 Base Level Engineering
Current Plan=p01
Default Exp/Contr=0.3,0.1
English Units
Geom File=g01
Flow File=f01
Plan File=p01
BEGIN DESCRIPTION:
Tom Tributary 11
END DESCRIPTION:

--- Tom Tributary 11.p01 (plan) ---

Plan Title=Multiple Run
Short Identifier=Multiple
Geom File=g01
Flow File=f01
Subcritical Flow
K Sum by GR= 0
Std Step Tol= 0.01
Critical Tol= 0.01
Num of Std Step Trials= 20
Max Error Tol= 0.3
Flow Tol Ratio= 0.001
Split Flow NTrial= 30
Split Flow Tol= 0.02
Split Flow Ratio= 0.02
Log Output Level= 0
Friction Slope Method= 1
Unsteady Friction Slope Method= 2
Unsteady Bridges Friction Slope Method= 1
Parabolic Critical Depth
Global Vel Dist=  1 , 1 , 1
Global Log Level= 0
CheckData=True
Encroach Param= -1, 0, 0, 0
BEGIN DESCRIPTION:
Multiple Run
END DESCRIPTION:

--- Tom Tributary 11.f01 (steady flow) ---

Flow Title=Multiple
Number of Profiles=7
Profile Names=10-year,25-year,50-year,1pct_min,100-year,1pct_plu,500-year
River Rch & RM= Tom Tributary 11,Reach-1,2688
    1199    2077    2932    2009    4009    7999    7413
River Rch & RM= Tom Tributary 11,Reach-1,2395
    1303    2260    3194    2189    4368    8715    8080
Boundary for River Rch & Prof#=Tom Tributary 11,Reach-1,1
Up Type=0
Dn Type=3
Dn Slope=0.005
Boundary for River Rch & Prof#=Tom Tributary 11,Reach-1,2
Up Type=0
Dn Type=3
Dn Slope=0.005
Boundary for River Rch & Prof#=Tom Tributary 11,Reach-1,3
Up Type=0
Dn Type=3
Dn Slope=0.005
Boundary for River Rch & Prof#=Tom Tributary 11,Reach-1,4
Up Type=0
Dn Type=3
Dn Slope=0.005
Boundary for River Rch & Prof#=Tom Tributary 11,Reach-1,5
Up Type=0
Dn Type=3
Dn Slope=0.005
Boundary for River Rch & Prof#=Tom Tributary 11,Reach-1,6
Up Type=0
Dn Type=3
Dn Slope=0.005
Boundary for River Rch & Prof#=Tom Tributary 11,Reach-1,7
Up Type=0
Dn Type=3
Dn Slope=0.005

--- Tom Tributary 11.g01 (geometry) ---

Geom Title=Existing Conditions

River Reach=Tom Tributary 11,Reach-1
Reach XY= 30
      2189725.00     13848525.00      2189728.65     13848573.49
      2189767.11     13848618.84      2189774.55     13848640.19
      2189776.22     13848964.50      2189783.14     13848981.06
      2189819.25     13849022.67      2189824.93     13849045.03
      2189825.52     13849659.78      2189833.14     13849681.06
      2189871.14     13849726.60      2189877.38     13849819.03
      2189919.63     13849872.82      2189925.40     13849900.00
      2189919.62     13849927.18      2189883.19     13849968.92
      2189875.54     13849990.21      2189873.78     13850314.50
      2189866.86     13850331.06      2189828.79     13850376.57
      2189822.73     13850519.06      2189783.14     13850568.95
      2189775.51     13850590.22      2189776.21     13850714.49
      2189822.83     13850780.98      2189823.92     13850864.46
      2189779.18     13850926.73      2189769.05     13850977.25
      2189728.60     13851026.49      2189725.00     13851075.00

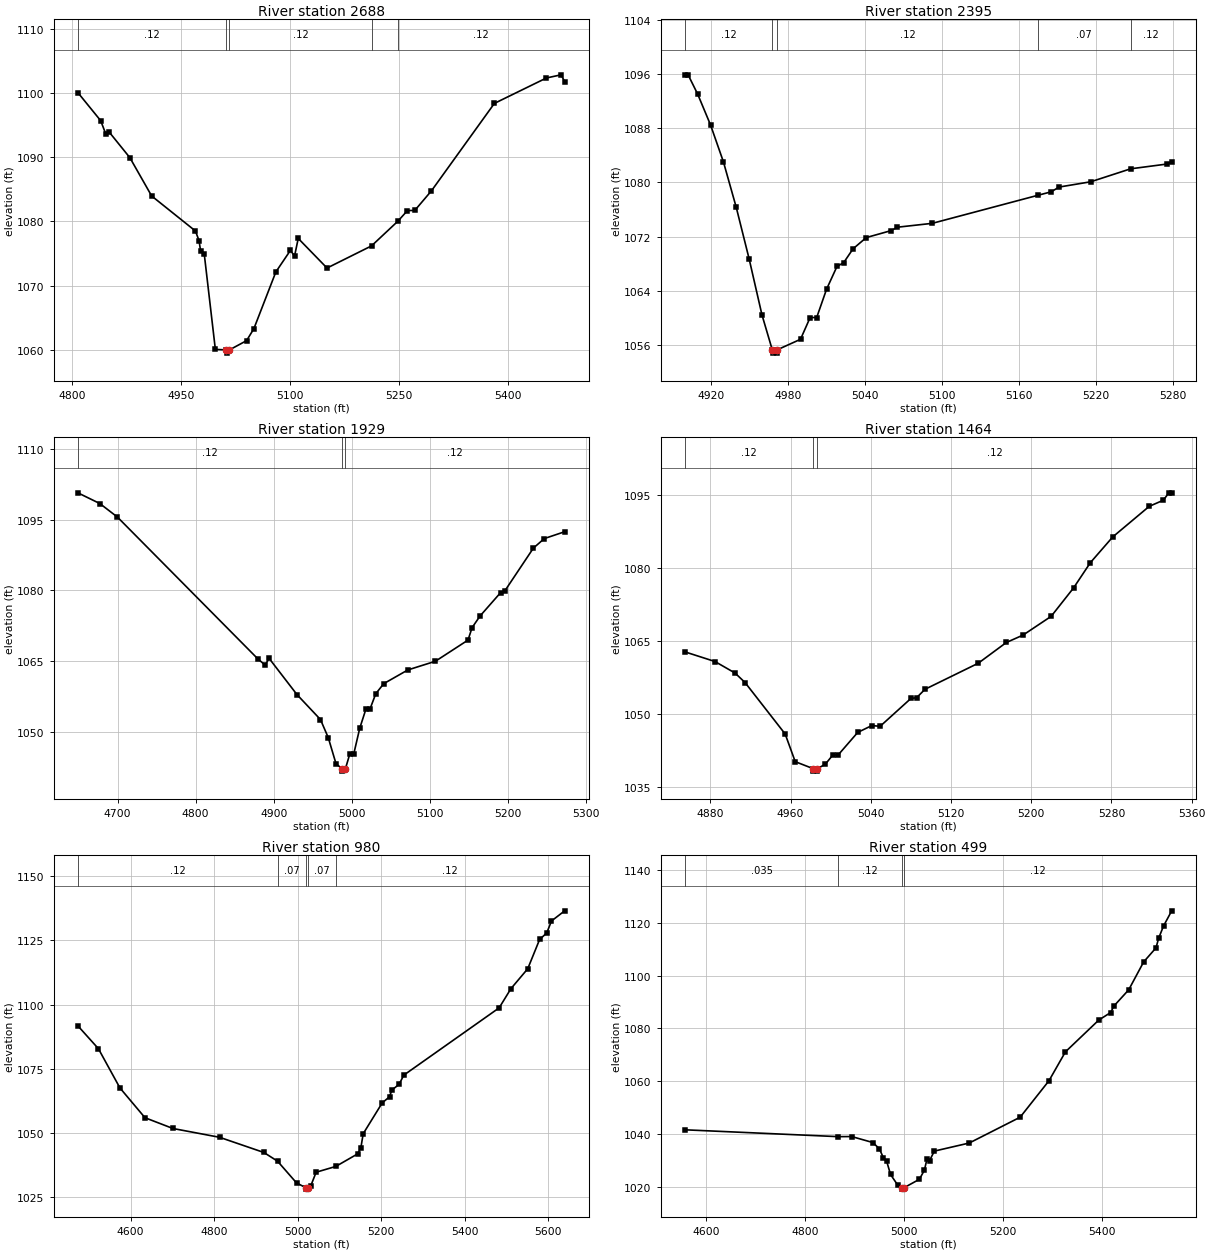
Type RM Length L Ch R = 1,2688,293,293,293
BEGIN DESCRIPTION:
Tom Tributary 11 6.0
END DESCRIPTION:
XS GIS Cut Line= 3
      2189533.76     13848563.10      2189724.50     13848548.42
      2190200.00     13848600.00
#Sta/Elev= 30
  4808.5 1100.07  4839.8 1095.71  4846.9 1093.63  4851.9 1093.88  4880.0 1089.94
  4910.0 1083.97  4970.2 1078.52  4975.2 1077.00  4977.2 1075.48  4982.3 1074.96
  4997.6 1060.08  5012.9 1060.00  5013.2 1059.50  5016.9 1060.00  5040.5 1061.44
  5050.6 1063.31  5080.8 1072.14  5100.9 1075.51  5106.5 1074.60  5111.6 1077.36
  5151.2 1072.75  5212.4 1076.20  5248.7 1080.05  5261.8 1081.70  5271.9 1081.72
  5294.8 1084.77  5381.4 1098.39  5453.0 1102.35  5473.1 1102.84  5478.1 1101.79
#Mann=5,-1,0
  4808.5    0.12       0  5012.9    0.05       0  5016.9    0.12       0
  5212.4    0.07       0  5248.7    0.12       0
Bank Sta=5012.9,5016.9
Exp/Cntr=0.3,0.1

Type RM Length L Ch R = 1,2395,466,466,466
BEGIN DESCRIPTION:
Tom Tributary 11 5.0
END DESCRIPTION:
XS GIS Cut Line= 3
      2189674.99     13848825.00      2189775.00     13848825.00
      2190046.24     13848759.72
#Sta/Elev= 30
  4900.0 1095.86  4902.5 1095.86  4910.0 1092.99  4920.0 1088.45  4930.0 1083.02
  4940.0 1076.30  4950.0 1068.72  4960.0 1060.46  4968.0 1055.32  4968.3 1054.82
  4971.8 1054.82  4972.0 1055.32  4990.0 1056.86  4997.5 1060.07  5002.6 1060.07
  5010.3 1064.25  5018.4 1067.60  5023.6 1068.16  5030.9 1070.20  5041.2 1071.86
  5060.4 1072.88  5065.5 1073.39  5092.6 1073.96  5174.9 1078.10  5185.2 1078.61
  5191.3 1079.31  5216.0 1080.09  5247.0 1082.00  5275.2 1082.70  5279.0 1083.05
#Mann=5,-1,0
  4900.0    0.12       0  4968.0    0.05       0  4972.0    0.12       0
  5174.9    0.07       0  5247.0    0.12       0
Bank Sta=4968,4972
Exp/Cntr=0.3,0.1

Type RM Length L Ch R = 1,1929,465,465,465
BEGIN DESCRIPTION:
Tom Tributary 11 4.0
END DESCRIPTION:
XS GIS Cut Line= 3
      2189474.49     13849258.56      2189825.00     13849275.00
      2190090.38     13849210.93
#Sta/Elev= 30
  4649.1 1100.71  4677.2 1098.44  4699.7 1095.58  4879.9 1065.47  4889.1 1064.18
  4894.1 1065.62  4929.9 1057.92  4960.0 1052.63  4970.0 1048.79  4980.0 1043.22
  4988.0 1042.19  4988.2 1041.69  4992.0 1042.19  4997.5 1045.29  5002.6 1045.29
  5010.3 1050.76  5018.4 1054.92  5023.5 1054.87  5030.9 1058.11  5041.1 1060.24
  5072.0 1063.15  5107.3 1064.99  5149.1 1069.48  5154.3 1072.12  5164.6 1074.60
  5191.0 1079.57  5196.2 1079.89  5232.9 1088.99  5246.9 1091.01  5273.0 1092.46
#Mann=3,-1,0
  4649.1    0.12       0  4988.0    0.05       0  4992.0    0.12       0
Bank Sta=4988,4992
Exp/Cntr=0.3,0.1

Type RM Length L Ch R = 1,1464,484,484,484
BEGIN DESCRIPTION:
Tom Tributary 11 3.0
END DESCRIPTION:
XS GIS Cut Line= 3
      2189725.04     13849725.00      2189875.00     13849725.00
      2190175.03     13849574.98
#Sta/Elev= 30
  4854.7 1062.79  4884.7 1060.81  4904.7 1058.45  4914.7 1056.50  4954.7 1045.95
  4964.7 1040.29  4982.7 1038.85  4982.9 1038.35  4986.4 1038.35  4986.7 1038.85
  4994.7 1039.76  5002.2 1041.66  5007.5 1041.66  5027.0 1046.28  5041.0 1047.68
  5049.4 1047.54  5080.1 1053.25  5085.7 1053.39  5094.1 1055.12  5147.2 1060.46
  5175.2 1064.71  5191.9 1066.23  5219.9 1070.07  5242.2 1075.88  5259.0 1081.07
  5281.4 1086.36  5317.7 1092.61  5331.7 1093.86  5337.3 1095.38  5340.1 1095.38
#Mann=3,-1,0
  4854.7    0.12       0  4982.7    0.05       0  4986.7    0.12       0
Bank Sta=4982.7,4986.7
Exp/Cntr=0.3,0.1

Type RM Length L Ch R = 1,980,481,481,481
BEGIN DESCRIPTION:
Tom Tributary 11 2.0
END DESCRIPTION:
XS GIS Cut Line= 3
      2189405.01     13849938.63      2189875.00     13850175.00
      2190453.88     13850445.63
#Sta/Elev= 30
  4473.9 1091.70  4522.9 1082.84  4574.6 1067.54  4634.5 1055.97  4701.4 1051.78
  4813.0 1048.36  4919.1 1042.45  4951.7 1039.08  4997.2 1030.62  5020.1 1028.70
  5020.3 1028.20  5024.1 1028.70  5031.5 1029.55  5044.1 1034.77  5091.1 1037.02
  5143.5 1041.91  5151.2 1044.30  5156.8 1049.76  5202.4 1061.76  5219.8 1064.12
  5225.3 1066.73  5242.6 1068.93  5253.9 1072.52  5482.1 1098.69  5510.5 1106.19
  5550.6 1113.91  5579.0 1125.29  5596.1 1127.83  5607.4 1132.48  5639.0 1136.43
#Mann=5,-1,0
  4473.9    0.12       0  4951.7    0.07       0  5020.1    0.05       0
  5024.1    0.07       0  5091.1    0.12       0
Bank Sta=5020.1,5024.1
Exp/Cntr=0.3,0.1

Type RM Length L Ch R = 1,499,325,325,325
BEGIN DESCRIPTION:
Tom Tributary 11 1.0
END DESCRIPTION:
XS GIS Cut Line= 3
      2189427.15     13850350.41      2189775.00     13850625.00
      2190311.25     13850566.53
#Sta/Elev= 30
  4557.4 1041.55  4867.1 1038.95  4894.0 1038.99  4936.9 1036.71  4950.0 1034.32
  4958.1 1030.90  4964.5 1029.72  4972.5 1024.59  4987.0 1020.55  4995.4 1019.54
  4995.6 1019.04  4999.4 1019.54  5030.7 1022.77  5040.8 1026.23  5046.3 1030.66
  5051.3 1029.89  5060.9 1033.47  5131.3 1036.53  5234.1 1046.33  5292.3 1060.17
  5325.5 1071.13  5392.9 1083.20  5416.9 1086.05  5423.1 1088.46  5453.2 1094.66
  5483.4 1105.25  5508.3 1110.58  5513.6 1114.22  5523.6 1118.91  5540.0 1124.63
#Mann=4,-1,0
  4557.4   0.035       0  4867.1    0.12       0  4995.4    0.05       0
  4999.4    0.12       0
Bank Sta=4995.4,4999.4
Exp/Cntr=0.3,0.1

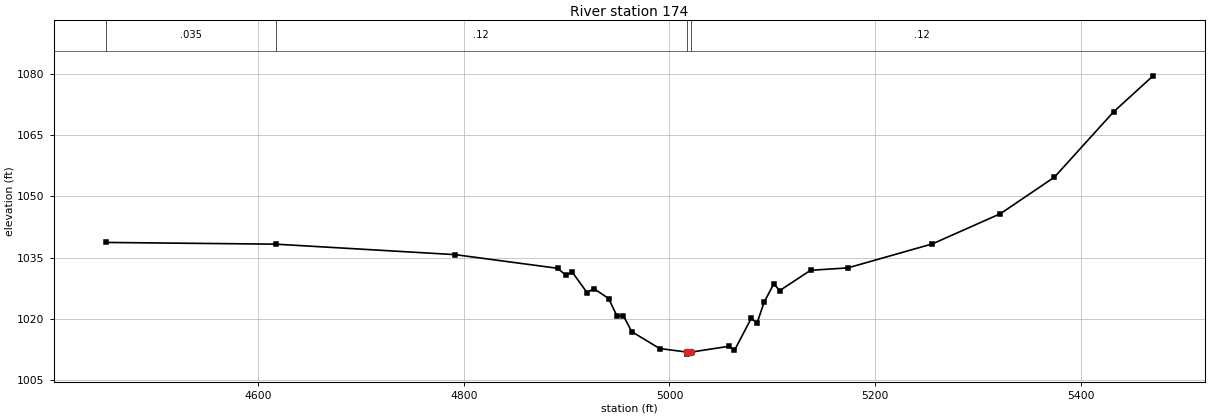
Type RM Length L Ch R = 1,174,0,0,0
BEGIN DESCRIPTION:
Tom Tributary 11 0.1
END DESCRIPTION:
XS GIS Cut Line= 3
      2189352.59     13850579.83      2189783.47     13850919.08
      2190199.97     13850700.01
#Sta/Elev= 30
  4451.6 1038.75  4616.8 1038.33  4791.6 1035.76  4891.1 1032.42  4899.1 1030.76
  4905.5 1031.46  4919.9 1026.43  4926.3 1027.46  4940.8 1025.02  4948.8 1020.79
  4955.2 1020.78  4963.3 1016.90  4990.5 1012.77  5017.1 1011.90  5017.3 1011.40
  5021.1 1011.90  5057.5 1013.30  5063.2 1012.29  5079.6 1020.18  5085.2 1018.97
  5092.1 1024.09  5101.6 1028.67  5107.2 1026.94  5137.3 1031.93  5173.4 1032.51
  5255.9 1038.40  5322.0 1045.78  5374.6 1054.73  5432.2 1070.73  5470.6 1079.55
#Mann=4,-1,0
  4451.6   0.035       0  4616.8    0.12       0  5017.1    0.05       0
  5021.1    0.12       0
Bank Sta=5017.1,5021.1
Exp/Cntr=0.3,0.1

Chan Stop Cuts=-1