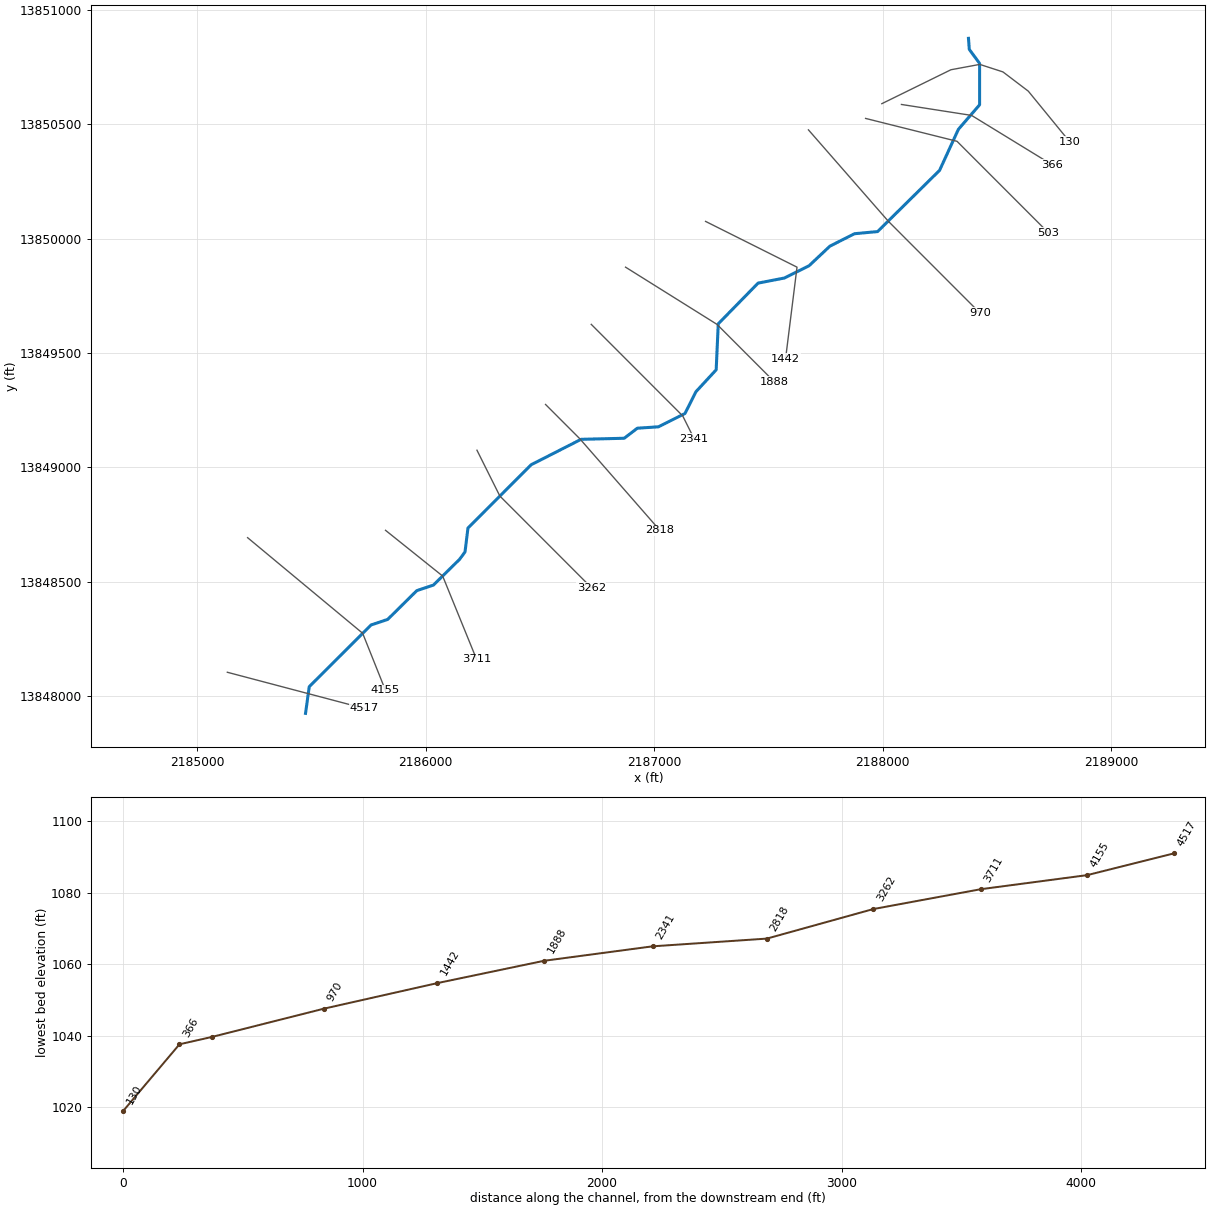
--- Tom Tributary 12.prj (project) ---

Proj Title=Tom Tributary 12 Base Level Engineering
Current Plan=p01
Default Exp/Contr=0.3,0.1
English Units
Geom File=g01
Flow File=f01
Plan File=p01
BEGIN DESCRIPTION:
Tom Tributary 12
END DESCRIPTION:

--- Tom Tributary 12.p01 (plan) ---

Plan Title=Multiple Run
Short Identifier=Multiple
Geom File=g01
Flow File=f01
Subcritical Flow
K Sum by GR= 0
Std Step Tol= 0.01
Critical Tol= 0.01
Num of Std Step Trials= 20
Max Error Tol= 0.3
Flow Tol Ratio= 0.001
Split Flow NTrial= 30
Split Flow Tol= 0.02
Split Flow Ratio= 0.02
Log Output Level= 0
Friction Slope Method= 1
Unsteady Friction Slope Method= 2
Unsteady Bridges Friction Slope Method= 1
Parabolic Critical Depth
Global Vel Dist=  1 , 1 , 1
Global Log Level= 0
CheckData=True
Encroach Param= -1, 0, 0, 0
BEGIN DESCRIPTION:
Multiple Run
END DESCRIPTION:

--- Tom Tributary 12.f01 (steady flow) ---

Flow Title=Multiple
Number of Profiles=7
Profile Names=10-year,25-year,50-year,1pct_min,100-year,1pct_plu,500-year
River Rch & RM= Tom Tributary 12,Reach-1,4517
    1177    2008    2804    1897    3785    7552    6825
River Rch & RM= Tom Tributary 12,Reach-1,2818
    1348    2316    3248    2206    4402    8783    8001
Boundary for River Rch & Prof#=Tom Tributary 12,Reach-1,1
Up Type=0
Dn Type=3
Dn Slope=0.005
Boundary for River Rch & Prof#=Tom Tributary 12,Reach-1,2
Up Type=0
Dn Type=3
Dn Slope=0.005
Boundary for River Rch & Prof#=Tom Tributary 12,Reach-1,3
Up Type=0
Dn Type=3
Dn Slope=0.005
Boundary for River Rch & Prof#=Tom Tributary 12,Reach-1,4
Up Type=0
Dn Type=3
Dn Slope=0.005
Boundary for River Rch & Prof#=Tom Tributary 12,Reach-1,5
Up Type=0
Dn Type=3
Dn Slope=0.005
Boundary for River Rch & Prof#=Tom Tributary 12,Reach-1,6
Up Type=0
Dn Type=3
Dn Slope=0.005
Boundary for River Rch & Prof#=Tom Tributary 12,Reach-1,7
Up Type=0
Dn Type=3
Dn Slope=0.005

--- Tom Tributary 12.g01 (geometry) ---

Geom Title=Existing Conditions

River Reach=Tom Tributary 12,Reach-1
Reach XY= 30
      2185475.00     13847925.00      2185491.43     13848041.76
      2185761.79     13848311.37      2185834.68     13848335.78
      2185961.79     13848461.37      2186034.68     13848485.78
      2186148.82     13848598.13      2186172.74     13848630.48
      2186185.52     13848734.79      2186461.79     13849011.38
      2186680.52     13849122.65      2186869.06     13849127.26
      2186926.60     13849171.14      2187019.04     13849177.33
      2187135.00     13849235.63      2187183.19     13849331.02
      2187271.45     13849426.47      2187280.46     13849627.45
      2187454.84     13849805.37      2187569.03     13849827.33
      2187677.29     13849880.84      2187768.95     13849966.84
      2187876.59     13850021.17      2187977.43     13850030.52
      2188248.71     13850298.18      2188330.85     13850477.29
      2188423.79     13850584.59      2188423.73     13850765.38
      2188378.65     13850826.51      2188375.00     13850875.00

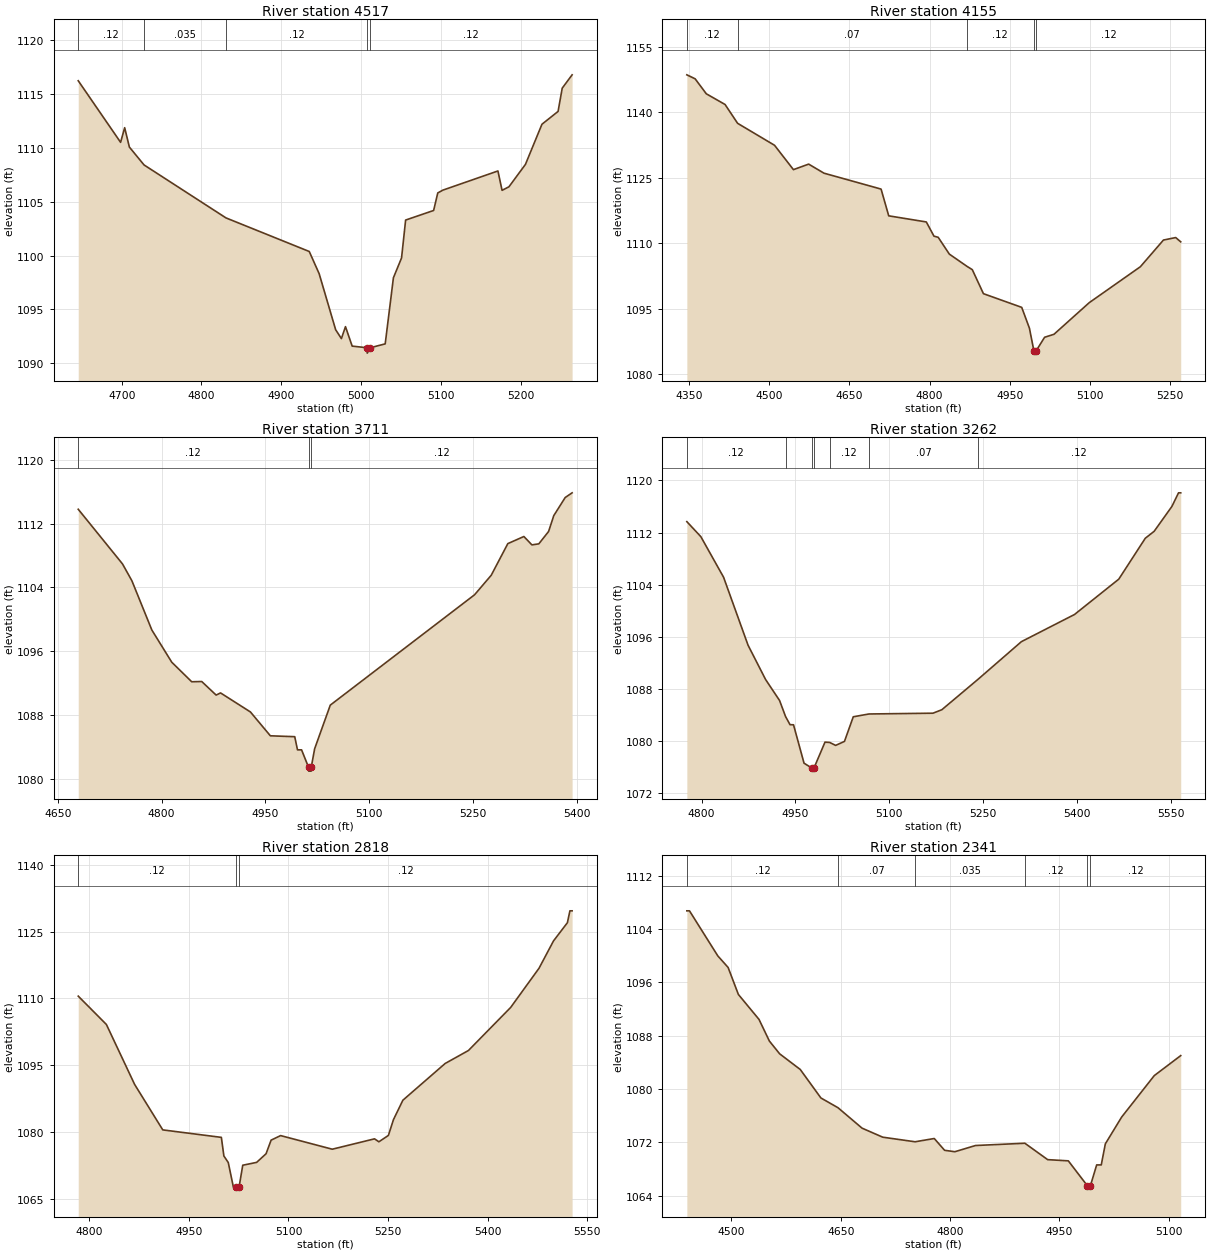
Type RM Length L Ch R = 1,4517,362,362,362
BEGIN DESCRIPTION:
Tom Tributary 12 10.0
END DESCRIPTION:
XS GIS Cut Line= 2
      2185132.98     13848104.68      2185731.59     13847946.71
#Sta/Elev= 30
  4645.5 1116.24  4698.6 1110.52  4703.7 1111.88  4709.6 1110.08  4728.0 1108.42
  4830.7 1103.50  4935.1 1100.38  4947.5 1098.32  4968.2 1093.11  4975.4 1092.29
  4980.5 1093.40  4988.9 1091.59  5007.6 1091.44  5007.8 1090.94  5011.6 1091.44
  5030.3 1091.80  5040.6 1097.94  5050.8 1099.78  5055.9 1103.30  5091.0 1104.19
  5096.2 1105.82  5102.6 1106.08  5171.6 1107.86  5176.8 1106.06  5185.4 1106.39
  5206.1 1108.47  5226.8 1112.20  5247.0 1113.39  5252.2 1115.55  5264.6 1116.79
#Mann=5,-1,0
  4645.5    0.12       0  4728.0   0.035       0  4830.7    0.12       0
  5007.6    0.05       0  5011.6    0.12       0
Bank Sta=5007.6,5011.6
Exp/Cntr=0.3,0.1

Type RM Length L Ch R = 1,4155,444,444,444
BEGIN DESCRIPTION:
Tom Tributary 12 9.0
END DESCRIPTION:
XS GIS Cut Line= 3
      2185221.64     13848692.89      2185725.00     13848275.00
      2185825.01     13848024.98
#Sta/Elev= 30
  4346.0 1148.54  4361.5 1147.63  4382.4 1144.20  4417.5 1141.75  4440.9 1137.45
  4510.0 1132.42  4545.3 1126.85  4573.8 1128.11  4602.4 1126.04  4709.2 1122.40
  4723.5 1116.28  4793.8 1114.88  4808.1 1111.63  4816.0 1111.37  4836.8 1107.53
  4869.5 1104.75  4879.8 1103.96  4900.6 1098.47  4972.2 1095.34  4986.6 1090.57
  4995.0 1085.37  4995.2 1084.87  4999.0 1085.37  5015.0 1088.50  5032.5 1089.18
  5098.5 1096.42  5194.1 1104.64  5237.2 1110.74  5260.1 1111.31  5269.5 1110.33
#Mann=5,-1,0
  4346.0    0.12       0  4440.9    0.07       0  4869.5    0.12       0
  4995.0    0.05       0  4999.0    0.12       0
Bank Sta=4995,4999
Exp/Cntr=0.3,0.1

Type RM Length L Ch R = 1,3711,449,449,449
BEGIN DESCRIPTION:
Tom Tributary 12 8.0
END DESCRIPTION:
XS GIS Cut Line= 3
      2185825.02     13848724.98      2186075.00     13848525.00
      2186223.66     13848160.47
#Sta/Elev= 30
  4679.6 1113.79  4743.6 1106.93  4757.2 1104.81  4786.0 1098.64  4814.8 1094.60
  4843.6 1092.15  4858.1 1092.18  4878.9 1090.48  4885.3 1090.75  4928.5 1088.36
  4957.3 1085.37  4992.5 1085.26  4996.5 1083.61  5002.4 1083.61  5012.4 1081.44
  5012.7 1080.94  5016.2 1080.94  5016.4 1081.44  5021.3 1083.75  5043.9 1089.22
  5252.4 1103.06  5276.5 1105.51  5300.5 1109.48  5323.7 1110.37  5335.3 1109.32
  5345.3 1109.45  5359.4 1111.00  5366.9 1112.99  5383.4 1115.26  5393.4 1115.85
#Mann=3,-1,0
  4679.6    0.12       0  5012.4    0.05       0  5016.4    0.12       0
Bank Sta=5012.4,5016.4
Exp/Cntr=0.3,0.1

Type RM Length L Ch R = 1,3262,444,444,444
BEGIN DESCRIPTION:
Tom Tributary 12 7.0
END DESCRIPTION:
XS GIS Cut Line= 3
      2186224.99     13849075.01      2186325.00     13848875.00
      2186725.00     13848475.00
#Sta/Elev= 30
  4776.4 1113.68  4798.8 1111.37  4835.1 1105.15  4874.2 1094.72  4902.2 1089.46
  4924.6 1086.23  4934.2 1083.76  4941.3 1082.52  4946.9 1082.50  4963.7 1076.61
  4975.7 1075.89  4975.9 1075.39  4979.7 1075.89  4997.2 1079.84  5004.7 1079.79
  5014.2 1079.34  5028.3 1079.95  5042.4 1083.73  5067.4 1084.16  5169.7 1084.28
  5183.9 1084.81  5241.5 1089.46  5311.1 1095.26  5396.0 1099.43  5466.7 1104.85
  5509.1 1111.13  5523.3 1112.20  5551.6 1116.01  5562.2 1118.10  5565.7 1118.10
#Mann=7,-1,0
  4776.4    0.12       0  4934.2    0.07       0  4975.7    0.05       0
  4979.7    0.07       0  5004.7    0.12       0  5067.4    0.07       0
  5241.5    0.12       0
Bank Sta=4975.7,4979.7
Exp/Cntr=0.3,0.1

Type RM Length L Ch R = 1,2818,477,477,477
BEGIN DESCRIPTION:
Tom Tributary 12 6.0
END DESCRIPTION:
XS GIS Cut Line= 3
      2186525.00     13849275.00      2186675.00     13849125.00
      2187024.97     13848725.03
#Sta/Elev= 30
  4783.5 1110.51  4825.9 1104.14  4868.4 1090.67  4910.8 1080.45  4999.0 1078.77
  5002.8 1074.58  5009.4 1073.12  5017.0 1067.67  5021.6 1067.64  5021.8 1067.14
  5025.7 1067.64  5031.2 1072.51  5052.1 1073.15  5066.3 1075.09  5073.9 1078.15
  5088.2 1079.17  5166.0 1076.11  5229.6 1078.44  5236.2 1077.78  5250.5 1079.21
  5258.1 1082.75  5272.3 1087.12  5335.9 1095.37  5371.0 1098.29  5434.6 1107.97
  5477.3 1116.78  5499.1 1122.92  5520.0 1127.01  5523.8 1129.68  5527.1 1129.68
#Mann=3,-1,0
  4783.5    0.12       0  5021.6    0.05       0  5025.7    0.12       0
Bank Sta=5021.6,5025.7
Exp/Cntr=0.3,0.1

Type RM Length L Ch R = 1,2341,453,453,453
BEGIN DESCRIPTION:
Tom Tributary 12 5.0
END DESCRIPTION:
XS GIS Cut Line= 3
      2186724.98     13849625.02      2187125.00     13849225.00
      2187174.99     13849125.01
#Sta/Elev= 30
  4438.9 1106.71  4442.5 1106.71  4481.4 1099.95  4495.5 1098.22  4509.6 1094.17
  4537.9 1090.43  4552.1 1087.19  4566.2 1085.27  4594.5 1082.92  4622.8 1078.65
  4646.2 1077.19  4679.3 1074.12  4707.6 1072.77  4752.0 1072.08  4778.3 1072.57
  4792.5 1070.80  4806.6 1070.59  4834.9 1071.52  4902.6 1071.86  4933.9 1069.40
  4962.2 1069.22  4988.4 1065.48  4988.7 1064.98  4992.5 1065.48  5001.1 1068.61
  5007.4 1068.61  5013.0 1071.77  5035.4 1075.79  5080.1 1082.00  5116.4 1085.00
#Mann=6,-1,0
  4438.9    0.12       0  4646.2    0.07       0  4752.0   0.035       0
  4902.6    0.12       0  4988.4    0.05       0  4992.5    0.12       0
Bank Sta=4988.4,4992.5
Exp/Cntr=0.3,0.1

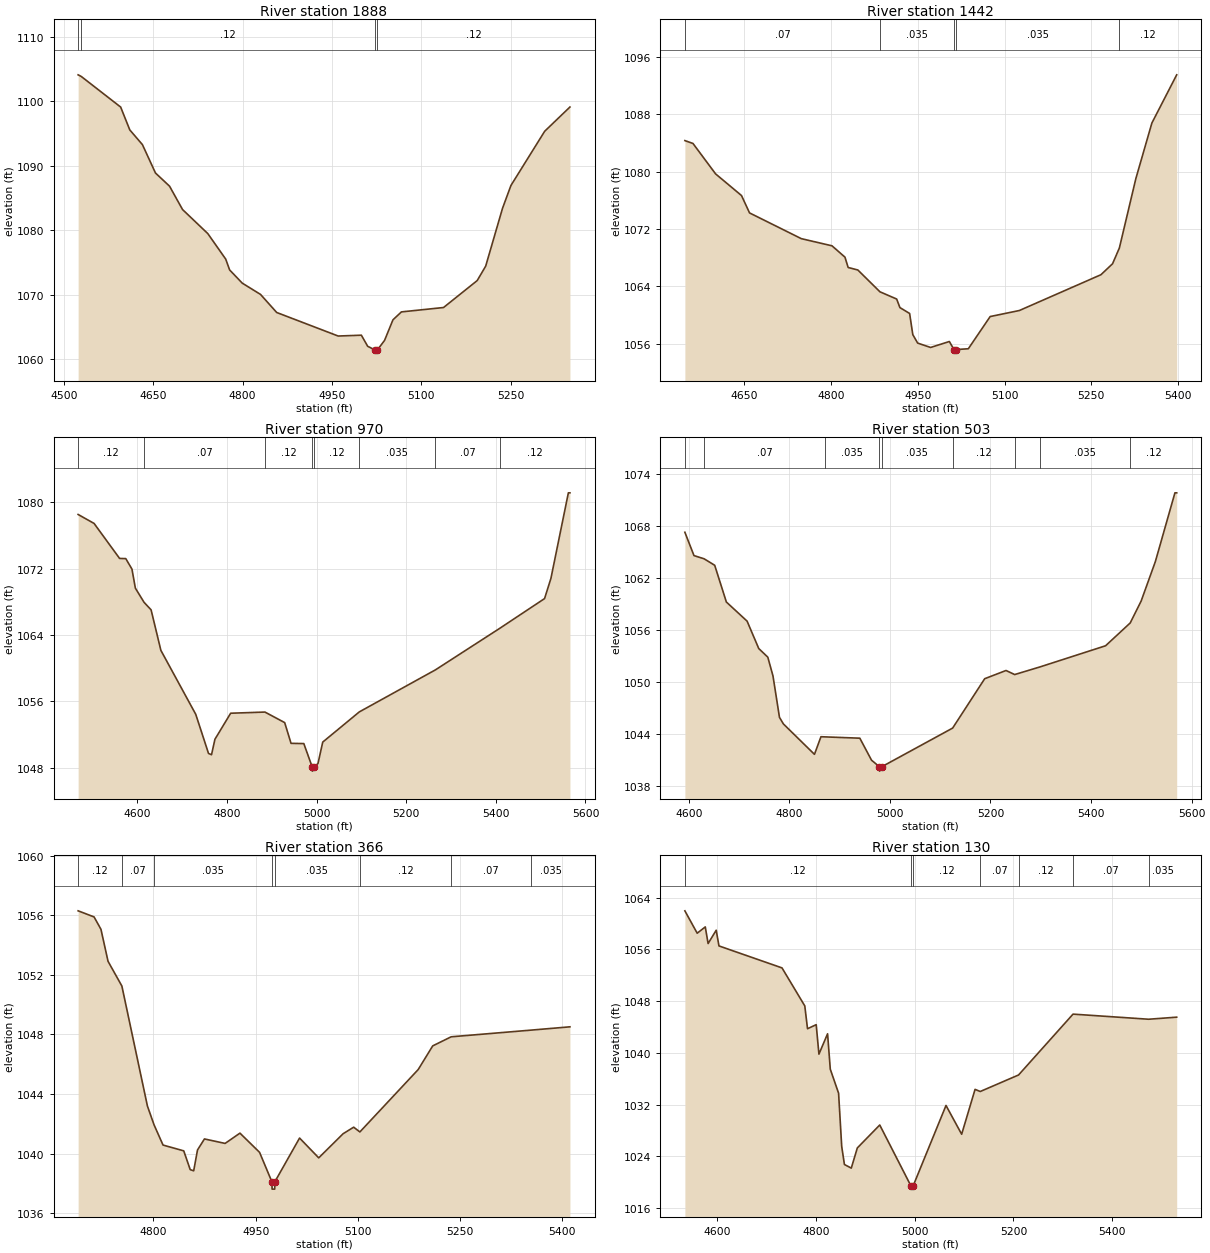
Type RM Length L Ch R = 1,1888,446,446,446
BEGIN DESCRIPTION:
Tom Tributary 12 4.0
END DESCRIPTION:
XS GIS Cut Line= 3
      2186874.96     13849875.03      2187275.00     13849625.00
      2187525.00     13849375.00
#Sta/Elev= 30
  4524.0 1104.08  4529.2 1103.83  4595.4 1099.08  4610.7 1095.54  4631.9 1093.26
  4653.8 1088.86  4677.4 1086.82  4699.2 1083.20  4741.6 1079.47  4771.7 1075.51
  4778.2 1073.84  4799.4 1071.79  4830.1 1070.04  4857.2 1067.24  4960.4 1063.59
  4999.3 1063.72  5009.9 1062.00  5021.9 1061.44  5022.2 1060.94  5026.2 1061.44
  5038.2 1062.91  5052.3 1066.10  5066.5 1067.33  5137.2 1068.01  5193.7 1072.19
  5207.9 1074.42  5236.2 1083.40  5250.3 1086.93  5306.9 1095.33  5349.3 1099.09
#Mann=4,-1,0
  4524.0    0.07       0  4529.2    0.12       0  5021.9    0.05       0
  5026.2    0.12       0
Bank Sta=5021.9,5026.2
Exp/Cntr=0.3,0.1

Type RM Length L Ch R = 1,1442,472,472,472
BEGIN DESCRIPTION:
Tom Tributary 12 3.0
END DESCRIPTION:
XS GIS Cut Line= 3
      2187224.96     13850075.02      2187625.00     13849875.00
      2187575.00     13849474.97
#Sta/Elev= 30
  4547.3 1084.33  4561.3 1083.93  4600.4 1079.69  4645.2 1076.67  4659.1 1074.25
  4748.6 1070.66  4801.7 1069.66  4824.1 1068.08  4829.6 1066.64  4846.4 1066.29
  4884.6 1063.25  4913.5 1062.24  4919.1 1061.05  4935.9 1060.23  4941.4 1057.28
  4949.8 1056.10  4972.2 1055.49  5004.6 1056.32  5012.6 1055.20  5012.9 1054.70
  5016.9 1055.20  5037.4 1055.31  5075.2 1059.80  5125.6 1060.64  5266.7 1065.63
  5286.8 1067.16  5298.6 1069.36  5327.1 1079.04  5354.8 1086.78  5397.7 1093.50
#Mann=5,-1,0
  4547.3    0.07       0  4884.6   0.035       0  5012.6   0.035       0
  5016.9   0.035       0  5298.6    0.12       0
Bank Sta=5012.6,5016.9
Exp/Cntr=0.3,0.1

Type RM Length L Ch R = 1,970,467,467,467
BEGIN DESCRIPTION:
Tom Tributary 12 2.0
END DESCRIPTION:
XS GIS Cut Line= 3
      2187674.99     13850475.01      2188025.00     13850075.00
      2188425.00     13849675.00
#Sta/Elev= 30
  4468.2 1078.52  4503.8 1077.44  4560.7 1073.22  4574.5 1073.20  4588.3 1071.93
  4595.9 1069.64  4615.3 1067.93  4631.0 1067.02  4652.8 1062.14  4730.6 1054.43
  4759.1 1049.71  4765.8 1049.56  4773.4 1051.42  4808.5 1054.56  4885.0 1054.70
  4929.0 1053.43  4943.2 1050.93  4971.7 1050.90  4990.4 1048.08  4990.7 1047.58
  4994.7 1048.08  5003.3 1048.50  5013.9 1051.08  5095.5 1054.72  5265.1 1059.78
  5408.7 1064.79  5508.8 1068.38  5523.0 1070.82  5561.9 1081.13  5565.4 1081.13
#Mann=8,-1,0
  4468.2    0.12       0  4615.3    0.07       0  4885.0    0.12       0
  4990.4    0.05       0  4994.7    0.12       0  5095.5   0.035       0
  5265.1    0.07       0  5408.7    0.12       0
Bank Sta=4990.4,4994.7
Exp/Cntr=0.3,0.1

Type RM Length L Ch R = 1,503,137,137,137
BEGIN DESCRIPTION:
Tom Tributary 12 1.0
END DESCRIPTION:
XS GIS Cut Line= 3
      2187924.99     13850525.00      2188325.00     13850425.00
      2188724.99     13850025.01
#Sta/Elev= 30
  4592.3 1067.32  4610.4 1064.62  4630.5 1064.25  4651.6 1063.50  4674.8 1059.25
  4716.0 1057.04  4739.2 1053.87  4757.2 1052.87  4767.5 1050.70  4780.4 1045.91
  4788.2 1045.15  4850.0 1041.63  4862.9 1043.67  4871.0 1043.65  4940.2 1043.50
  4963.4 1040.96  4979.2 1040.19  4979.5 1039.69  4983.6 1040.19  5124.8 1044.67
  5188.5 1050.38  5230.9 1051.33  5248.1 1050.86  5298.3 1051.74  5428.9 1054.19
  5477.9 1056.83  5499.6 1059.36  5527.9 1063.93  5566.8 1071.88  5570.3 1071.88
#Mann=9,-1,0
  4592.3    0.12       0  4630.5    0.07       0  4871.0   0.035       0
  4979.2   0.035       0  4983.6   0.035       0  5124.8    0.12       0
  5248.1    0.07       0  5298.3   0.035       0  5477.9    0.12       0
Bank Sta=4979.2,4983.6
Exp/Cntr=0.3,0.1

Type RM Length L Ch R = 1,366,236,236,236
BEGIN DESCRIPTION:
Tom Tributary 12 0.1
END DESCRIPTION:
XS GIS Cut Line= 3
      2188081.85     13850586.01      2188388.65     13850538.20
      2188739.45     13850323.48
#Sta/Elev= 30
  4689.5 1056.30  4712.9 1055.89  4723.0 1055.06  4733.4 1052.91  4753.7 1051.25
  4791.2 1043.19  4801.0 1041.92  4814.1 1040.57  4844.5 1040.18  4854.0 1038.92
  4859.1 1038.84  4864.7 1040.24  4874.9 1040.98  4905.2 1040.68  4927.0 1041.37
  4955.8 1040.08  4973.8 1038.11  4974.2 1037.61  4978.0 1037.61  4978.3 1038.11
  5014.5 1041.04  5042.6 1039.71  5078.4 1041.33  5093.9 1041.77  5103.0 1041.45
  5188.6 1045.64  5209.9 1047.23  5237.0 1047.84  5354.7 1048.29  5411.3 1048.51
#Mann=8,-1,0
  4689.5    0.12       0  4753.7    0.07       0  4801.0   0.035       0
  4973.8   0.035       0  4978.3   0.035       0  5103.0    0.12       0
  5237.0    0.07       0  5354.7   0.035       0
Bank Sta=4973.8,4978.3
Exp/Cntr=0.3,0.1

Type RM Length L Ch R = 1,130,0,0,0
BEGIN DESCRIPTION:
Tom Tributary 12 0.0
END DESCRIPTION:
XS GIS Cut Line= 6
      2187996.09     13850589.44      2188298.30     13850737.72
      2188424.40     13850761.11      2188525.86     13850728.25
      2188636.71     13850644.19      2188817.00     13850423.94
#Sta/Elev= 30
  4535.0 1061.96  4559.9 1058.50  4576.3 1059.47  4582.0 1056.90  4598.4 1058.96
  4604.0 1056.53  4731.6 1053.13  4777.7 1047.25  4783.2 1043.72  4800.8 1044.35
  4806.3 1039.79  4823.8 1042.94  4829.3 1037.46  4846.1 1033.75  4852.4 1025.52
  4857.9 1022.72  4871.8 1022.16  4884.0 1025.28  4929.4 1028.83  4992.5 1019.41
  4992.8 1018.91  4997.0 1019.41  5063.5 1031.85  5095.2 1027.40  5122.3 1034.34
  5132.8 1034.01  5210.4 1036.57  5320.6 1045.98  5473.6 1045.19  5530.4 1045.51
#Mann=7,-1,0
  4535.0    0.12       0  4992.5    0.05       0  4997.0    0.12       0
  5132.8    0.07       0  5210.4    0.12       0  5320.6    0.07       0
  5473.6   0.035       0
Bank Sta=4992.5,4997
Exp/Cntr=0.3,0.1

Chan Stop Cuts=-1