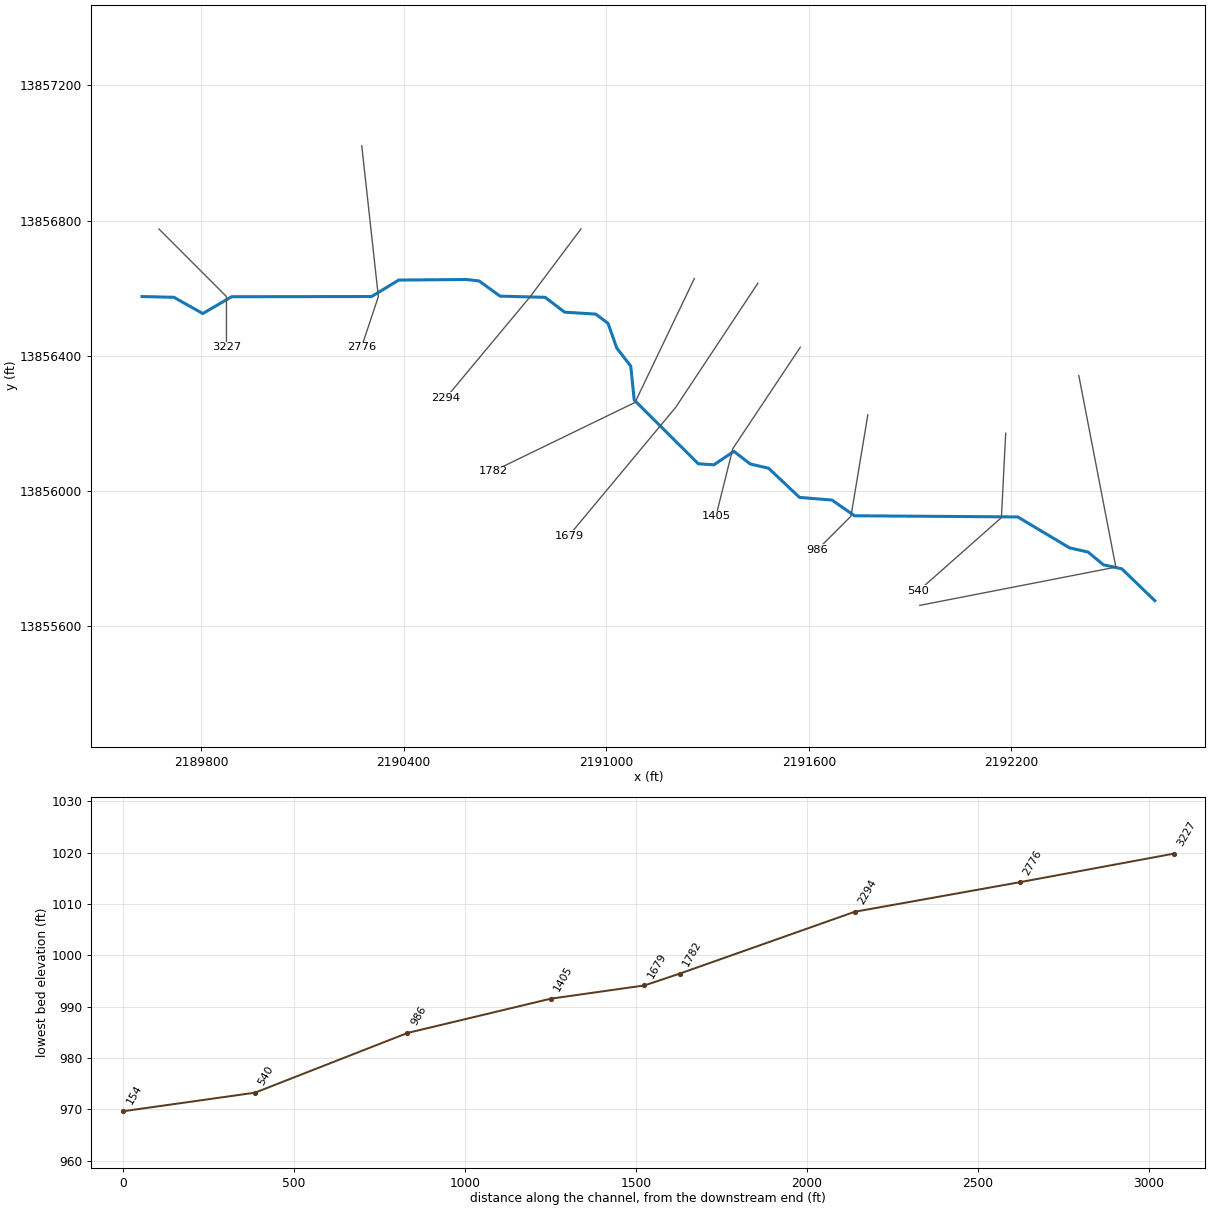
--- Tom Tributary 9.prj (project) ---

Proj Title=Tom Tributary 9 Base Level Engineering
Current Plan=p01
Default Exp/Contr=0.3,0.1
English Units
Geom File=g01
Flow File=f01
Plan File=p01
BEGIN DESCRIPTION:
Tom Tributary 9
END DESCRIPTION:

--- Tom Tributary 9.p01 (plan) ---

Plan Title=Multiple Run
Short Identifier=Multiple
Geom File=g01
Flow File=f01
Subcritical Flow
K Sum by GR= 0
Std Step Tol= 0.01
Critical Tol= 0.01
Num of Std Step Trials= 20
Max Error Tol= 0.3
Flow Tol Ratio= 0.001
Split Flow NTrial= 30
Split Flow Tol= 0.02
Split Flow Ratio= 0.02
Log Output Level= 0
Friction Slope Method= 1
Unsteady Friction Slope Method= 2
Unsteady Bridges Friction Slope Method= 1
Parabolic Critical Depth
Global Vel Dist=  1 , 1 , 1
Global Log Level= 0
CheckData=True
Encroach Param= -1, 0, 0, 0
BEGIN DESCRIPTION:
Multiple Run
END DESCRIPTION:

--- Tom Tributary 9.f01 (steady flow) ---

Flow Title=Multiple
Number of Profiles=7
Profile Names=10-year,25-year,50-year,1pct_min,100-year,1pct_plu,500-year
River Rch & RM= Tom Tributary 9,Reach-1,3227
    1033    1753    2439    1646    3284    6552    5887
Boundary for River Rch & Prof#=Tom Tributary 9,Reach-1,1
Up Type=0
Dn Type=3
Dn Slope=0.005
Boundary for River Rch & Prof#=Tom Tributary 9,Reach-1,2
Up Type=0
Dn Type=3
Dn Slope=0.005
Boundary for River Rch & Prof#=Tom Tributary 9,Reach-1,3
Up Type=0
Dn Type=3
Dn Slope=0.005
Boundary for River Rch & Prof#=Tom Tributary 9,Reach-1,4
Up Type=0
Dn Type=3
Dn Slope=0.005
Boundary for River Rch & Prof#=Tom Tributary 9,Reach-1,5
Up Type=0
Dn Type=3
Dn Slope=0.005
Boundary for River Rch & Prof#=Tom Tributary 9,Reach-1,6
Up Type=0
Dn Type=3
Dn Slope=0.005
Boundary for River Rch & Prof#=Tom Tributary 9,Reach-1,7
Up Type=0
Dn Type=3
Dn Slope=0.005

--- Tom Tributary 9.g01 (geometry) ---

Geom Title=Existing Conditions

River Reach=Tom Tributary 9,Reach-1
Reach XY= 30
      2189625.00     13856575.00      2189719.14     13856572.87
      2189804.82     13856524.71      2189890.21     13856574.46
      2190304.97     13856575.07      2190385.50     13856623.78
      2190585.19     13856625.45      2190623.43     13856621.22
      2190685.51     13856576.23      2190819.06     13856572.73
      2190876.60     13856528.86      2190969.29     13856522.93
      2191005.42     13856495.57      2191031.15     13856422.85
      2191072.67     13856369.03      2191082.86     13856268.83
      2191272.71     13856080.11      2191318.95     13856076.98
      2191378.31     13856116.93      2191426.65     13856079.45
      2191481.04     13856066.86      2191572.58     13855980.54
      2191669.02     13855972.64      2191735.50     13855926.22
      2192219.07     13855922.76      2192372.80     13855831.08
      2192427.20     13855818.92      2192472.81     13855781.10
      2192527.32     13855769.21      2192625.00     13855675.00

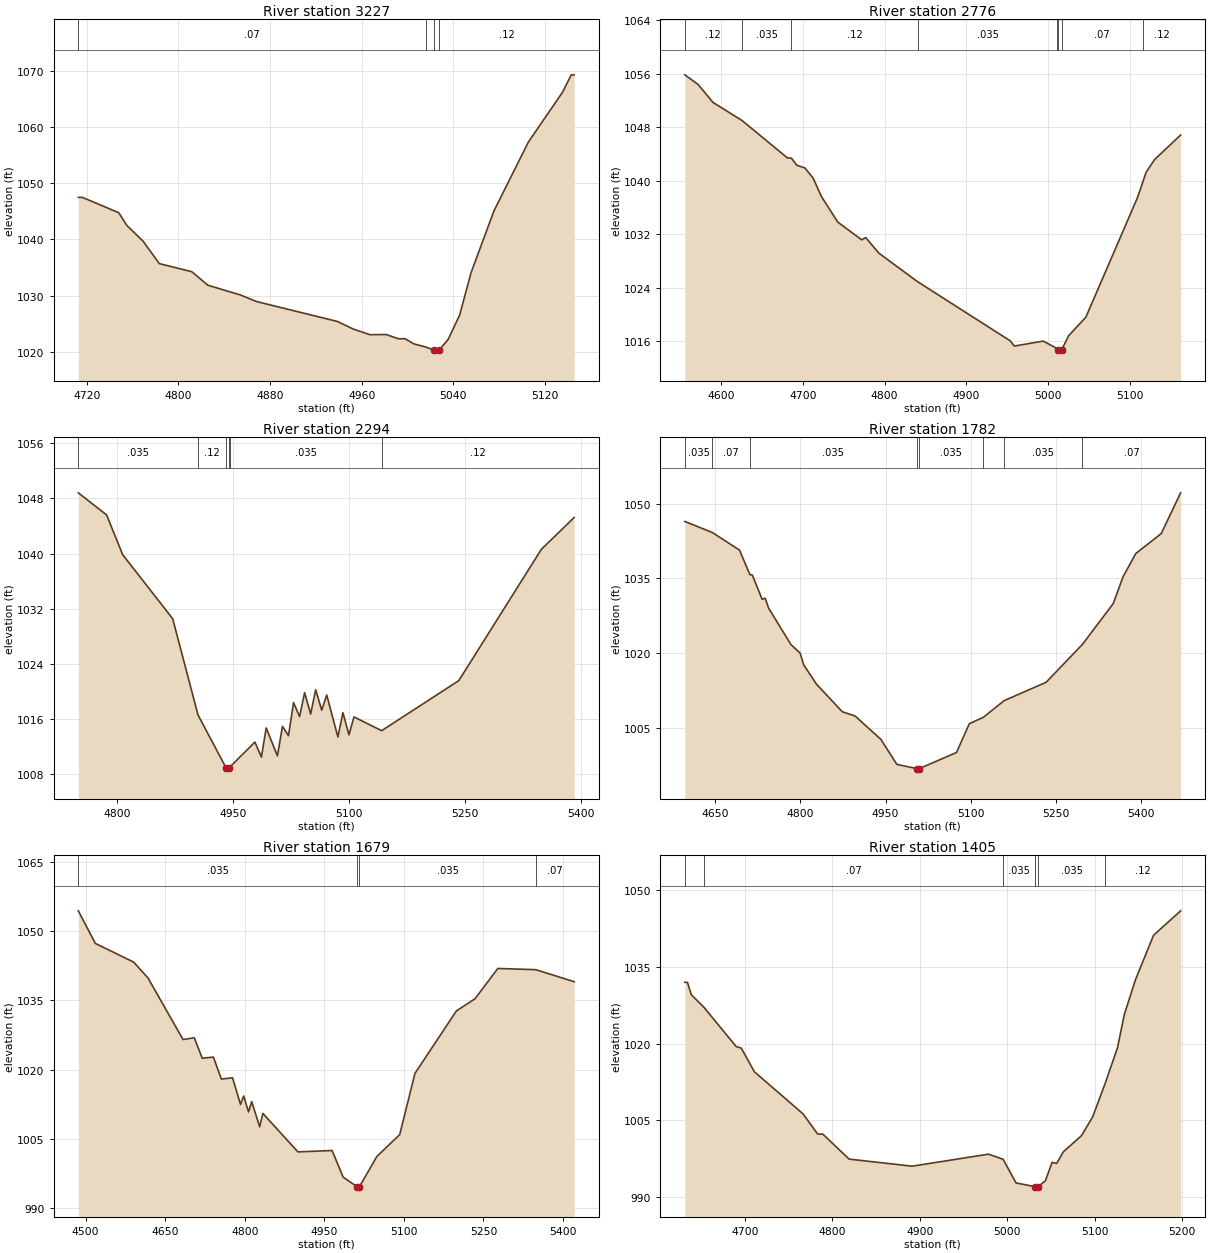
Type RM Length L Ch R = 1,3227,451,451,451
BEGIN DESCRIPTION:
Tom Tributary 9 7.0
END DESCRIPTION:
XS GIS Cut Line= 3
      2189675.03     13856774.97      2189875.00     13856575.00
      2189875.00     13856425.00
#Sta/Elev= 30
  4712.6 1047.50  4716.1 1047.50  4747.9 1044.76  4755.0 1042.49  4769.1 1039.71
  4783.3 1035.71  4811.6 1034.27  4825.7 1031.86  4854.0 1030.14  4868.1 1028.96
  4938.8 1025.41  4953.0 1024.03  4967.1 1023.06  4981.3 1023.09  4991.9 1022.34
  4997.9 1022.34  5005.4 1021.43  5015.8 1020.87  5023.4 1020.28  5023.7 1019.78
  5027.2 1019.78  5027.4 1020.28  5035.4 1022.22  5045.4 1026.52  5055.4 1034.09
  5075.4 1045.09  5105.4 1057.32  5135.4 1066.25  5142.9 1069.30  5145.4 1069.30
#Mann=4,-1,0
  4712.6    0.07       0  5015.8    0.12       0  5023.4    0.05       0
  5027.4    0.12       0
Bank Sta=5023.4,5027.4
Exp/Cntr=0.3,0.1

Type RM Length L Ch R = 1,2776,482,482,482
BEGIN DESCRIPTION:
Tom Tributary 9 6.0
END DESCRIPTION:
XS GIS Cut Line= 3
      2190275.85     13857021.16      2190325.00     13856575.00
      2190274.99     13856424.97
#Sta/Elev= 30
  4555.5 1055.86  4571.8 1054.42  4590.1 1051.72  4625.4 1049.04  4681.1 1043.43
  4686.0 1043.40  4692.5 1042.34  4702.5 1041.92  4712.6 1040.41  4722.7 1037.66
  4742.8 1033.82  4772.0 1031.17  4777.0 1031.50  4793.1 1029.17  4840.4 1024.91
  4953.9 1016.05  4958.9 1015.27  4994.3 1016.01  5011.6 1014.88  5012.9 1014.71
  5013.1 1014.21  5016.6 1014.21  5016.9 1014.71  5025.4 1016.81  5046.5 1019.59
  5109.8 1037.51  5116.3 1039.85  5120.3 1041.29  5130.8 1043.20  5162.5 1046.85
#Mann=8,-1,0
  4555.5    0.12       0  4625.4   0.035       0  4686.0    0.12       0
  4840.4   0.035       0  5011.6    0.07       0  5012.9   0.035       0
  5016.9    0.07       0  5116.3    0.12       0
Bank Sta=5012.9,5016.9
Exp/Cntr=0.3,0.1

Type RM Length L Ch R = 1,2294,512,512,512
BEGIN DESCRIPTION:
Tom Tributary 9 5.0
END DESCRIPTION:
XS GIS Cut Line= 3
      2190925.00     13856774.99      2190775.00     13856575.00
      2190525.00     13856275.00
#Sta/Elev= 30
  4750.4 1048.80  4786.9 1045.60  4807.7 1039.83  4872.3 1030.55  4905.0 1016.60
  4941.1 1008.96  4941.4 1008.46  4945.1 1008.96  4946.5 1009.09  4978.5 1012.67
  4986.9 1010.50  4993.1 1014.72  5007.6 1010.67  5014.1 1014.94  5021.9 1013.60
  5028.4 1018.40  5036.2 1016.36  5042.7 1019.84  5050.5 1016.73  5057.0 1020.26
  5064.8 1017.29  5071.3 1019.49  5085.7 1013.41  5092.2 1016.93  5100.0 1013.72
  5106.5 1016.32  5142.2 1014.32  5241.9 1021.58  5348.6 1040.62  5390.9 1045.22
#Mann=6,-1,0
  4750.4   0.035       0  4905.0    0.12       0  4941.1   0.035       0
  4945.1    0.12       0  4946.5   0.035       0  5142.2    0.12       0
Bank Sta=4941.1,4945.1
Exp/Cntr=0.3,0.1

Type RM Length L Ch R = 1,1782,103,103,103
BEGIN DESCRIPTION:
Tom Tributary 9 4.0
END DESCRIPTION:
XS GIS Cut Line= 3
      2191261.09     13856628.36      2191085.31     13856261.60
      2190664.33     13856057.62
#Sta/Elev= 30
  4596.0 1046.41  4644.3 1044.21  4692.5 1040.67  4710.8 1035.76  4715.2 1035.67
  4732.3 1030.83  4737.8 1031.02  4743.9 1029.03  4783.2 1021.76  4799.3 1020.06
  4805.8 1017.68  4828.5 1013.79  4873.8 1008.30  4896.4 1007.45  4941.8 1002.77
  4970.0  997.76  5005.5  996.91  5005.7  996.41  5009.5  996.91  5075.2 1000.14
  5097.8 1005.90  5122.6 1007.19  5159.2 1010.52  5233.3 1014.20  5297.4 1021.80
  5351.7 1029.97  5368.8 1035.28  5391.3 1039.97  5436.4 1043.99  5470.5 1052.14
#Mann=8,-1,0
  4596.0   0.035       0  4644.3    0.07       0  4710.8   0.035       0
  5005.5   0.035       0  5009.5   0.035       0  5122.6    0.12       0
  5159.2   0.035       0  5297.4    0.07       0
Bank Sta=5005.5,5009.5
Exp/Cntr=0.3,0.1

Type RM Length L Ch R = 1,1679,274,274,274
BEGIN DESCRIPTION:
Tom Tributary 9 3.5
END DESCRIPTION:
XS GIS Cut Line= 3
      2191449.27     13856614.40      2191205.93     13856247.23
      2190889.48     13855867.36
#Sta/Elev= 30
  4486.2 1054.37  4518.3 1047.31  4590.5 1043.27  4617.5 1039.84  4683.7 1026.49
  4704.8 1026.89  4719.8 1022.46  4740.9 1022.70  4755.9 1017.94  4777.0 1018.22
  4792.0 1012.45  4798.0 1014.27  4807.1 1010.82  4813.1 1013.06  4828.1 1007.61
  4834.1 1010.51  4900.3 1002.17  4964.7 1002.47  4985.5  996.71  5012.1  994.61
  5012.4  994.11  5016.1  994.61  5049.3 1001.21  5092.2 1005.92  5120.9 1019.16
  5199.0 1032.69  5234.1 1035.32  5277.1 1041.89  5348.6 1041.63  5421.1 1039.03
#Mann=4,-1,0
  4486.2   0.035       0  5012.1   0.035       0  5016.1   0.035       0
  5348.6    0.07       0
Bank Sta=5012.1,5016.1
Exp/Cntr=0.3,0.1

Type RM Length L Ch R = 1,1405,419,419,419
BEGIN DESCRIPTION:
Tom Tributary 9 3.0
END DESCRIPTION:
XS GIS Cut Line= 3
      2191575.01     13856425.02      2191375.00     13856125.00
      2191325.01     13855925.03
#Sta/Elev= 30
  4631.3 1031.99  4634.3 1031.99  4638.8 1029.56  4653.5 1027.04  4689.9 1019.45
  4695.9 1019.11  4710.9 1014.48  4766.5 1006.25  4783.1 1002.32  4789.1 1002.29
  4819.1  997.40  4891.2  996.02  4978.4  998.37  4995.1  997.37  5009.9  992.74
  5031.1  992.03  5031.4  991.53  5035.1  992.03  5043.4  993.15  5051.1  996.77
  5056.3  996.55  5064.0  998.84  5084.6 1001.97  5097.5 1005.66  5111.8 1012.23
  5125.9 1019.22  5133.6 1025.67  5146.5 1032.54  5167.1 1041.21  5198.0 1045.98
#Mann=6,-1,0
  4631.3   0.035       0  4653.5    0.07       0  4995.1   0.035       0
  5031.1   0.035       0  5035.1   0.035       0  5111.8    0.12       0
Bank Sta=5031.1,5035.1
Exp/Cntr=0.3,0.1

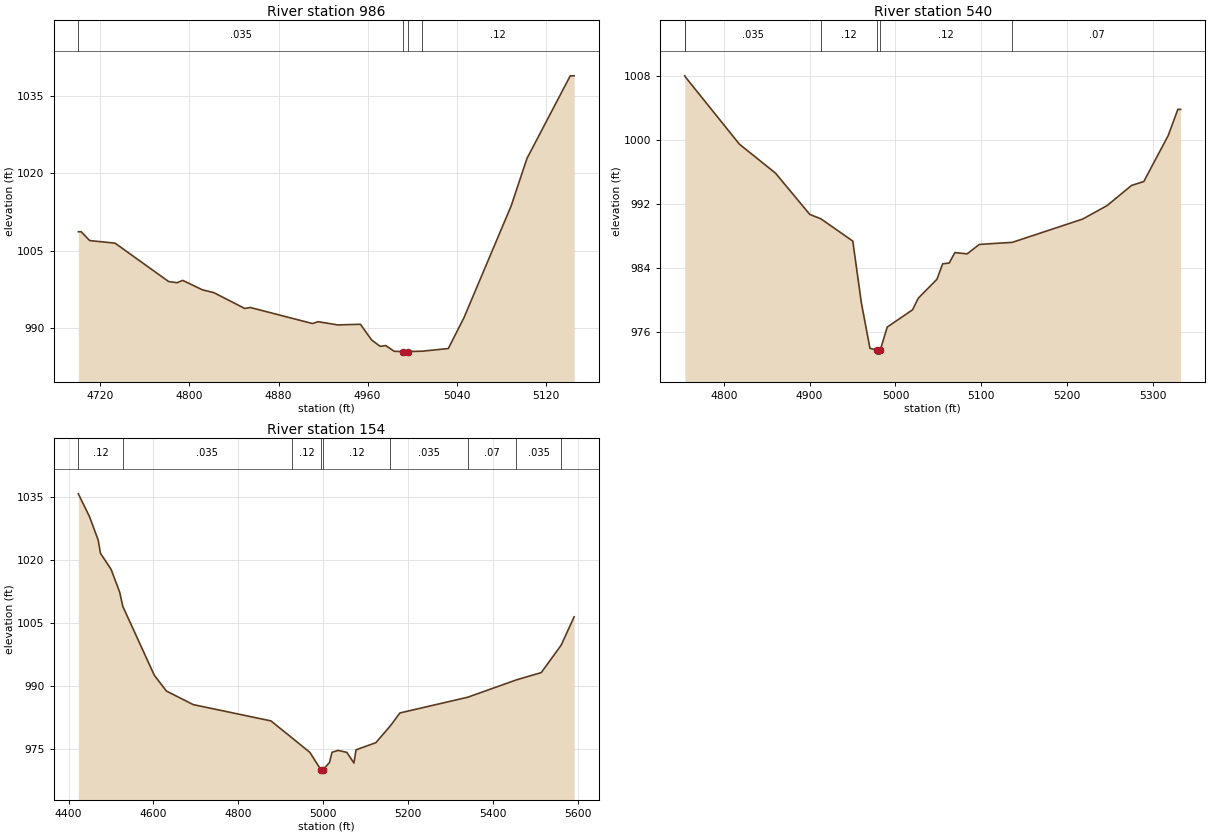
Type RM Length L Ch R = 1,986,446,446,446
BEGIN DESCRIPTION:
Tom Tributary 9 2.0
END DESCRIPTION:
XS GIS Cut Line= 3
      2191775.01     13856225.03      2191725.00     13855925.00
      2191624.99     13855824.99
#Sta/Elev= 30
  4700.1 1008.66  4702.7 1008.66  4710.3 1006.94  4733.1 1006.44  4781.2  998.98
  4788.8  998.74  4793.9  999.20  4811.6  997.36  4821.8  996.82  4849.7  993.73
  4854.7  993.92  4910.5  990.80  4915.6  991.16  4933.3  990.53  4953.6  990.66
  4963.7  987.60  4971.3  986.37  4976.4  986.51  4984.0  985.40  4992.1  985.35
  4992.4  984.85  4995.9  984.85  4996.1  985.35  5009.0  985.42  5032.6  985.94
  5046.7  991.95  5089.1 1013.69  5103.3 1022.92  5142.2 1038.99  5145.7 1038.99
#Mann=4,-1,0
  4700.1   0.035       0  4992.1   0.035       0  4996.1   0.035       0
  5009.0    0.12       0
Bank Sta=4992.1,4996.1
Exp/Cntr=0.3,0.1

Type RM Length L Ch R = 1,540,386,386,386
BEGIN DESCRIPTION:
Tom Tributary 9 1.0
END DESCRIPTION:
XS GIS Cut Line= 3
      2192183.40     13856170.46      2192170.66     13855920.66
      2191925.18     13855703.90
#Sta/Elev= 30
  4754.6 1008.08  4755.2 1007.95  4818.2  999.52  4860.2  995.90  4900.2  990.72
  4913.3  990.16  4950.3  987.38  4960.3  979.64  4970.3  973.95  4978.3  973.72
  4978.6  973.22  4982.1  973.22  4982.3  973.72  4990.4  976.61  5019.9  978.77
  5026.6  980.23  5048.3  982.59  5055.0  984.53  5062.6  984.63  5069.2  985.94
  5083.5  985.78  5097.7  986.96  5136.1  987.22  5218.1  990.14  5246.6  991.83
  5275.0  994.35  5289.3  994.84  5317.7 1000.59  5329.0 1003.88  5332.2 1003.88
#Mann=6,-1,0
  4754.6    0.12       0  4755.2   0.035       0  4913.3    0.12       0
  4978.3    0.05       0  4982.3    0.12       0  5136.1    0.07       0
Bank Sta=4978.3,4982.3
Exp/Cntr=0.3,0.1

Type RM Length L Ch R = 1,154,0,0,0
BEGIN DESCRIPTION:
Tom Tributary 9 0.1
END DESCRIPTION:
XS GIS Cut Line= 3
      2192400.00     13856340.87      2192509.66     13855774.18
      2191928.88     13855661.00
#Sta/Elev= 30
  4422.8 1035.83  4449.1 1030.41  4469.5 1024.86  4475.0 1021.68  4500.1 1017.85
  4520.4 1012.38  4527.7 1009.03  4601.9  992.66  4630.4  988.90  4693.6  985.67
  4876.9  981.79  4926.3  977.77  4968.6  974.31  4995.0  970.10  4995.3  969.60
  4999.0  970.10  5014.9  971.89  5020.9  974.32  5035.3  974.77  5055.7  974.31
  5072.5  971.77  5077.6  974.91  5124.2  976.61  5158.1  980.58  5180.9  983.68
  5341.0  987.43  5455.1  991.54  5514.2  993.29  5560.9  999.79  5591.7 1006.56
#Mann=9,-1,0
  4422.8    0.12       0  4527.7   0.035       0  4926.3    0.12       0
  4995.0    0.05       0  4999.0    0.12       0  5158.1   0.035       0
  5341.0    0.07       0  5455.1   0.035       0  5560.9    0.07       0
Bank Sta=4995,4999
Exp/Cntr=0.3,0.1

Chan Stop Cuts=-1