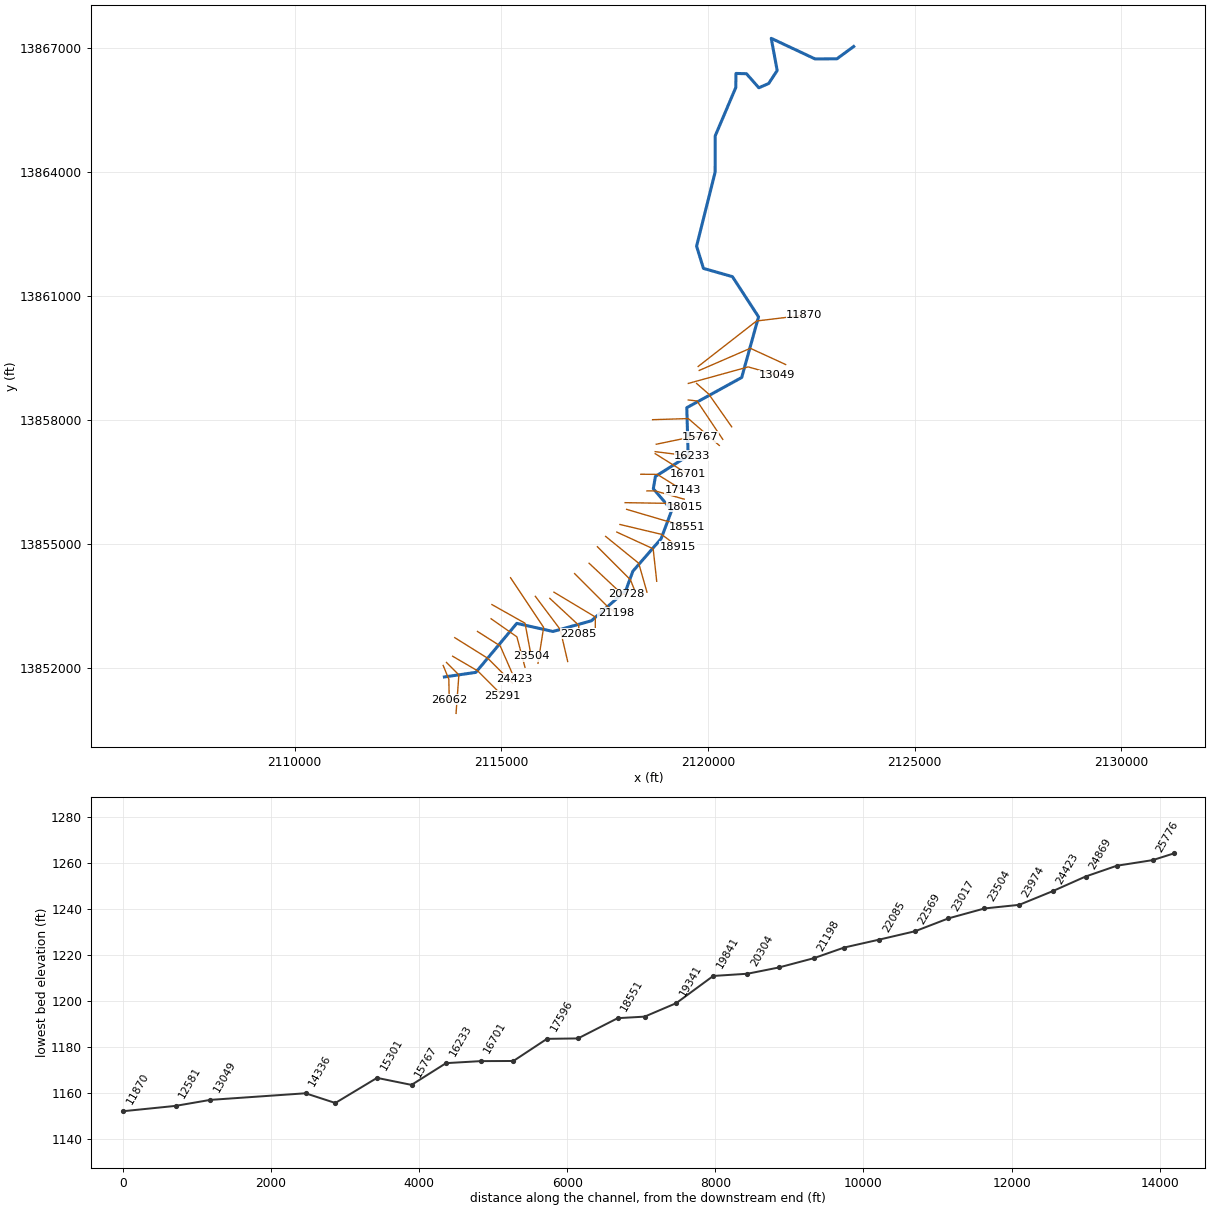
--- WALTER CREEK.prj (project) ---

Proj Title=WALTER CREEK Base Level Engineering
Current Plan=p01
Default Exp/Contr=0.3,0.1
English Units
Geom File=g01
Flow File=f01
Plan File=p01
Y Axis Title=Elevation
X Axis Title(PF)=Main Channel Distance
X Axis Title(XS)=Station
BEGIN DESCRIPTION:
WALTER CREEK
END DESCRIPTION:
DSS Export Rating Curves= 0
DSS Export Rating Curve Sorted= 0
DSS Export Volume Flow Curves= 0
DXF OffsetX= 0
DXF OffsetY= 0
DXF ScaleX= 1
DXF ScaleY= 10

--- WALTER CREEK.p01 (plan) ---

Plan Title=Multiple Run
Short Identifier=Multiple
Geom File=g01
Flow File=f01
Subcritical Flow
K Sum by GR= 0
Std Step Tol= 0.01
Critical Tol= 0.01
Num of Std Step Trials= 20
Max Error Tol= 0.3
Flow Tol Ratio= 0.001
Split Flow NTrial= 30
Split Flow Tol= 0.02
Split Flow Ratio= 0.02
Log Output Level= 0
Friction Slope Method= 1
Unsteady Friction Slope Method= 2
Unsteady Bridges Friction Slope Method= 1
Parabolic Critical Depth
Global Vel Dist=  1 , 1 , 1
Global Log Level= 0
CheckData=True
Encroach Param= -1, 0, 0, 0
BEGIN DESCRIPTION:
Multiple Run
END DESCRIPTION:

--- WALTER CREEK.f01 (steady flow) ---

Flow Title=Multiple
Number of Profiles=7
Profile Names=10-year,25-year,50-year,1pct_min,100-year,1pct_plu,500-year
River Rch & RM= WALTER CREEK,Reach-1,26062
     739    1211    1647    1086    2167    4324    3708
River Rch & RM= WALTER CREEK,Reach-1,25776
    1285    2178    3029    2038    4067    8115    7256
River Rch & RM= WALTER CREEK,Reach-1,24869
    1663    2861    4014    2722    5432   10837    9850
River Rch & RM= WALTER CREEK,Reach-1,18015
    2090    3627    5117    3486    6955   13877   12730
River Rch & RM= WALTER CREEK,Reach-1,11870
    2875    5086    7271    5017   10011   19974   18798
River Rch & RM= WALTER CREEK,Reach-1,9747
    3454    6157    8848    6132   12236   24413   23185
River Rch & RM= WALTER CREEK,Reach-1,7865
    3562    6345    9112    6310   12591   25122   23816
River Rch & RM= WALTER CREEK,Reach-1,4512
    3608    6422    9218    6379   12728   25397   24046
Boundary for River Rch & Prof#=WALTER CREEK,Reach-1,1
Up Type=0
Dn Type=3
Dn Slope=0.005
Boundary for River Rch & Prof#=WALTER CREEK,Reach-1,2
Up Type=0
Dn Type=3
Dn Slope=0.005
Boundary for River Rch & Prof#=WALTER CREEK,Reach-1,3
Up Type=0
Dn Type=3
Dn Slope=0.005
Boundary for River Rch & Prof#=WALTER CREEK,Reach-1,4
Up Type=0
Dn Type=3
Dn Slope=0.005
Boundary for River Rch & Prof#=WALTER CREEK,Reach-1,5
Up Type=0
Dn Type=3
Dn Slope=0.005
Boundary for River Rch & Prof#=WALTER CREEK,Reach-1,6
Up Type=0
Dn Type=3
Dn Slope=0.005
Boundary for River Rch & Prof#=WALTER CREEK,Reach-1,7
Up Type=0
Dn Type=3
Dn Slope=0.005

--- WALTER CREEK.g01 (geometry) ---

Geom Title=Existing Conditions
Program Version=4.10

River Reach=WALTER CREEK    ,Reach-1
Reach XY= 30
        2113625.       13851775.       2114384.8     13851885.48
      2115376.46     13853071.46        2116250.      13852874.6
      2117181.06     13853133.14      2118011.38     13853861.78
      2118182.86     13854331.17      2118867.18     13855118.81
      2119124.64     13855809.84      2118678.54     13856326.47
      2118728.61      13856623.5      2119521.49     13857126.25
      2119488.37     13858288.32      2120816.86     13859018.94
      2121223.79     13860485.51      2120592.13     13861458.55
      2119891.12     13861657.86      2119725.07     13862195.03
      2120173.78      13863985.5      2120175.75     13864864.31
      2120672.74     13866030.94      2120678.45     13866373.81
      2120931.19     13866367.15      2121230.89     13866026.96
      2121469.38     13866130.62      2121674.94     13866445.03
      2121530.49     13867223.04      2122590.21     13866725.51
      2123119.06     13866727.26        2123525.       13867025.

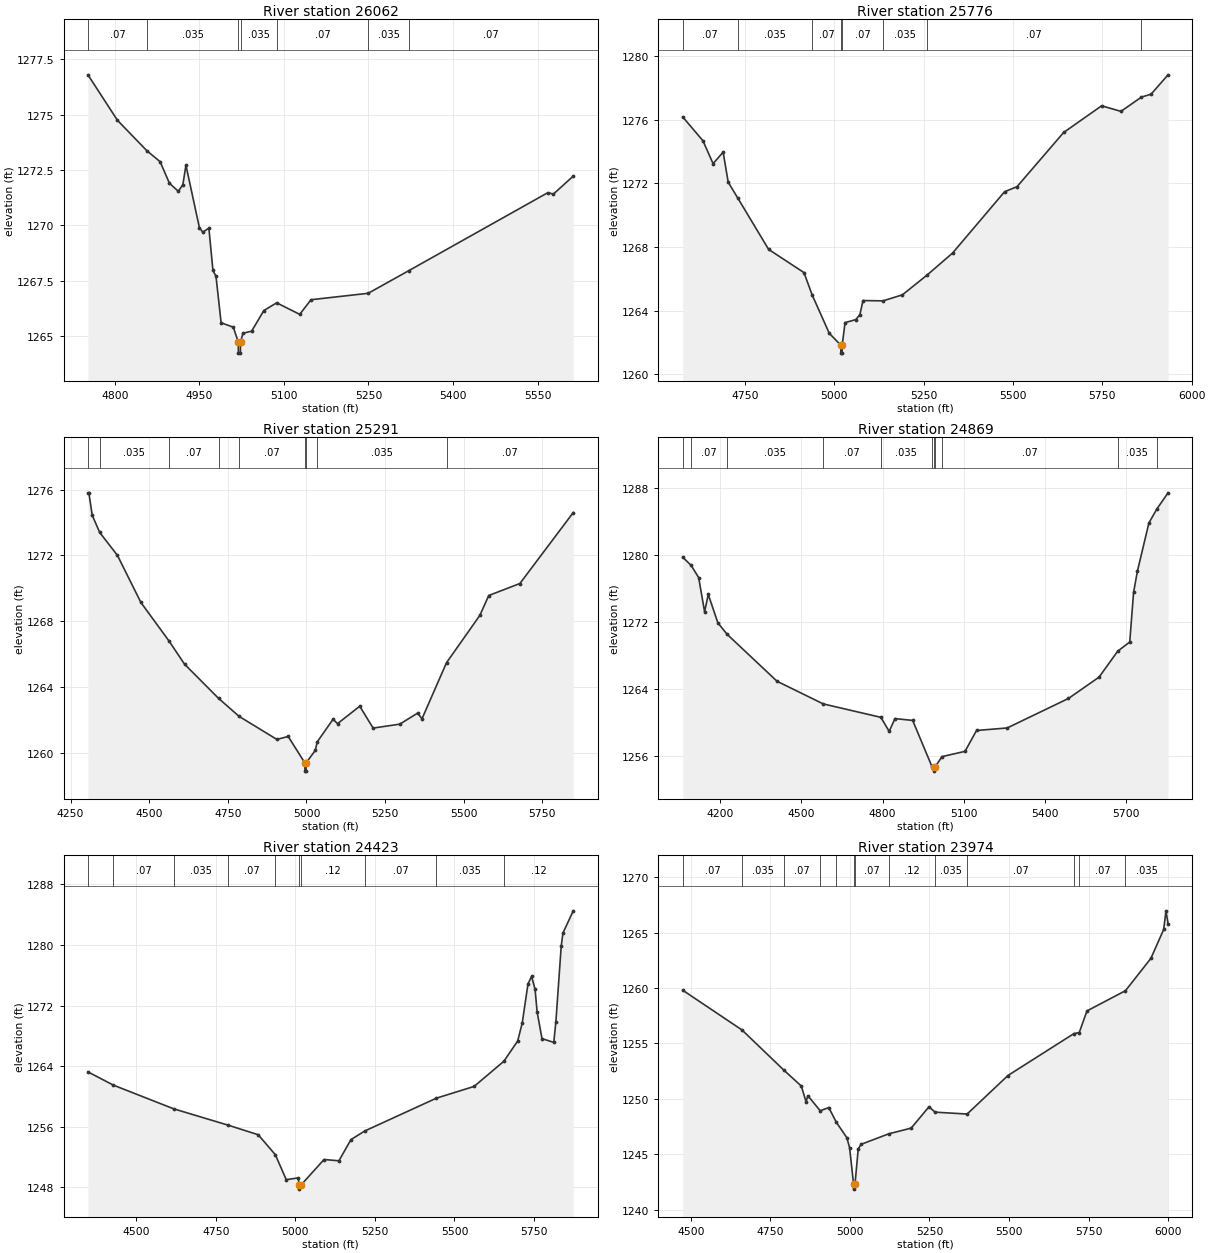
Type RM Length L Ch R = 1 ,26062   ,286,286,286
BEGIN DESCRIPTION:
WALTER CREEK 54.0
END DESCRIPTION:
XS GIS Cut Line= 3
      2113594.81     13852053.32      2113732.34     13851719.92
      2113740.67     13851219.94
#Sta/Elev= 30
  4752.5  1276.8  4804.8 1274.75  4856.8 1273.38  4880.5 1272.88    4897 1271.91
  4912.9 1271.54  4920.9 1271.85  4926.3 1272.72  4950.2  1269.9  4956.2  1269.7
    4967 1269.88  4974.2 1267.97  4979.6 1267.71  4988.7 1265.61  5010.3 1265.41
  5019.1 1264.74  5019.4 1264.24  5022.9 1264.24  5023.1 1264.74  5027.4 1265.14
  5042.8 1265.23  5064.4 1266.16  5087.2 1266.51  5128.1 1265.99  5148.1 1266.65
  5249.5 1266.94  5321.4 1267.96    5568 1271.48  5578.1 1271.42  5613.2 1272.23
#Mann= 7 ,-1 , 0
  4752.5     .07       0  4856.8    .035       0  5019.1    .035       0
  5023.1    .035       0  5087.2     .07       0  5249.5    .035       0
  5321.4     .07       0
Bank Sta=5019.1,5023.1
XS Rating Curve= 0 ,0
Exp/Cntr=0.3,0.1

Type RM Length L Ch R = 1 ,25776   ,485,485,485
BEGIN DESCRIPTION:
WALTER CREEK 53.0
END DESCRIPTION:
XS GIS Cut Line= 3
        2113675.       13852125.        2113975.       13851825.
      2113906.42     13850893.59
#Sta/Elev= 30
  4575.7 1276.19  4632.3 1274.69  4660.6 1273.25  4688.8 1273.97    4703 1272.08
  4729.3  1271.1  4816.1 1267.85  4915.1 1266.39  4937.8 1264.99  4985.8 1262.57
    5018 1261.82  5018.3 1261.32  5021.8 1261.32    5022 1261.82    5030 1263.24
  5060.1 1263.43  5071.6 1263.75  5080.2 1264.63  5136.3 1264.61  5190.5 1264.99
  5258.8 1266.22  5330.9 1267.62  5476.4 1271.48  5511.3  1271.8  5641.7 1275.21
    5748 1276.89  5802.1 1276.54  5859.6 1277.44  5886.3 1277.62  5933.9 1278.84
#Mann= 8 ,-1 , 0
  4575.7     .07       0  4729.3    .035       0  4937.8     .07       0
    5018     .05       0    5022     .07       0  5136.3    .035       0
  5258.8     .07       0  5859.6    .035       0
Bank Sta=5018,5022
XS Rating Curve= 0 ,0
Exp/Cntr=0.3,0.1

Type RM Length L Ch R = 1 ,25291   ,422,422,422
BEGIN DESCRIPTION:
WALTER CREEK 52.0
END DESCRIPTION:
XS GIS Cut Line= 3
      2113824.98     13852275.01        2114425.       13851925.
      2115025.02     13851324.98
#Sta/Elev= 30
  4305.1 1275.81    4308 1275.81  4318.8 1274.44  4342.5  1273.4    4399    1272
  4473.4 1269.14    4563 1266.79  4612.3 1265.38  4720.4  1263.3    4786  1262.2
  4905.9  1260.8  4941.9 1260.98  4994.8 1259.37  4995.1 1258.87  4998.6 1258.87
  4998.8 1259.37    5028 1260.13  5034.2 1260.65  5084.6 1262.03  5098.7 1261.76
  5169.4 1262.82  5211.9 1261.49  5296.7 1261.73  5353.3  1262.4  5367.4 1262.06
  5445.3 1265.47  5551.3 1268.35  5579.6 1269.56  5678.6 1270.29  5848.3 1274.61
#Mann= 9 ,-1 , 0
  4305.1     .07       0  4342.5    .035       0    4563     .07       0
  4720.4    .035       0    4786     .07       0  4994.8     .05       0
  4998.8     .07       0  5034.2    .035       0  5445.3     .07       0
Bank Sta=4994.8,4998.8
XS Rating Curve= 0 ,0
Exp/Cntr=0.3,0.1

Type RM Length L Ch R = 1 ,24869   ,446,446,446
BEGIN DESCRIPTION:
WALTER CREEK 51.0
END DESCRIPTION:
XS GIS Cut Line= 3
      2113875.04     13852724.97        2114675.       13852225.
      2115275.02     13851624.98
#Sta/Elev= 30
  4062.1  1279.7  4092.9 1278.73    4121 1277.26  4142.8 1273.19  4156.4 1275.25
  4191.8 1271.87  4226.2 1270.49  4410.5 1264.89  4581.1 1262.19  4793.5 1260.59
  4824.4 1258.91  4845.7 1260.44  4911.1 1260.22  4980.8 1254.83  4989.6 1254.67
  4989.9 1254.17  4994.2 1254.67  5019.2  1255.9  5104.4 1256.53  5146.9 1259.02
    5260 1259.32  5486.3 1262.84  5599.4 1265.39  5668.1 1268.48  5712.6 1269.58
  5726.7 1275.49  5740.8 1278.02  5783.3 1283.78  5811.9 1285.41    5854 1287.38
#Mann= 11 ,-1 , 0
  4062.1    .035       0  4092.9     .07       0  4226.2    .035       0
  4581.1     .07       0  4793.5    .035       0  4980.8     .12       0
  4989.6     .05       0  4994.2     .12       0  5019.2     .07       0
  5668.1    .035       0  5811.9     .12       0
Bank Sta=4989.6,4994.2
XS Rating Curve= 0 ,0
Exp/Cntr=0.3,0.1

Type RM Length L Ch R = 1 ,24423   ,449,449,449
BEGIN DESCRIPTION:
WALTER CREEK 50.0
END DESCRIPTION:
XS GIS Cut Line= 3
      2114424.97     13852875.02        2114975.       13852525.
      2115325.01     13851724.97
#Sta/Elev= 30
  4348.2 1263.25  4428.1  1261.5  4617.8 1258.37  4789.8  1256.2  4883.3 1254.95
  4937.2 1252.31  4971.4 1249.02  5009.1 1249.25  5012.2 1248.27  5012.6 1247.77
  5016.9 1248.27  5090.2 1251.68    5137 1251.51  5174.8 1254.31  5218.9 1255.46
  5443.4 1259.78  5561.9 1261.33  5655.3 1264.65  5698.7 1267.32  5713.1 1269.71
  5731.1 1274.85  5742.4 1275.85  5753.3 1274.17  5759.9 1271.16  5775.1 1267.64
  5812.2 1267.14  5818.8 1269.87  5835.6 1279.87    5841 1281.58  5873.4 1284.51
#Mann= 10 ,-1 , 0
  4348.2    .035       0  4428.1     .07       0  4617.8    .035       0
  4789.8     .07       0  4937.2     .12       0  5012.2     .05       0
  5016.9     .12       0  5218.9     .07       0  5443.4    .035       0
  5655.3     .12       0
Bank Sta=5012.2,5016.9
XS Rating Curve= 0 ,0
Exp/Cntr=0.3,0.1

Type RM Length L Ch R = 1 ,23974   ,470,470,470
BEGIN DESCRIPTION:
WALTER CREEK 49.0
END DESCRIPTION:
XS GIS Cut Line= 3
      2114753.34     13853182.71      2115378.48     13852745.11
      2115574.02     13852008.71
#Sta/Elev= 30
  4474.9 1259.81  4661.2 1256.22  4793.2 1252.58  4847.5 1251.16  4862.3 1249.75
  4868.4 1250.28  4907.1 1248.92  4933.8 1249.22  4957.5 1247.89  4990.5  1246.5
  4999.2  1245.6  5011.6 1242.35    5012 1241.85  5016.4 1242.35  5026.3 1245.46
    5035 1245.89  5121.9 1246.84  5192.8 1247.36  5248.8 1249.29  5267.7  1248.8
  5368.6 1248.63  5496.8 1252.11  5703.9 1255.89  5720.9 1255.99  5745.1 1257.94
  5866.2 1259.77  5946.1 1262.69  5986.2  1265.3  5993.4 1266.98  5999.9 1265.83
#Mann= 13 ,-1 , 0
  4474.9     .07       0  4661.2    .035       0  4793.2     .07       0
  4907.1    .035       0  4957.5     .07       0  5011.6     .05       0
  5016.4     .07       0  5121.9     .12       0  5267.7    .035       0
  5368.6     .07       0  5703.9    .035       0  5720.9     .07       0
  5866.2    .035       0
Bank Sta=5011.6,5016.4
XS Rating Curve= 0 ,0
Exp/Cntr=0.3,0.1

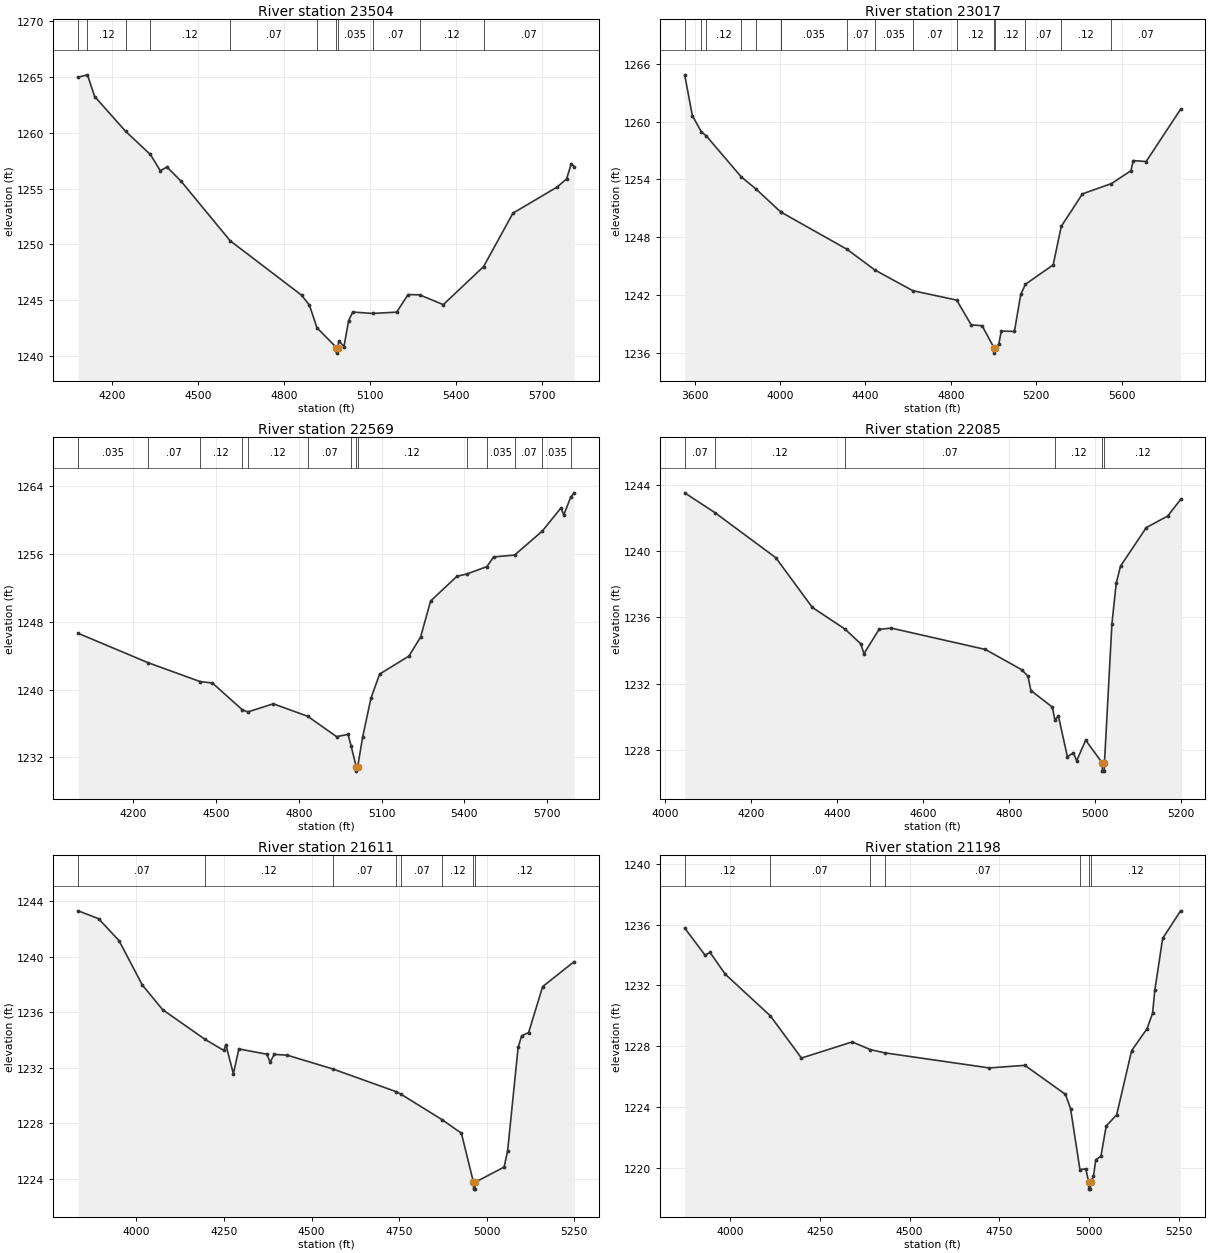
Type RM Length L Ch R = 1 ,23504   ,487,487,487
BEGIN DESCRIPTION:
WALTER CREEK 48.0
END DESCRIPTION:
XS GIS Cut Line= 3
      2114774.96     13853525.02        2115575.       13853075.
      2115725.01     13852274.96
#Sta/Elev= 30
  4082.1 1264.97  4114.3 1265.18  4139.5 1263.24  4247.8 1260.12    4334 1258.05
    4369 1256.59  4391.9 1256.93  4441.3 1255.66  4612.6 1250.33    4862 1245.46
  4889.4 1244.57  4915.8 1242.54  4983.9 1240.77  4984.2 1240.27  4988.8 1240.77
  4992.1 1241.37  5010.2 1240.86  5026.3 1243.17  5040.7 1243.95    5110 1243.82
  5194.2 1243.94    5234 1245.51    5274 1245.49    5357 1244.61  5497.8 1248.02
  5600.3  1252.8  5752.9 1255.11  5787.7 1255.86  5803.8 1257.23    5814 1256.97
#Mann= 11 ,-1 , 0
  4082.1     .07       0  4114.3     .12       0  4247.8     .07       0
    4334     .12       0  4612.6     .07       0  4915.8    .035       0
  4983.9    .035       0  4988.8    .035       0    5110     .07       0
    5274     .12       0  5497.8     .07       0
Bank Sta=4983.9,4988.8
XS Rating Curve= 0 ,0
Exp/Cntr=0.3,0.1

Type RM Length L Ch R = 1 ,23017   ,448,448,448
BEGIN DESCRIPTION:
WALTER CREEK 47.0
END DESCRIPTION:
XS GIS Cut Line= 3
      2115224.98     13854175.04        2116025.       13852975.
      2115889.07     13852105.42
#Sta/Elev= 30
  3553.4 1264.87  3589.5 1260.62  3631.6 1258.95  3654.8 1258.52  3817.8 1254.28
  3886.6 1253.02  4002.5 1250.63    4004 1250.61  4313.6 1246.74  4444.7 1244.58
  4621.5 1242.44  4827.2 1241.46    4895 1238.89  4946.1  1238.8  5003.3 1236.45
  5003.7 1235.95  5008.2 1236.45  5024.5  1236.9  5036.1 1238.25  5097.4  1238.2
  5127.2 1242.05  5149.3 1243.11  5279.1 1245.12  5316.8 1249.12  5416.1  1252.5
  5552.1 1253.57  5643.4 1254.91  5653.6 1255.96  5714.3 1255.86  5875.8  1261.3
#Mann= 16 ,-1 , 0
  3553.4     .12       0  3631.6     .07       0  3654.8     .12       0
  3817.8     .07       0  3886.6    .035       0  4002.5     .07       0
    4004    .035       0  4313.6     .07       0  4444.7    .035       0
  4621.5     .07       0  4827.2     .12       0  5003.3     .05       0
  5008.2     .12       0  5149.3     .07       0  5316.8     .12       0
  5552.1     .07       0
Bank Sta=5003.3,5008.2
XS Rating Curve= 0 ,0
Exp/Cntr=0.3,0.1

Type RM Length L Ch R = 1 ,22569   ,484,484,484
BEGIN DESCRIPTION:
WALTER CREEK 46.0
END DESCRIPTION:
XS GIS Cut Line= 3
      2115824.99     13853725.01        2116425.       13852925.
      2116607.46     13852148.57
#Sta/Elev= 30
  4000.1 1246.64    4252 1243.19  4441.3 1240.95  4486.6 1240.77  4594.4 1237.63
    4615 1237.36  4707.4 1238.32  4832.2 1236.84  4936.6 1234.44  4978.2 1234.71
  4989.4 1233.33  5007.8 1230.87  5008.2 1230.37    5013 1230.87  5030.9 1234.37
  5061.1 1238.97  5092.6 1241.83  5198.6 1243.95    5241 1246.19  5277.5 1250.46
  5373.4 1253.39  5407.6 1253.63  5481.4 1254.52  5505.7 1255.66  5581.8 1255.88
  5682.1 1258.71    5750 1261.45  5760.1 1260.62  5784.8 1262.69  5797.7 1263.23
#Mann= 14 ,-1 , 0
  4000.1    .035       0    4252     .07       0  4441.3     .12       0
  4594.4     .07       0    4615     .12       0  4832.2     .07       0
  4989.4     .12       0  5007.8     .05       0    5013     .12       0
  5407.6     .07       0  5481.4    .035       0  5581.8     .07       0
  5682.1    .035       0  5784.8     .07       0
Bank Sta=5007.8,5013
XS Rating Curve= 0 ,0
Exp/Cntr=0.3,0.1

Type RM Length L Ch R = 1 ,22085   ,474,474,474
BEGIN DESCRIPTION:
WALTER CREEK 45.0
END DESCRIPTION:
XS GIS Cut Line= 3
      2116175.02     13853674.99        2116875.       13853025.
        2116875.     13852825.03
#Sta/Elev= 30
  4044.8 1243.53  4114.9 1242.34  4257.1 1239.61  4342.1 1236.61  4418.2  1235.3
    4455 1234.41  4462.3 1233.81  4497.5 1235.28  4525.8 1235.36  4745.2 1234.07
  4830.2 1232.84  4844.4 1232.45  4851.2 1231.59  4901.1 1230.59  4907.2 1229.81
  4915.3 1230.05  4936.3 1227.59  4950.4 1227.83  4957.8 1227.34  4978.8 1228.59
  5017.4 1227.22  5017.8 1226.72  5022.2 1226.72  5022.6 1227.22    5040 1235.63
    5050 1238.07    5060  1239.1    5120 1241.43    5170 1242.13    5200 1243.13
#Mann= 6 ,-1 , 0
  4044.8     .07       0  4114.9     .12       0  4418.2     .07       0
  4907.2     .12       0  5017.4     .05       0  5022.6     .12       0
Bank Sta=5017.4,5022.6
XS Rating Curve= 0 ,0
Exp/Cntr=0.3,0.1

Type RM Length L Ch R = 1 ,21611   ,413,413,413
BEGIN DESCRIPTION:
WALTER CREEK 44.0
END DESCRIPTION:
XS GIS Cut Line= 3
      2116275.03     13853824.98        2117275.       13853225.
        2117275.     13852974.96
#Sta/Elev= 30
  3833.8 1243.32  3892.1 1242.75  3950.4 1241.17  4016.5 1237.99  4074.8  1236.2
    4196 1234.06  4249.7 1233.26  4255.5 1233.68  4276.9 1231.58  4292.5 1233.37
  4372.2 1232.99  4381.9 1232.42  4393.5 1232.98  4430.5 1232.92  4560.6 1231.93
  4741.8 1230.29  4755.4 1230.11  4872.5 1228.28    4928  1227.3  4962.4 1223.77
  4962.8 1223.27  4967.2 1223.27  4967.6 1223.77    5050 1224.86    5060 1226.02
    5090 1233.48    5100 1234.31    5120 1234.55    5160 1237.86    5250 1239.66
#Mann= 8 ,-1 , 0
  3833.8     .07       0    4196     .12       0  4560.6     .07       0
  4741.8     .12       0  4755.4     .07       0  4872.5     .12       0
  4962.4     .05       0  4967.6     .12       0
Bank Sta=4962.4,4967.6
XS Rating Curve= 0 ,0
Exp/Cntr=0.3,0.1

Type RM Length L Ch R = 1 ,21198   ,470,470,470
BEGIN DESCRIPTION:
WALTER CREEK 43.0
END DESCRIPTION:
XS GIS Cut Line= 3
      2116774.97     13854275.03        2117575.       13853475.
      2117774.99     13853325.01
#Sta/Elev= 30
  3873.4 1235.77    3930 1233.99  3944.1 1234.16  3986.6 1232.73  4111.8    1230
  4198.7 1227.22  4340.1 1228.28  4389.8 1227.78    4431 1227.56    4722 1226.57
    4821 1226.74  4934.1 1224.83  4948.2  1223.9  4974.4 1219.88  4990.7 1219.94
  4998.4  1219.1  4998.9  1218.6  5003.6  1218.6  5004.1  1219.1  5012.1 1219.44
  5018.4 1220.53  5032.9 1220.77  5047.5 1222.75  5076.7 1223.49  5118.4 1227.71
  5161.1 1229.14  5176.7 1230.17  5182.9 1231.67  5204.8 1235.09  5254.8  1236.9
#Mann= 7 ,-1 , 0
  3873.4     .12       0  4111.8     .07       0  4389.8     .12       0
    4431     .07       0  4974.4     .12       0  4998.4     .05       0
  5004.1     .12       0
Bank Sta=4998.4,5004.1
XS Rating Curve= 0 ,0
Exp/Cntr=0.3,0.1

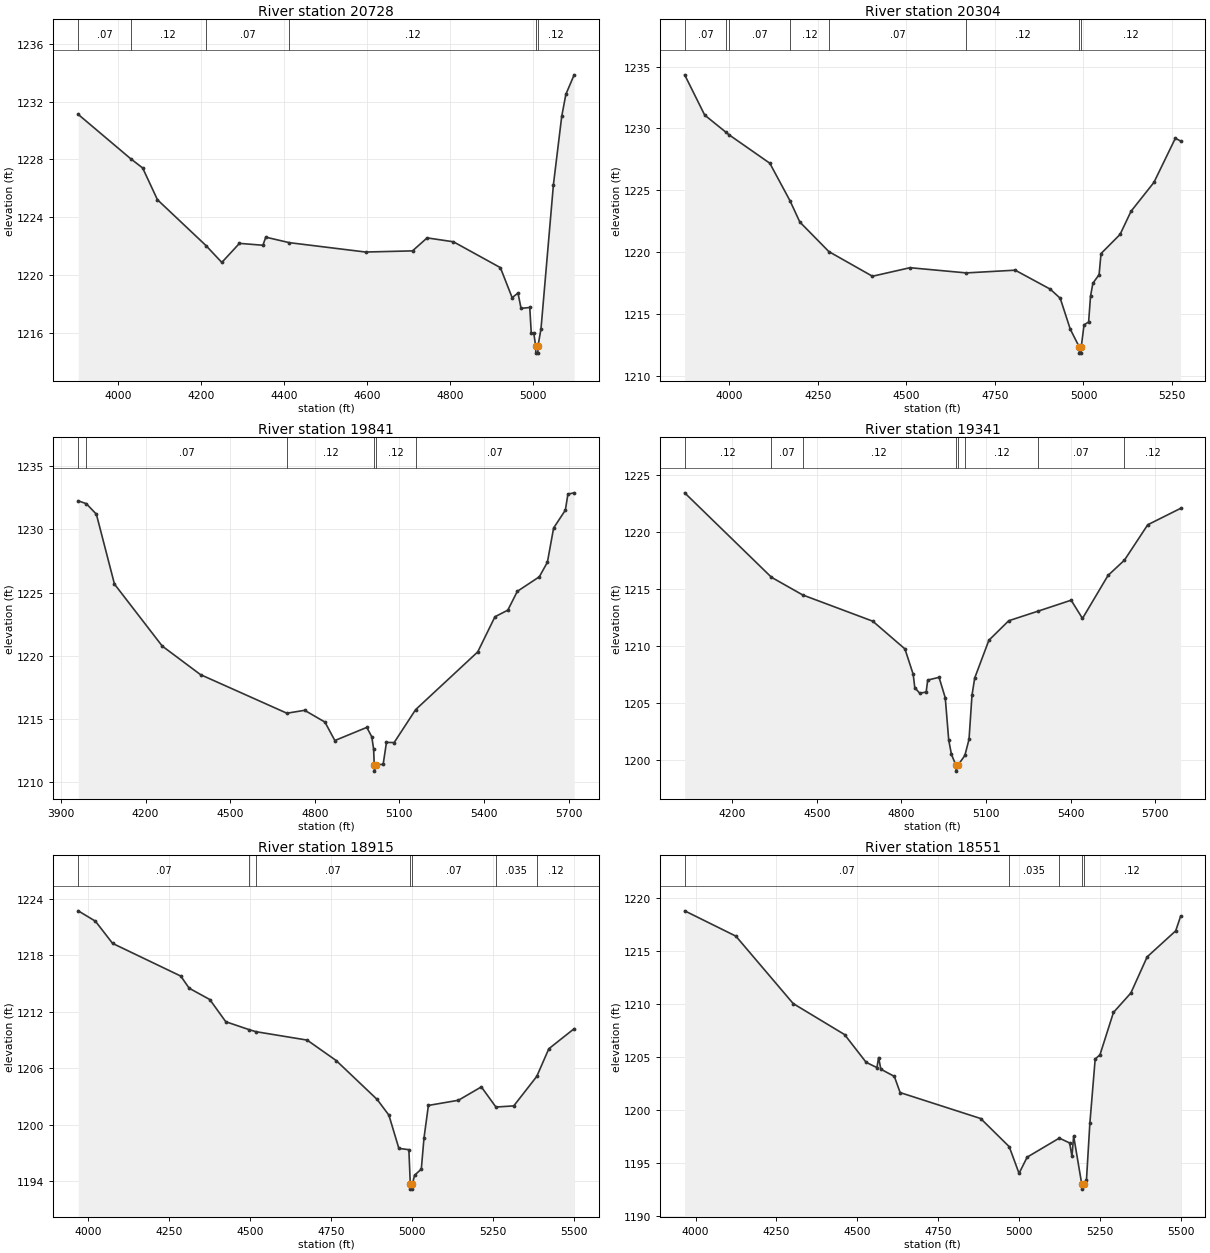
Type RM Length L Ch R = 1 ,20728   ,424,424,424
BEGIN DESCRIPTION:
WALTER CREEK 42.0
END DESCRIPTION:
XS GIS Cut Line= 3
      2117125.03     13854524.98        2117925.       13853775.
      2118025.05       13853775.
#Sta/Elev= 30
  3903.4 1231.11  4029.6 1228.05  4058.9  1227.4  4094.6  1225.2  4211.6 1222.03
  4249.9 1220.86  4292.4 1222.18  4349.1 1222.05  4355.9 1222.61  4412.6 1222.23
  4596.7 1221.58    4710 1221.66  4745.2 1222.56  4808.7 1222.29    4922  1220.5
  4950.4 1218.42  4964.5 1218.74  4971.9 1217.68  4992.9 1217.74  4996.5 1215.98
  5002.5 1215.98  5007.1 1215.08  5007.6 1214.58  5012.4 1214.58  5012.8 1215.08
    5020 1216.26    5050 1226.25    5070 1230.97    5080  1232.5    5100 1233.85
#Mann= 6 ,-1 , 0
  3903.4     .07       0  4029.6     .12       0  4211.6     .07       0
  4412.6     .12       0  5007.1     .05       0  5012.8     .12       0
Bank Sta=5007.1,5012.8
XS Rating Curve= 0 ,0
Exp/Cntr=0.3,0.1

Type RM Length L Ch R = 1 ,20304   ,463,463,463
BEGIN DESCRIPTION:
WALTER CREEK 41.0
END DESCRIPTION:
XS GIS Cut Line= 3
      2117325.02     13854924.98        2118125.       13854125.
        2118225.       13853875.
#Sta/Elev= 30
  3873.7 1234.33  3930.2 1231.08  3990.8 1229.68  3999.3 1229.48  4114.1 1227.19
  4171.3 1224.15  4198.9 1222.44    4281 1220.05    4404 1218.06  4510.1 1218.75
    4669 1218.33  4807.1 1218.55    4906 1217.02  4934.3 1216.28  4962.6 1213.79
    4988 1212.35  4988.5 1211.85  4993.3 1211.85  4993.7 1212.35  5001.5 1214.13
  5014.5 1214.37  5019.9 1216.46  5026.6  1217.5  5044.1 1218.19  5049.5 1219.89
  5103.3 1221.44  5134.3 1223.31  5198.9 1225.64  5259.5 1229.21  5274.3 1228.98
#Mann= 8 ,-1 , 0
  3873.7     .07       0  3990.8     .12       0  3999.3     .07       0
  4171.3     .12       0    4281     .07       0    4669     .12       0
    4988     .05       0  4993.7     .12       0
Bank Sta=4988,4993.7
XS Rating Curve= 0 ,0
Exp/Cntr=0.3,0.1

Type RM Length L Ch R = 1 ,19841   ,500,500,500
BEGIN DESCRIPTION:
WALTER CREEK 40.0
END DESCRIPTION:
XS GIS Cut Line= 3
      2117525.03     13855174.97        2118325.       13854525.
      2118524.99     13853825.04
#Sta/Elev= 30
  3961.3 1232.26  3990.1 1232.03  4025.7  1231.2  4089.9 1225.67  4259.3 1220.77
  4395.1 1218.51  4701.3 1215.46  4764.3 1215.69  4836.2 1214.76  4871.4  1213.3
  4984.8 1214.34  5002.4 1213.59  5008.9 1212.62  5011.1 1211.38  5011.6 1210.88
  5017.2 1211.38  5042.7 1211.42  5054.4 1213.15  5081.7 1213.14  5157.7 1215.74
  5378.1 1220.31  5439.2 1223.09  5484.7 1223.61  5518.5  1225.1  5596.5 1226.25
  5625.1  1227.4  5647.2 1230.11  5688.8 1231.52  5697.9 1232.79    5720 1232.89
#Mann= 6 ,-1 , 0
  3961.3     .12       0  3990.1     .07       0  4701.3     .12       0
  5011.1     .05       0  5017.2     .12       0  5157.7     .07       0
Bank Sta=5011.1,5017.2
XS Rating Curve= 0 ,0
Exp/Cntr=0.3,0.1

Type RM Length L Ch R = 1 ,19341   ,426,426,426
BEGIN DESCRIPTION:
WALTER CREEK 39.0
END DESCRIPTION:
XS GIS Cut Line= 3
      2117795.32     13855279.02        2118675.       13854875.
      2118760.48     13854089.06
#Sta/Elev= 30
  4031.7 1223.42  4339.4 1216.02  4450.2 1214.47  4698.7 1212.17  4812.7 1209.74
  4842.1 1207.51  4847.6 1206.35  4865.1 1205.86    4888 1205.96  4893.5 1207.01
  4933.7 1207.25  4955.7 1205.46    4968 1201.75  4977.7 1200.49  4993.9 1199.53
  4994.4 1199.03  5000.1 1199.53  5025.2  1200.4    5040 1201.82  5050.5 1205.67
  5060.1 1207.19  5110.4  1210.5  5180.8 1212.21  5284.8 1213.05  5402.1 1214.01
  5442.3 1212.41  5532.9 1216.18  5591.1 1217.52  5673.7 1220.62  5790.3 1222.06
#Mann= 8 ,-1 , 0
  4031.7     .12       0  4339.4     .07       0  4450.2     .12       0
  4993.9     .05       0  5000.1     .12       0  5025.2     .12       0
  5284.8     .07       0  5591.1     .12       0
Bank Sta=4993.9,5000.1
XS Rating Curve= 0 ,0
Exp/Cntr=0.3,0.1

Type RM Length L Ch R = 1 ,18915   ,364,364,364
BEGIN DESCRIPTION:
WALTER CREEK 38.0
END DESCRIPTION:
XS GIS Cut Line= 3
       2117871.7     13855463.05        2118875.       13855225.
      2119275.03     13854924.97
#Sta/Elev= 30
  3969.2 1222.73  4022.3 1221.63  4075.4 1219.27  4285.8  1215.8  4311.8 1214.51
  4375.4 1213.31  4424.8 1210.95  4497.7  1210.1  4518.5 1209.89    4676    1209
  4765.6 1206.83  4892.3 1202.69  4928.4 1201.03  4959.2  1197.5  4990.1 1197.36
  4994.6 1193.67  4995.1 1193.17  5000.4 1193.17  5000.9 1193.67  5007.6 1194.64
  5028.5  1195.3  5036.8  1198.6  5050.4 1202.06  5143.1 1202.61  5213.9 1204.03
  5258.8 1201.89  5313.9 1202.01  5384.9 1205.14  5422.2 1208.08  5500.4 1210.21
#Mann= 7 ,-1 , 0
  3969.2     .07       0  4497.7     .12       0  4518.5     .07       0
  4994.6     .05       0  5000.9     .07       0  5258.8    .035       0
  5384.9     .12       0
Bank Sta=4994.6,5000.9
XS Rating Curve= 0 ,0
Exp/Cntr=0.3,0.1

Type RM Length L Ch R = 1 ,18551   ,536,536,536
BEGIN DESCRIPTION:
WALTER CREEK 37.0
END DESCRIPTION:
XS GIS Cut Line= 2
      2118033.17       13855829.      2119504.26     13855395.59
#Sta/Elev= 30
  3966.2 1218.79  4124.5  1216.4  4301.7 1210.03  4460.7  1207.1  4527.3 1204.48
  4560.7 1203.98  4565.9 1204.93  4572.8 1203.83  4614.5 1203.15  4632.5 1201.62
  4881.5 1199.17  4969.8 1196.51  5000.2 1193.99  5025.2 1195.52  5124.7 1197.32
  5156.6 1196.86  5163.8  1195.6    5169 1197.52  5193.9    1193  5194.4  1192.5
  5200.2    1193  5208.7 1193.38  5219.1  1198.7  5235.6 1204.79  5250.4 1205.19
  5292.1 1209.19    5346 1211.03  5396.3 1214.44  5484.6  1216.9  5499.8 1218.28
#Mann= 5 ,-1 , 0
  3966.2     .07       0  4969.8    .035       0  5124.7     .12       0
  5193.9    .035       0  5200.2     .12       0
Bank Sta=5193.9,5200.2
XS Rating Curve= 0 ,0
Exp/Cntr=0.3,0.1

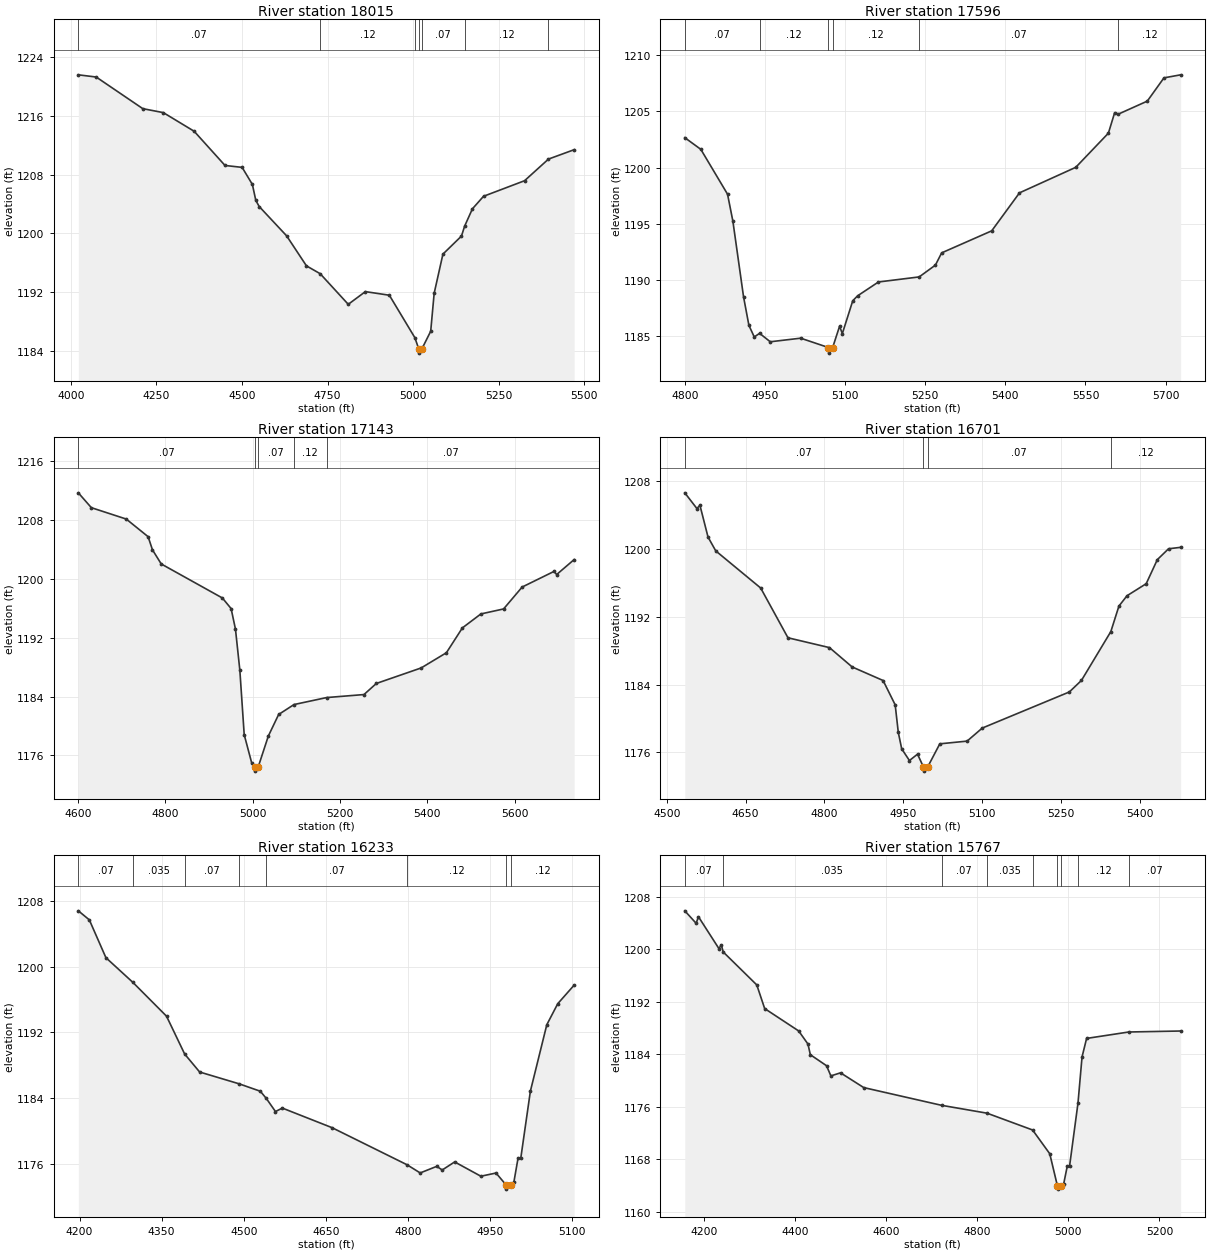
Type RM Length L Ch R = 1 ,18015   ,419,419,419
BEGIN DESCRIPTION:
WALTER CREEK 36.0
END DESCRIPTION:
XS GIS Cut Line= 3
       2117996.7     13855990.83        2118975.       13855975.
      2119437.67      13855893.6
#Sta/Elev= 30
  4021.9  1221.6  4074.1  1221.3  4210.2 1216.99  4270.2 1216.45  4360.2 1213.91
  4450.3 1209.25  4500.3 1208.99  4530.3 1206.66  4540.3 1204.48  4550.3 1203.65
  4630.3 1199.66  4688.2 1195.57  4728.3  1194.5  4810.3 1190.33  4860.3 1192.06
  4930.3 1191.57  5004.9 1185.78  5016.7 1184.18  5017.2 1183.68  5024.5 1184.18
  5051.1 1186.66  5061.2 1191.83  5086.8 1197.17    5141 1199.63  5150.2 1200.98
  5172.9 1203.34  5205.4 1205.05  5325.2 1207.17  5395.1 1210.12  5470.1  1211.4
#Mann= 7 ,-1 , 0
  4021.9     .07       0  4728.3     .12       0  5004.9     .07       0
  5016.7     .05       0  5024.5     .07       0  5150.2     .12       0
  5395.1     .07       0
Bank Sta=5016.7,5024.5
XS Rating Curve= 0 ,0
Exp/Cntr=0.3,0.1

Type RM Length L Ch R = 1 ,17596   ,453,453,453
BEGIN DESCRIPTION:
WALTER CREEK 35.0
END DESCRIPTION:
XS GIS Cut Line= 3
      2118524.95       13856275.        2118725.       13856275.
      2119425.04     13856074.99
#Sta/Elev= 30
    4800 1202.67    4830 1201.63    4880 1197.64    4890 1195.24    4910  1188.5
    4920 1185.97    4930 1184.94    4940 1185.26    4960 1184.51  5016.9 1184.83
  5068.8    1184  5069.3  1183.5  5076.8    1184  5089.7 1185.89  5094.9 1185.24
  5114.4 1188.16  5123.5  1188.6  5162.5 1189.83  5238.7 1190.28  5269.1 1191.33
  5280.8 1192.42  5374.5 1194.38  5426.5 1197.76  5531.8 1200.03  5592.9 1203.07
  5604.6 1204.89  5611.8 1204.77  5665.7 1205.92  5696.9 1207.99  5728.1 1208.26
#Mann= 6 ,-1 , 0
    4800     .07       0    4940     .12       0  5068.8     .05       0
  5076.8     .12       0  5238.7     .07       0  5611.8     .12       0
Bank Sta=5068.8,5076.8
XS Rating Curve= 0 ,0
Exp/Cntr=0.3,0.1

Type RM Length L Ch R = 1 ,17143   ,442,442,442
BEGIN DESCRIPTION:
WALTER CREEK 34.0
END DESCRIPTION:
XS GIS Cut Line= 3
      2118375.16     13856678.33        2118775.       13856675.
      2119399.48     13856285.97
#Sta/Elev= 30
  4600.5 1211.73  4630.3 1209.71  4710.3 1208.16  4760.3 1205.76  4770.3 1203.97
  4790.4 1202.05  4930.4 1197.42  4950.4 1195.98  4960.4 1193.18  4970.4  1187.6
  4980.4 1178.82  4997.9  1174.9    5004 1174.36  5004.5 1173.86  5012.1 1174.36
  5035.7 1178.64  5059.3 1181.57  5094.5 1182.92  5169.1 1183.87  5254.7 1184.28
  5283.1 1185.79  5385.7  1187.9  5443.5 1189.97  5480.1 1193.35  5522.5 1195.25
  5574.5 1195.93    5617 1198.91  5690.1 1201.04    5696 1200.61  5736.1 1202.65
#Mann= 5 ,-1 , 0
  4600.5     .07       0    5004     .05       0  5012.1     .07       0
  5094.5     .12       0  5169.1     .07       0
Bank Sta=5004,5012.1
XS Rating Curve= 0 ,0
Exp/Cntr=0.3,0.1

Type RM Length L Ch R = 1 ,16701   ,468,468,468
BEGIN DESCRIPTION:
WALTER CREEK 33.0
END DESCRIPTION:
XS GIS Cut Line= 3
      2118725.04     13857174.98        2119125.       13856925.
      2119525.04     13856674.98
#Sta/Elev= 30
  4534.2 1206.63  4557.2 1204.78    4563 1205.16  4578.4 1201.41  4593.1 1199.78
  4678.6  1195.4  4730.5 1189.53  4809.5 1188.37  4852.6 1186.09  4911.5 1184.49
  4934.5 1181.62  4940.4 1178.37  4946.9 1176.43  4961.6 1175.05    4977  1175.8
  4988.2  1174.3  4988.7  1173.8  4996.4  1174.3  5019.4 1177.02  5071.3 1177.34
  5100.2 1178.88  5265.9 1183.14  5288.9  1184.5  5344.8 1190.26  5360.2 1193.27
  5375.6 1194.49  5412.1 1195.91  5433.3 1198.75  5454.6 1200.03  5477.6  1200.2
#Mann= 4 ,-1 , 0
  4534.2     .07       0  4988.2     .05       0  4996.4     .07       0
  5344.8     .12       0
Bank Sta=4988.2,4996.4
XS Rating Curve= 0 ,0
Exp/Cntr=0.3,0.1

Type RM Length L Ch R = 1 ,16233   ,466,466,466
BEGIN DESCRIPTION:
WALTER CREEK 32.0
END DESCRIPTION:
XS GIS Cut Line= 3
      2118725.02       13857225.        2119525.       13857125.
      2119624.99       13857125.
#Sta/Elev= 30
  4197.7 1206.78  4217.8 1205.68  4248.1 1201.08  4297.3 1198.08  4358.9 1193.96
    4392 1189.36  4419.4 1187.17  4491.7 1185.73  4530.3 1184.83  4541.1 1183.97
    4558 1182.36  4570.6 1182.78  4661.3  1180.4  4798.6 1175.88  4822.5 1174.89
  4852.7 1175.69  4862.8 1175.25  4885.5 1176.23  4933.4 1174.49  4961.1 1174.88
  4979.6 1173.42  4980.1 1172.92  4987.9 1173.42  4993.8  1173.8  5001.4 1176.71
  5006.4 1176.71  5023.9 1184.84  5053.9 1192.92  5073.9 1195.48  5103.9 1197.74
#Mann= 8 ,-1 , 0
  4197.7     .07       0  4297.3    .035       0    4392     .07       0
  4491.7    .035       0  4541.1     .07       0  4798.6     .12       0
  4979.6     .05       0  4987.9     .12       0
Bank Sta=4979.6,4987.9
XS Rating Curve= 0 ,0
Exp/Cntr=0.3,0.1

Type RM Length L Ch R = 1 ,15767   ,466,466,466
BEGIN DESCRIPTION:
WALTER CREEK 31.0
END DESCRIPTION:
XS GIS Cut Line= 3
      2118750.15     13857404.02        2119575.       13857575.
       2119821.5     13857577.61
#Sta/Elev= 30
  4157.6 1205.85  4182.5 1203.95  4187.6 1204.95  4232.6 1200.09  4237.7 1200.67
    4242 1199.58  4315.7 1194.56    4333 1190.96  4407.7 1187.55  4428.1 1185.55
  4433.3 1183.93  4468.9 1182.25  4478.4  1180.7  4499.6 1181.17  4550.6 1178.92
  4721.4 1176.22  4821.4 1175.02  4921.4 1172.46  4959.1 1168.84  4975.9 1163.95
  4976.4 1163.45  4984.2 1163.95  4989.8 1164.29  4997.4  1166.9  5002.5  1166.9
  5021.1 1176.56    5030 1183.59    5040 1186.41  5132.6 1187.39  5246.5 1187.54
#Mann= 9 ,-1 , 0
  4157.6     .07       0    4242    .035       0  4721.4     .07       0
  4821.4    .035       0  4921.4     .07       0  4975.9     .05       0
  4984.2     .07       0  5021.1     .12       0  5132.6     .07       0
Bank Sta=4975.9,4984.2
XS Rating Curve= 0 ,0
Exp/Cntr=0.3,0.1

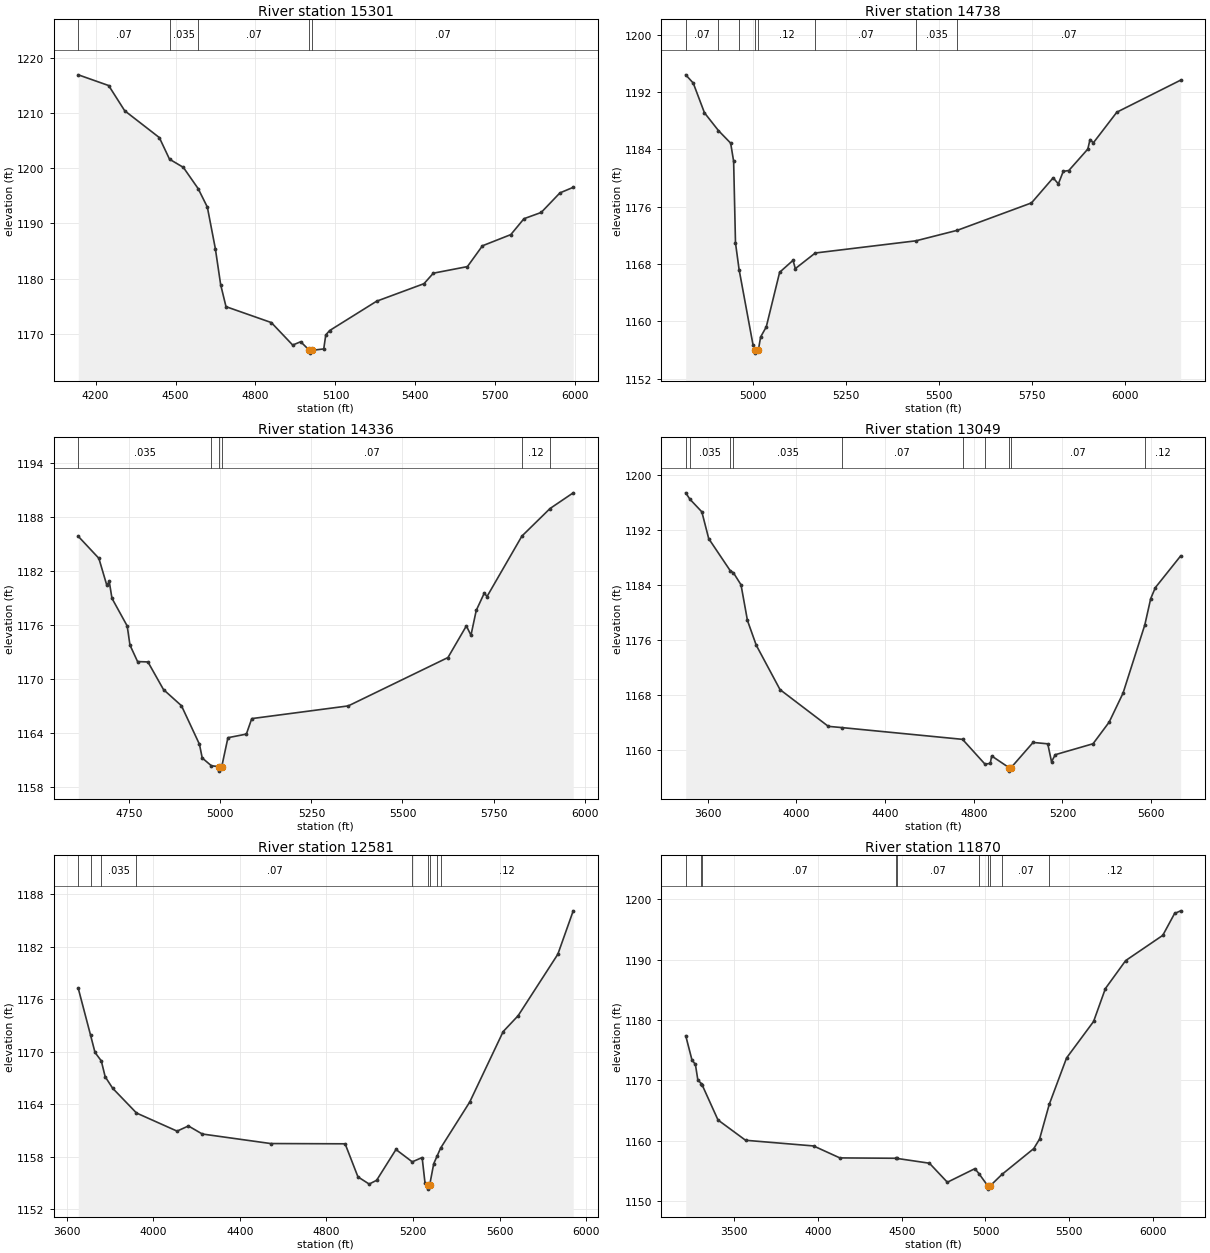
Type RM Length L Ch R = 1 ,15301   ,563,563,563
BEGIN DESCRIPTION:
WALTER CREEK 30.0
END DESCRIPTION:
XS GIS Cut Line= 3
      2118661.02     13857998.15        2119525.       13858025.
      2120275.03     13857374.98
#Sta/Elev= 30
  4135.2 1216.87  4249.2 1214.93  4309.3 1210.37  4439.3 1205.51  4477.5  1201.6
  4529.4 1200.12  4585.1 1196.26  4619.4 1192.93  4649.4 1185.42  4669.4 1178.88
  4689.4 1174.91  4859.5 1172.03  4939.6 1167.96  4969.6 1168.56  5002.5    1167
    5003  1166.5  5010.9    1167  5056.1 1167.26  5063.7 1169.79    5078 1170.58
  5254.6  1175.9  5432.2 1179.07  5467.3 1180.97  5595.1 1182.16  5651.6 1185.93
  5757.9 1187.95  5807.3 1190.83  5871.9 1191.96  5942.2  1195.5  5992.1 1196.51
#Mann= 5 ,-1 , 0
  4135.2     .07       0  4477.5    .035       0  4585.1     .07       0
  5002.5     .05       0  5010.9     .07       0
Bank Sta=5002.5,5010.9
XS Rating Curve= 0 ,0
Exp/Cntr=0.3,0.1

Type RM Length L Ch R = 1 ,14738   ,402,402,402
BEGIN DESCRIPTION:
WALTER CREEK 29.0
END DESCRIPTION:
XS GIS Cut Line= 3
      2119524.95     13858475.01      2119736.27     13858450.77
      2120358.44     13857521.76
#Sta/Elev= 30
    4819  1194.4  4839.2 1193.25  4869.4  1189.1    4907 1186.62  4939.8 1184.87
  4947.8 1182.34  4952.8 1170.95  4962.5 1167.23  5000.2 1156.65    5006 1156.07
  5006.5 1155.57  5014.5 1156.07  5020.4 1157.83  5035.5 1159.22  5071.5 1166.85
  5107.6 1168.52  5113.6 1167.36  5167.3 1169.54  5437.9 1171.24  5549.4 1172.71
  5748.7 1176.53    5807 1180.03  5820.9 1179.18  5834.1 1180.93  5849.1 1181.05
  5900.1 1184.04  5906.1 1185.37  5915.1 1184.92  5978.2 1189.19  6149.8 1193.66
#Mann= 8 ,-1 , 0
    4819     .07       0    4907    .035       0  4962.5     .12       0
    5006     .05       0  5014.5     .12       0  5167.3     .07       0
  5437.9    .035       0  5549.4     .07       0
Bank Sta=5006,5014.5
XS Rating Curve= 0 ,0
Exp/Cntr=0.3,0.1

Type RM Length L Ch R = 1 ,14336   ,1287,1287,1287
BEGIN DESCRIPTION:
WALTER CREEK 28.0
END DESCRIPTION:
XS GIS Cut Line= 3
      2119724.99       13858875.      2120021.01     13858615.83
        2120575.     13857825.01
#Sta/Elev= 30
  4609.8 1185.86  4666.3 1183.42  4688.1 1180.43  4694.8 1180.85  4702.3 1178.98
  4744.1 1175.91  4751.7 1173.79  4772.6 1171.96    4801 1171.92  4843.8 1168.85
  4893.1 1167.06  4942.5 1162.78  4950.1 1161.26  4975.1  1160.4  4995.1  1160.3
  4995.6  1159.8  5003.7  1160.3  5020.7 1163.51  5071.3 1163.91  5086.1 1165.63
  5351.1 1167.04  5624.9 1172.41  5675.4 1175.92    5688 1174.88  5702.5 1177.64
  5724.6 1179.56  5732.1 1179.18  5827.9 1185.89  5905.2 1188.95  5968.8 1190.69
#Mann= 6 ,-1 , 0
  4609.8    .035       0  4975.1     .07       0  4995.1     .05       0
  5003.7     .07       0  5827.9     .12       0  5905.2     .07       0
Bank Sta=4995.1,5003.7
XS Rating Curve= 0 ,0
Exp/Cntr=0.3,0.1

Type RM Length L Ch R = 1 ,13049   ,468,468,468
BEGIN DESCRIPTION:
WALTER CREEK 27.0
END DESCRIPTION:
XS GIS Cut Line= 3
      2119525.03     13858875.01        2120975.       13859275.
      2121674.96     13859075.01
#Sta/Elev= 30
    3501 1197.38  3519.9 1196.45  3573.6 1194.62  3604.7 1190.72  3701.7 1186.06
  3716.3 1185.75  3750.3 1184.01  3779.4 1178.82    3819 1175.23  3926.3 1168.77
  4144.1 1163.43  4205.3 1163.25  4749.4 1161.54  4850.8 1157.93  4874.5 1158.05
  4880.6 1159.13  4959.3 1157.42  4959.8 1156.92    4968 1157.42  5067.5 1161.09
  5133.8 1160.89  5150.7 1158.28  5167.6 1159.31  5337.9  1160.9  5410.7 1164.05
  5473.1 1168.25  5571.4 1178.18  5597.9 1181.99  5618.7 1183.59  5733.1 1188.21
#Mann= 10 ,-1 , 0
    3501     .12       0  3519.9    .035       0  3701.7     .07       0
  3716.3    .035       0  4205.3     .07       0  4749.4    .035       0
  4850.8     .07       0  4959.3     .05       0    4968     .07       0
  5571.4     .12       0
Bank Sta=4959.3,4968
XS Rating Curve= 0 ,0
Exp/Cntr=0.3,0.1

Type RM Length L Ch R = 1 ,12581   ,711,711,711
BEGIN DESCRIPTION:
WALTER CREEK 26.0
END DESCRIPTION:
XS GIS Cut Line= 3
      2119789.21     13859189.22        2121025.       13859725.
      2121879.62     13859332.92
#Sta/Elev= 30
  3653.1 1177.25  3710.1 1171.88  3730.4 1169.93  3759.4 1168.97  3777.3 1167.16
    3812 1165.84  3922.1 1163.01  4109.6 1160.94    4162 1161.53  4226.2 1160.61
  4542.3 1159.52  4886.2 1159.49  4945.5 1155.71  4997.3 1154.89  5031.8 1155.32
  5121.1 1158.84  5196.4 1157.43  5242.1 1157.92  5255.2 1155.05  5268.4 1154.81
  5268.9 1154.31  5277.1 1154.81  5295.7 1157.22  5311.2 1158.09  5327.5    1159
  5462.1 1164.27  5616.6 1172.32  5685.6 1174.13  5869.2 1181.16  5940.3 1186.12
#Mann= 9 ,-1 , 0
  3653.1     .12       0  3710.1     .07       0  3759.4    .035       0
  3922.1     .07       0  5196.4    .035       0  5268.4     .05       0
  5277.1    .035       0  5311.2     .07       0  5327.5     .12       0
Bank Sta=5268.4,5277.1
XS Rating Curve= 0 ,0
Exp/Cntr=0.3,0.1

Type RM Length L Ch R = 1 ,11870   ,254,254,254
BEGIN DESCRIPTION:
WALTER CREEK 25.5
END DESCRIPTION:
XS GIS Cut Line= 3
      2119763.28     13859285.38      2121174.53     13860385.19
      2122331.03     13860525.66
#Sta/Elev= 30
  3210.8 1177.38  3247.8 1173.39  3268.6 1172.62  3283.1 1170.06  3304.9 1169.42
    3310 1169.16  3403.4 1163.43    3568 1160.07  3973.7 1159.13  4130.7 1157.15
  4467.7 1157.09  4470.1 1157.07  4665.4 1156.27  4772.4 1153.12  4936.8 1155.37
  4961.1 1154.54  5014.9 1152.48  5015.4 1151.98  5026.3 1152.48  5098.4 1154.42
  5288.1 1158.69  5322.8 1160.27  5380.6 1166.02    5484  1173.7  5645.2 1179.74
  5715.7 1185.19  5836.6 1189.82  6058.2    1194  6128.7 1197.62    6165 1198.06
#Mann= 10 ,-1 , 0
  3210.8     .12       0  3304.9    .035       0    3310     .07       0
  4467.7    .035       0  4470.1     .07       0  4961.1     .12       0
  5014.9     .05       0  5026.3     .12       0  5098.4     .07       0
  5380.6     .12       0
Bank Sta=5014.9,5026.3
XS Rating Curve= 0 ,0
Exp/Cntr=0.3,0.1