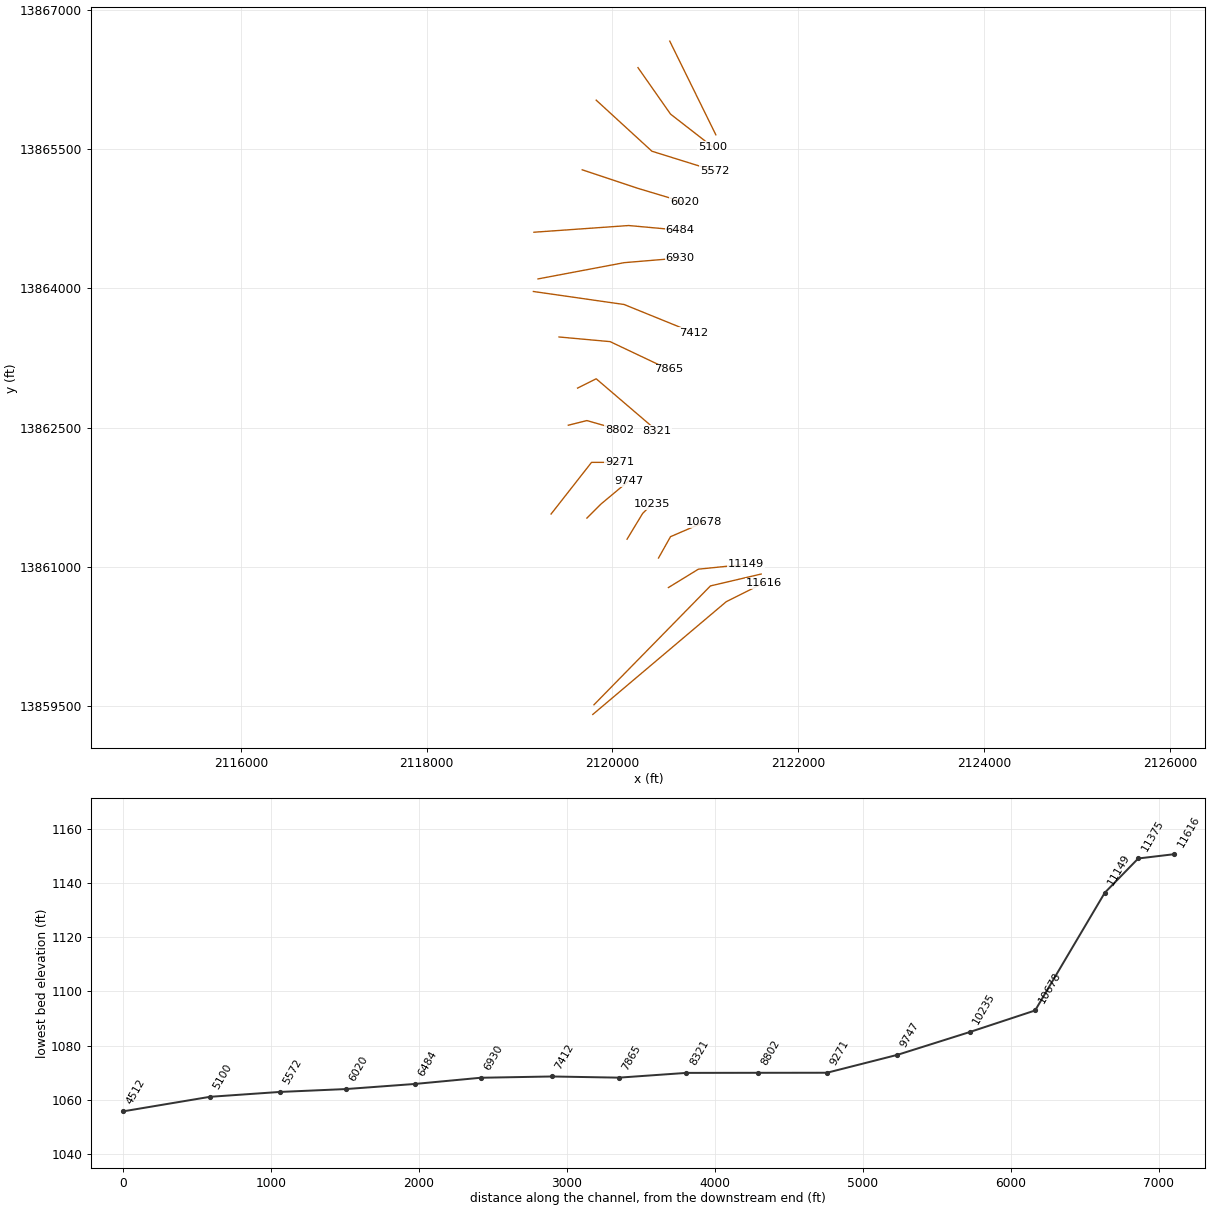
HEC-RAS study WALTER CREEK.prj: WALTER CREEK Base Level Engineering

--- WALTER CREEK.g01 (geometry) --- (continued)

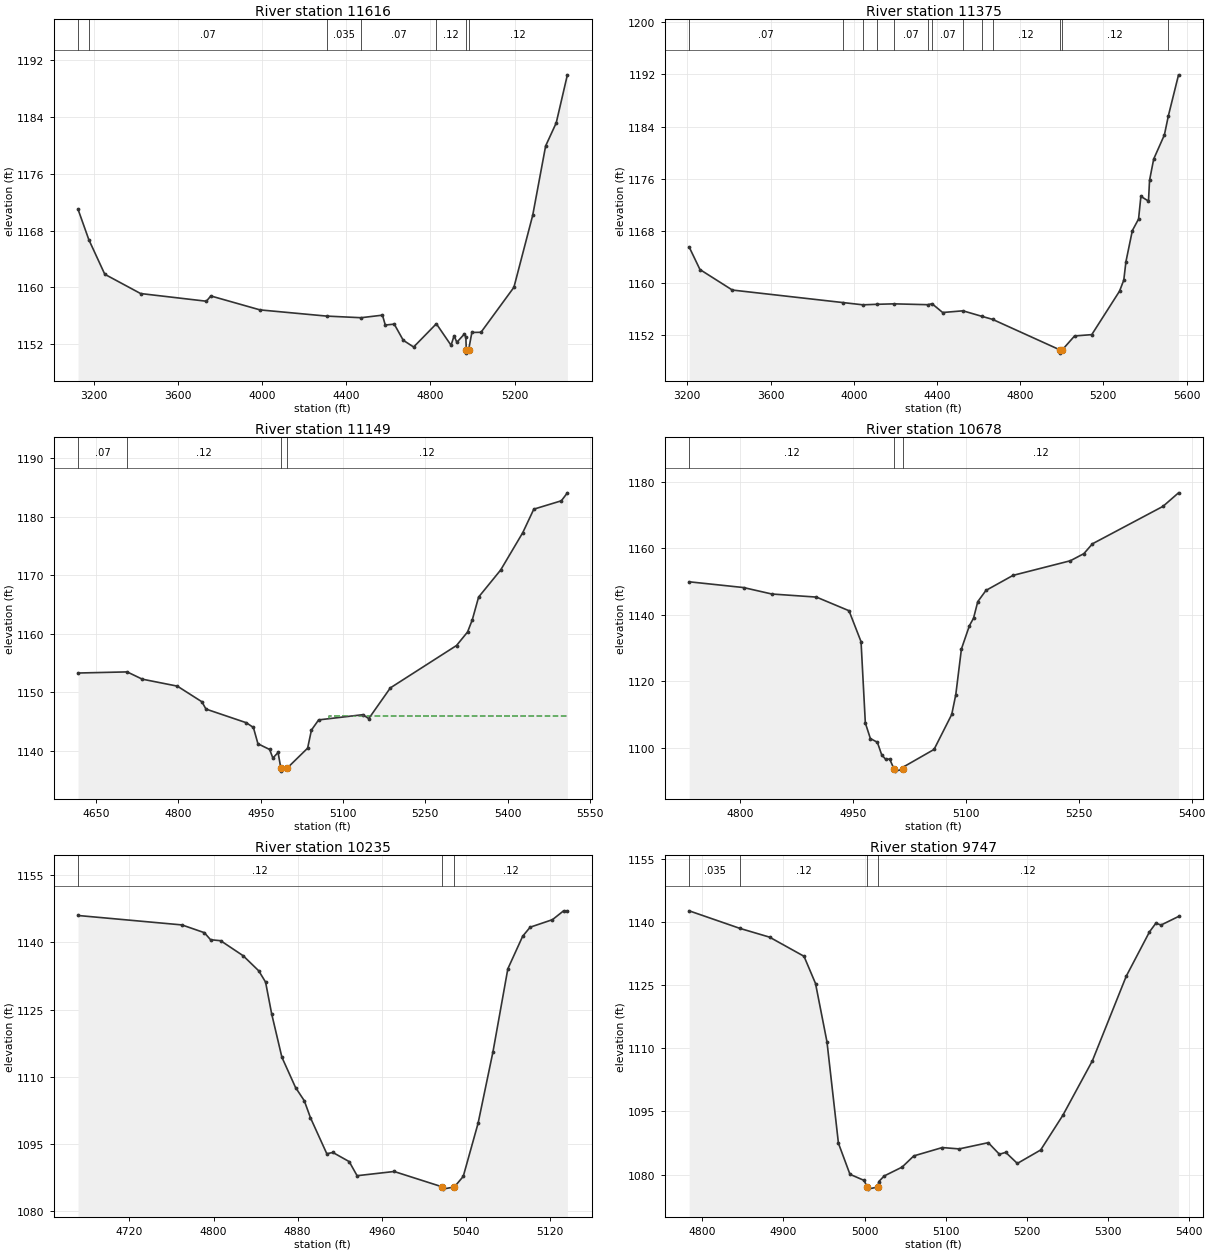
Type RM Length L Ch R = 1 ,11616   ,241,241,241
BEGIN DESCRIPTION:
WALTER CREEK 25.0
END DESCRIPTION:
XS GIS Cut Line= 3
      2119788.73     13859411.16        2121225.       13860625.
      2121624.99     13860824.99
#Sta/Elev= 30
  3123.6    1171    3175 1166.72    3251 1161.85  3421.3 1159.14  3734.1 1158.06
  3755.4  1158.8  3989.4 1156.84  4305.8 1155.97  4469.8 1155.74  4571.8  1156.1
  4585.1 1154.71  4627.7 1154.84  4670.6 1152.57    4720 1151.62    4828 1154.89
  4898.1 1151.86  4912.4 1153.21  4925.5 1152.28  4961.8 1153.47  4968.4 1153.02
  4970.4 1151.26  4970.9 1150.76  4981.8 1151.26    4997 1153.67  5040.4 1153.69
    5197 1160.02  5286.4 1170.15  5347.9  1179.9  5398.2 1183.14  5451.3  1189.9
#Mann= 7 ,-1 , 0
  3123.6     .12       0    3175     .07       0  4305.8    .035       0
  4469.8     .07       0    4828     .12       0  4970.4     .05       0
  4981.8     .12       0
Bank Sta=4970.4,4981.8
XS Rating Curve= 0 ,0
Exp/Cntr=0.3,0.1

Type RM Length L Ch R = 1 ,11375   ,226,226,226
BEGIN DESCRIPTION:
WALTER CREEK 24.5
END DESCRIPTION:
XS GIS Cut Line= 3
      2119801.33     13859515.26      2121054.62     13860794.84
      2121601.23     13860922.85
#Sta/Elev= 30
  3208.9 1165.49  3260.8 1162.03  3416.4 1158.88    3950 1156.95  4044.2 1156.61
  4110.8 1156.69  4193.5 1156.76  4356.8 1156.63  4376.4 1156.78  4427.5 1155.43
  4525.1 1155.69  4617.2 1154.83  4667.1 1154.38    4991 1149.69  4991.5 1149.19
  5002.4 1149.69  5061.7 1151.83  5144.2 1152.03  5277.7 1158.71  5298.2 1160.41
  5308.5 1163.24  5339.3 1168.01  5369.2 1169.79  5380.4 1173.27  5416.9 1172.54
    5422 1175.73    5442 1179.01  5493.4 1182.71  5512.6 1185.66  5561.4 1191.94
#Mann= 13 ,-1 , 0
  3208.9     .07       0    3950    .035       0  4044.2     .07       0
  4110.8    .035       0  4193.5     .07       0  4356.8    .035       0
  4376.4     .07       0  4525.1    .035       0  4617.2     .07       0
  4667.1     .12       0    4991     .05       0  5002.4     .12       0
  5512.6     .07       0
Bank Sta=4991,5002.4
XS Rating Curve= 0 ,0
Exp/Cntr=0.3,0.1

Type RM Length L Ch R = 1 ,11149   ,471,471,471
BEGIN DESCRIPTION:
WALTER CREEK 24.0
END DESCRIPTION:
XS GIS Cut Line= 3
      2120602.58     13860777.27        2120925.       13860975.
      2121435.91     13861027.28
#Sta/Elev= 30
  4617.2 1153.29  4706.7 1153.48  4734.3 1152.24  4798.2 1151.05  4842.9 1148.38
  4850.4 1147.13  4923.8  1144.8  4936.8 1143.99  4945.1  1141.2  4966.4 1140.23
  4972.3 1138.76  4981.8 1139.72  4986.8 1137.03  4987.3 1136.53  4998.2 1137.03
  5035.6 1140.45  5042.6 1143.55  5055.7 1145.28  5136.2 1146.17    5147  1145.5
  5186.4 1150.75    5307 1157.99  5327.1  1160.3  5335.7 1162.37  5347.2 1166.26
  5387.5  1170.9  5427.7 1177.27  5447.8 1181.28    5498 1182.71    5509 1184.07
#Mann= 4 ,-1 , 0
  4617.2     .07       0  4706.7     .12       0  4986.8     .05       0
  4998.2     .12       0
#XS Ineff= 2 , 0
       0                 5075.46       0    1146
Permanent Ineff=
       F       F
Bank Sta=4986.8,4998.2
XS Rating Curve= 0 ,0
Exp/Cntr=0.3,0.1

Type RM Length L Ch R = 1 ,10678   ,443,443,443
BEGIN DESCRIPTION:
WALTER CREEK 23.0
END DESCRIPTION:
XS GIS Cut Line= 3
      2120495.84       13861095.        2120625.       13861325.
      2120980.06     13861477.74
#Sta/Elev= 30
  4732.3 1149.88  4804.5 1148.15  4842.1 1146.21  4901.4 1145.28  4944.7 1141.18
  4960.7 1131.88  4966.4 1107.44  4973.1 1102.76  4982.4 1101.64  4988.1 1097.89
  4993.2 1096.57  4998.8 1096.57  5004.8 1093.47  5005.3 1092.97  5016.3 1093.47
  5017.9 1094.34  5057.7 1099.49  5081.2    1110  5086.6 1115.96  5094.1  1129.7
  5104.7 1136.68  5110.2 1138.95  5115.8 1143.91  5126.7 1147.29  5162.7 1151.81
  5238.8  1156.2  5256.8 1158.34  5268.2  1161.3  5361.9 1172.55  5382.6 1176.62
#Mann= 3 ,-1 , 0
  4732.3     .12       0  5004.8     .05       0  5016.3     .12       0
Bank Sta=5004.8,5016.3
XS Rating Curve= 0 ,0
Exp/Cntr=0.3,0.1

Type RM Length L Ch R = 1 ,10235   ,488,488,488
BEGIN DESCRIPTION:
WALTER CREEK 22.0
END DESCRIPTION:
XS GIS Cut Line= 3
      2120157.27     13861298.08        2120325.       13861575.
      2120425.02     13861675.02
#Sta/Elev= 30
  4671.2 1145.95    4770 1143.85  4791.3 1142.12  4797.2 1140.55  4806.8 1140.33
  4828.2 1136.98    4843 1133.62  4849.5 1131.11  4855.3 1124.02    4865 1114.37
    4878 1107.61  4886.3 1104.67  4892.2 1100.86  4907.7 1092.86  4913.5 1093.14
    4929  1091.1  4936.5 1087.96  4971.7  1088.9  5017.5 1085.47    5018 1084.97
    5029 1085.47  5037.4  1087.8  5051.5 1099.64  5065.7 1115.62  5079.8 1134.07
  5093.9 1141.33    5101 1143.34  5122.2 1145.02  5132.8 1146.99  5136.4 1146.99
#Mann= 3 ,-1 , 0
  4671.2     .12       0  5017.5     .05       0    5029     .12       0
Bank Sta=5017.5,5029
XS Rating Curve= 0 ,0
Exp/Cntr=0.3,0.1

Type RM Length L Ch R = 1 ,9747    ,476,476,476
BEGIN DESCRIPTION:
WALTER CREEK 21.0
END DESCRIPTION:
XS GIS Cut Line= 3
      2119725.01     13861525.01        2119875.       13861675.
      2120174.97     13861924.98
#Sta/Elev= 30
    4784 1142.63  4846.5 1138.46    4883 1136.38  4925.4 1131.84  4939.6 1125.37
  4953.7 1111.51  4967.8 1087.45    4982 1080.07  4999.4 1078.62  5003.2 1077.05
  5003.7 1076.55  5016.3 1077.05  5017.6 1078.36  5024.1 1079.67  5046.2 1081.78
  5060.6 1084.44  5095.7 1086.42  5116.5  1086.1  5152.3 1087.58    5166 1084.83
  5173.8 1085.28  5188.1 1082.65  5216.8 1085.84  5244.1 1094.07  5280.5 1107.02
  5322.2 1127.11  5350.8 1137.63  5358.6 1139.67  5365.2 1139.27  5386.6 1141.29
#Mann= 4 ,-1 , 0
    4784    .035       0  4846.5     .12       0  5003.2     .05       0
  5016.3     .12       0
Bank Sta=5003.2,5016.3
XS Rating Curve= 0 ,0
Exp/Cntr=0.3,0.1

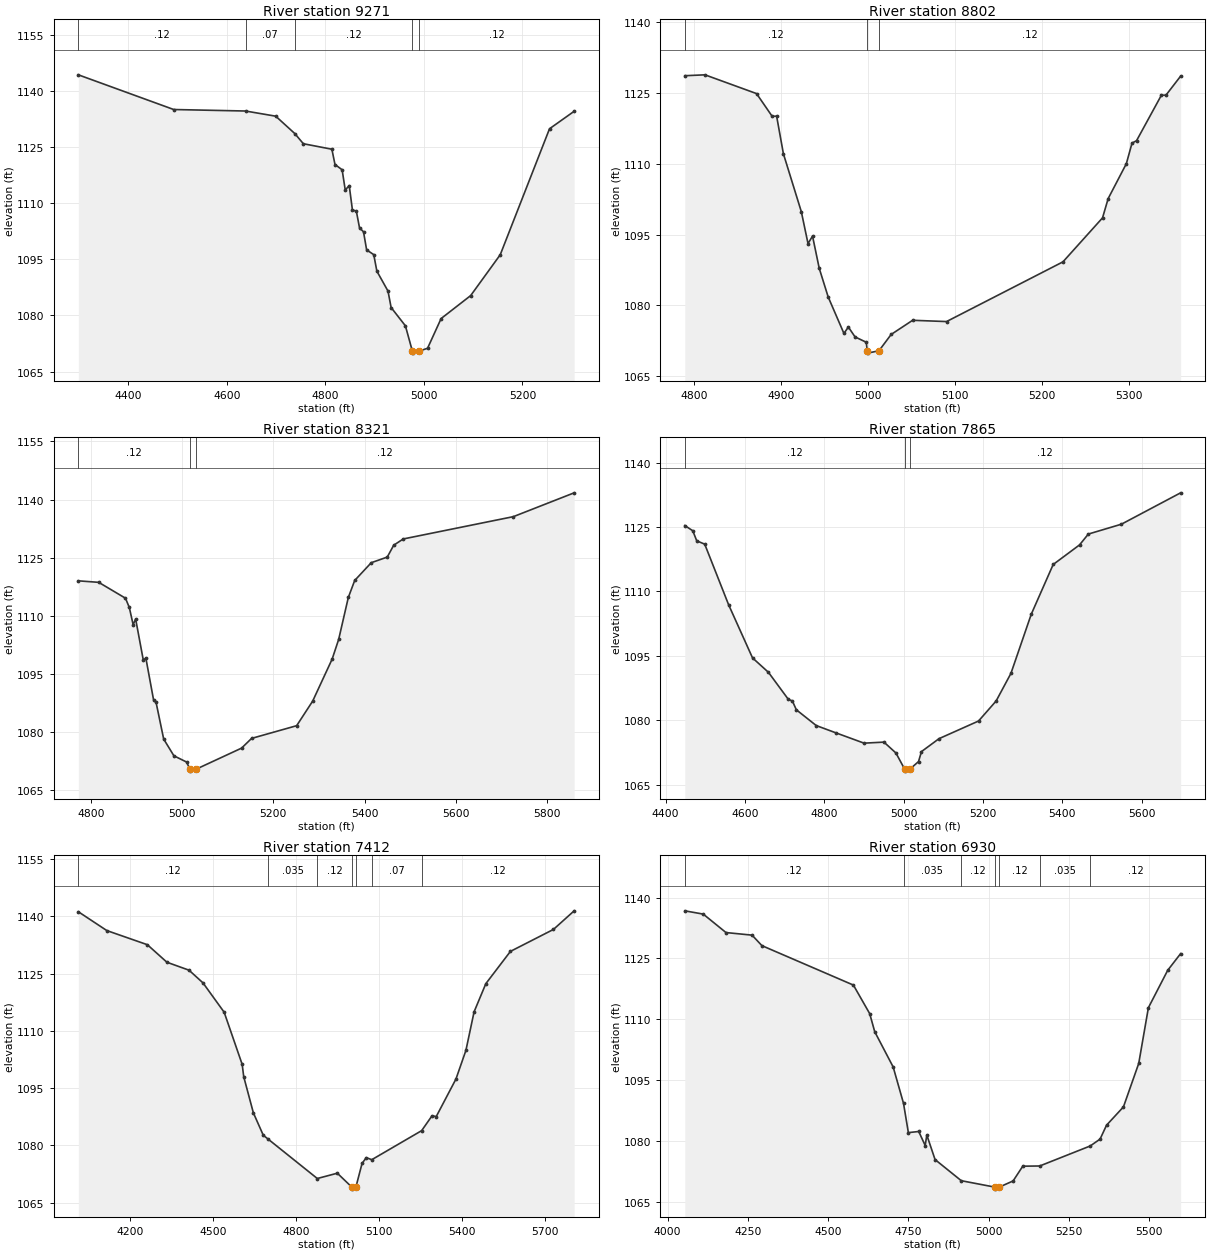
Type RM Length L Ch R = 1 ,9271    ,469,469,469
BEGIN DESCRIPTION:
WALTER CREEK 20.0
END DESCRIPTION:
XS GIS Cut Line= 3
      2119339.57     13861568.93        2119775.       13862125.
      2120075.03       13862125.
#Sta/Elev= 30
  4298.7 1144.29  4492.3 1135.02    4638 1134.62  4699.3 1133.24    4738  1128.6
  4755.4 1125.88  4813.3 1124.41  4819.6 1120.33  4834.1 1118.92  4840.4 1113.51
  4848.5 1114.69  4854.9 1108.25    4863 1107.82  4869.4 1103.39  4877.5 1102.35
  4883.8 1097.52  4898.3 1096.24  4904.6 1091.83  4927.2  1086.5  4933.5 1082.12
  4962.5 1077.23  4976.7 1070.43  4977.2 1069.93  4989.9 1070.43  5007.5 1071.24
    5035 1079.17    5095 1085.31    5155 1096.22    5255 1129.88    5305 1134.55
#Mann= 5 ,-1 , 0
  4298.7     .12       0    4638     .07       0    4738     .12       0
  4976.7     .05       0  4989.9     .12       0
Bank Sta=4976.7,4989.9
XS Rating Curve= 0 ,0
Exp/Cntr=0.3,0.1

Type RM Length L Ch R = 1 ,8802    ,481,481,481
BEGIN DESCRIPTION:
WALTER CREEK 19.0
END DESCRIPTION:
XS GIS Cut Line= 3
      2119525.01       13862525.        2119725.       13862575.
      2120075.05     13862474.99
#Sta/Elev= 30
  4789.7 1128.62  4812.9 1128.81  4872.2 1124.84  4890.2 1120.02  4895.3 1120.07
  4903.1  1112.1  4923.7 1099.85  4931.4 1093.09  4936.6 1094.68  4944.3 1087.86
  4954.6 1081.79  4972.7 1074.08  4977.8 1075.43  4985.5 1073.34  4998.4 1072.21
  4999.5 1070.41    5000 1069.91    5013 1070.41    5027 1073.86  5051.7 1076.86
  5090.7 1076.59  5224.6 1089.23  5270.1 1098.54  5276.6 1102.63  5297.5 1110.01
    5304 1114.36  5309.2 1114.87  5337.8  1124.5    5343  1124.5  5359.9 1128.53
#Mann= 3 ,-1 , 0
  4789.7     .12       0  4999.5     .05       0    5013     .12       0
Bank Sta=4999.5,5013
XS Rating Curve= 0 ,0
Exp/Cntr=0.3,0.1

Type RM Length L Ch R = 1 ,8321    ,456,456,456
BEGIN DESCRIPTION:
WALTER CREEK 18.0
END DESCRIPTION:
XS GIS Cut Line= 3
      2119625.03     13862925.02        2119825.       13863025.
      2120481.37     13862463.41
#Sta/Elev= 30
  4772.3 1119.01    4817 1118.62  4875.7 1114.52  4884.1 1112.13  4892.5 1107.69
    4898 1109.15  4914.8 1098.53  4920.4 1099.08  4937.2 1088.33  4942.8 1087.63
  4959.5 1078.15  4981.9 1073.84  5009.6 1072.23  5017.1 1070.38  5017.6 1069.88
  5030.6 1070.38  5130.3 1075.82  5152.3 1078.33  5251.1 1081.61  5286.2 1087.95
    5329 1098.82  5343.3 1103.91  5364.4 1114.71  5378.4  1119.1  5414.7 1123.69
  5449.8 1125.14    5464 1128.21  5484.9 1129.82  5726.4 1135.58  5859.7 1141.73
#Mann= 3 ,-1 , 0
  4772.3     .12       0  5017.1     .05       0  5030.6     .12       0
Bank Sta=5017.1,5030.6
XS Rating Curve= 0 ,0
Exp/Cntr=0.3,0.1

Type RM Length L Ch R = 1 ,7865    ,453,453,453
BEGIN DESCRIPTION:
WALTER CREEK 17.0
END DESCRIPTION:
XS GIS Cut Line= 3
      2119425.02       13863475.        2119975.       13863425.
      2120605.22     13863126.24
#Sta/Elev= 30
  4448.4 1125.36  4468.5 1124.14  4478.5 1121.79  4498.6 1121.02  4558.8  1106.9
  4619.1 1094.51  4659.2 1091.15  4709.5 1084.83  4719.5 1084.48  4729.5 1082.42
  4779.7 1078.74  4829.9 1077.02  4900.2 1074.64  4950.4 1074.88  4980.6 1072.34
  5002.3 1068.62  5002.8 1068.12  5016.3 1068.62  5037.5 1070.35  5044.9 1072.67
  5089.2 1075.69  5188.8  1079.8  5233.1 1084.47  5270.4  1090.9  5321.6 1104.68
  5376.9 1116.28  5443.3 1120.84  5465.5 1123.37  5548.9 1125.67  5698.1 1132.98
#Mann= 3 ,-1 , 0
  4448.4     .12       0  5002.3     .05       0  5016.3     .12       0
Bank Sta=5002.3,5016.3
XS Rating Curve= 0 ,0
Exp/Cntr=0.3,0.1

Type RM Length L Ch R = 1 ,7412    ,482,482,482
BEGIN DESCRIPTION:
WALTER CREEK 16.0
END DESCRIPTION:
XS GIS Cut Line= 3
      2119149.48     13863964.78        2120125.       13863825.
      2120870.38     13863522.26
#Sta/Elev= 30
  4014.5 1141.17  4117.4 1136.24  4263.7 1132.54  4334.3 1127.95  4414.1 1125.87
  4464.6 1122.54    4541 1114.86    4606 1101.21  4611.6 1097.98  4646.4 1088.52
  4682.2 1082.66    4698 1081.74  4877.2 1071.33  4949.5 1072.72  5002.3 1069.05
  5002.8 1068.55  5016.4 1069.05  5038.8 1075.28    5054 1076.79    5074 1076.26
  5253.9 1083.86  5291.4 1087.75  5306.6 1087.55  5377.8 1097.38  5413.7 1104.87
  5443.2 1114.96  5485.7 1122.35  5574.4 1130.79  5729.7 1136.54  5804.5 1141.41
#Mann= 7 ,-1 , 0
  4014.5     .12       0    4698    .035       0  4877.2     .12       0
  5002.3     .05       0  5016.4     .12       0    5074     .07       0
  5253.9     .12       0
Bank Sta=5002.3,5016.4
XS Rating Curve= 0 ,0
Exp/Cntr=0.3,0.1

Type RM Length L Ch R = 1 ,6930    ,446,446,446
BEGIN DESCRIPTION:
WALTER CREEK 15.0
END DESCRIPTION:
XS GIS Cut Line= 3
      2119198.95      13864100.2        2120125.       13864275.
      2120725.02       13864325.
#Sta/Elev= 30
  4053.5 1136.74    4111 1135.93  4181.8 1131.38  4263.1 1130.74  4293.7 1128.15
  4578.7 1118.42  4629.5 1111.37  4645.1 1106.92  4702.6 1098.21  4734.8 1089.24
  4749.9 1082.02  4782.2  1082.3  4802.3 1078.84  4807.4 1081.42  4833.1 1075.37
  4914.7 1070.16  5018.9 1068.58  5019.4 1068.08  5033.1 1068.58  5076.2  1070.1
  5106.3 1073.74  5159.1 1073.79  5316.2 1078.72  5347.1 1080.42  5367.2 1083.85
  5419.9 1088.37  5467.5 1099.09  5497.6 1112.84  5557.8 1122.07    5598 1126.18
#Mann= 7 ,-1 , 0
  4053.5     .12       0  4734.8    .035       0  4914.7     .12       0
  5018.9     .05       0  5033.1     .12       0  5159.1    .035       0
  5316.2     .12       0
Bank Sta=5018.9,5033.1
XS Rating Curve= 0 ,0
Exp/Cntr=0.3,0.1

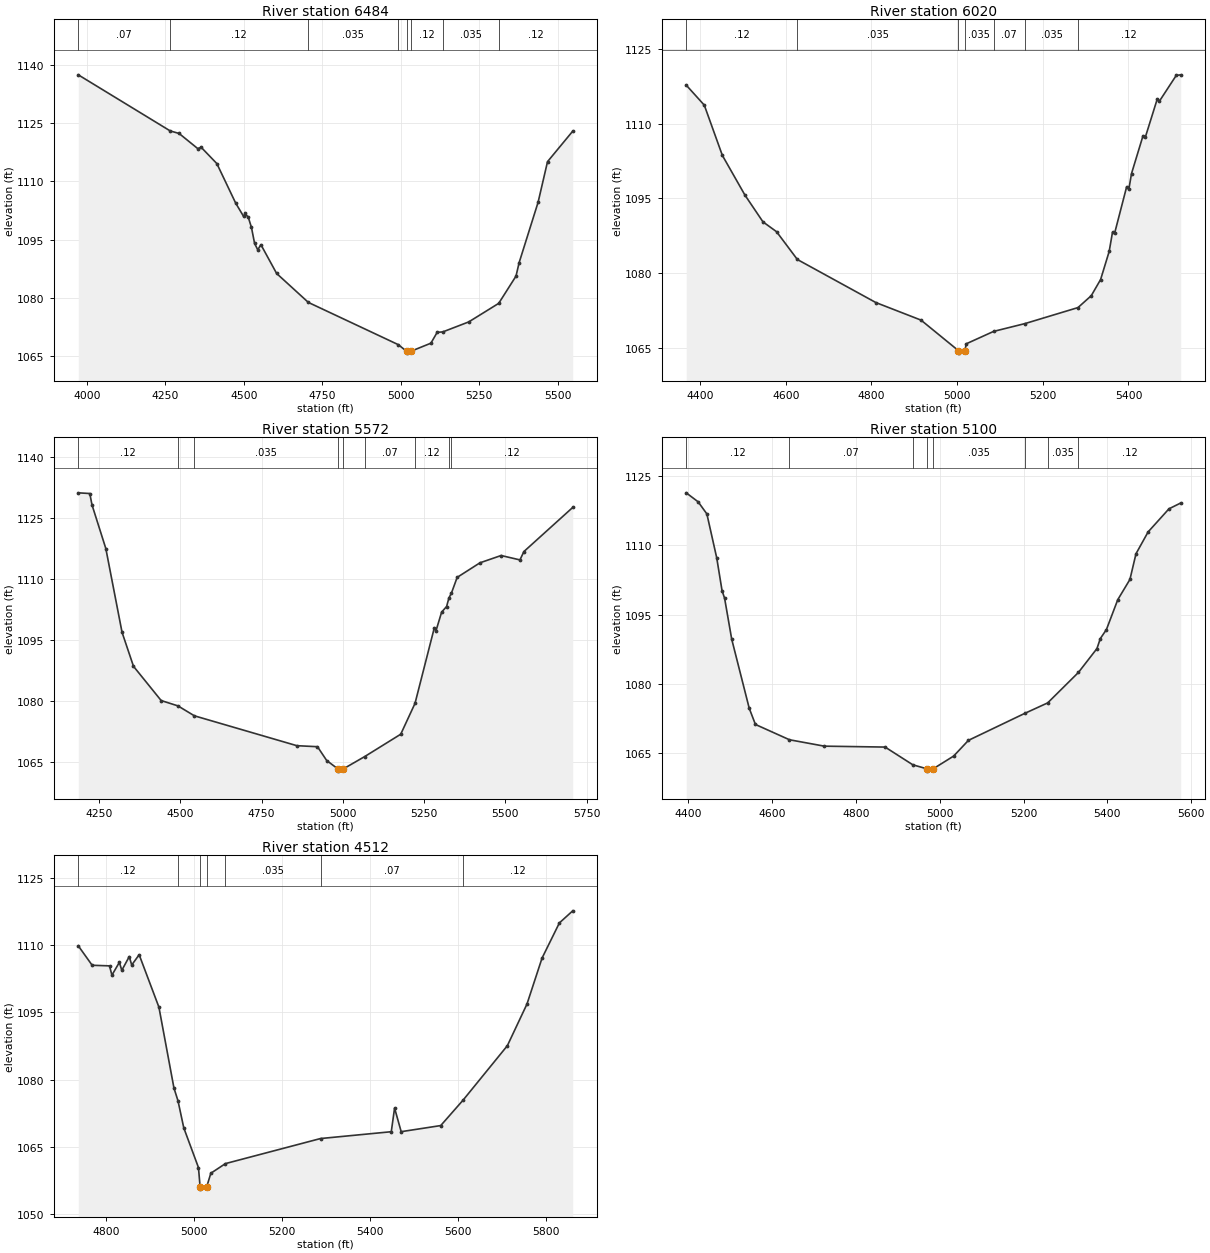
Type RM Length L Ch R = 1 ,6484    ,464,464,464
BEGIN DESCRIPTION:
WALTER CREEK 14.0
END DESCRIPTION:
XS GIS Cut Line= 3
       2119154.7     13864602.81        2120175.       13864675.
      2120724.98       13864625.
#Sta/Elev= 30
    3973 1137.47  4266.1 1123.01  4294.1 1122.37  4353.8 1118.46  4364.3 1118.82
  4414.4 1114.61  4474.6  1104.4  4499.8 1100.98  4504.8 1101.76  4514.7 1100.74
  4524.7 1098.16  4534.7 1094.03  4544.7 1092.41  4554.8 1093.72  4604.9  1086.3
    4706 1078.84  4992.2 1067.97  5018.7 1066.28  5019.2 1065.78  5033.2 1066.28
  5096.3 1068.34  5116.3 1071.14  5134.3 1071.25  5216.8 1073.82  5312.3  1078.6
  5367.4 1085.62  5377.4  1089.1  5437.7 1104.62  5467.8  1115.1  5548.1 1122.96
#Mann= 8 ,-1 , 0
    3973     .07       0  4266.1     .12       0    4706    .035       0
  4992.2     .12       0  5018.7     .05       0  5033.2     .12       0
  5134.3    .035       0  5312.3     .12       0
Bank Sta=5018.7,5033.2
XS Rating Curve= 0 ,0
Exp/Cntr=0.3,0.1

Type RM Length L Ch R = 1 ,6020    ,448,448,448
BEGIN DESCRIPTION:
WALTER CREEK 13.0
END DESCRIPTION:
XS GIS Cut Line= 3
      2119674.96     13865275.01        2120275.       13865075.
      2120774.99       13864925.
#Sta/Elev= 30
  4367.5  1117.8  4409.7 1113.77  4451.9 1103.66  4504.6 1095.68  4546.7  1090.3
  4578.4 1088.32    4627 1082.73  4810.3 1074.07  4915.7 1070.54  5003.1  1064.4
  5003.6  1063.9  5017.8  1064.4  5021.7 1065.79  5085.2 1068.27  5158.4 1069.84
  5282.2 1073.06  5313.2 1075.45    5335  1078.7    5355 1084.34  5362.8 1088.22
    5368  1088.1  5395.9 1097.38  5401.1 1096.94  5407.2 1100.02  5434.1 1107.63
  5439.4 1107.32  5467.2 1114.98  5472.4 1114.58  5511.6 1119.75    5522 1119.87
#Mann= 7 ,-1 , 0
  4367.5     .12       0    4627    .035       0  5003.1    .035       0
  5017.8    .035       0  5085.2     .07       0  5158.4    .035       0
  5282.2     .12       0
Bank Sta=5003.1,5017.8
XS Rating Curve= 0 ,0
Exp/Cntr=0.3,0.1

Type RM Length L Ch R = 1 ,5572    ,472,472,472
BEGIN DESCRIPTION:
WALTER CREEK 12.0
END DESCRIPTION:
XS GIS Cut Line= 3
        2119825.       13866025.        2120425.       13865475.
      2121100.02     13865264.26
#Sta/Elev= 30
  4186.1  1131.2  4221.6 1131.03  4228.3 1128.25  4270.9 1117.51  4320.8 1096.93
    4356 1088.58  4441.1 1080.17  4492.7 1078.86  4543.3 1076.42  4858.5 1069.08
    4922 1068.83  4950.4 1065.43  4985.6 1063.33  4986.1 1062.83  5000.4 1063.33
  5067.1  1066.4  5178.1  1071.9    5222 1079.47  5281.5 1098.07  5286.7 1097.34
  5303.9  1101.9  5319.2 1103.27  5326.2 1105.34  5334.2  1106.6  5351.7 1110.43
  5421.9 1114.01  5486.9  1115.8  5544.8 1114.72  5557.1 1116.78  5707.2 1127.61
#Mann= 9 ,-1 , 0
  4186.1     .12       0  4492.7     .07       0  4543.3    .035       0
  4985.6    .035       0  5000.4    .035       0  5067.1     .07       0
    5222     .12       0  5326.2    .035       0  5334.2     .12       0
Bank Sta=4985.6,5000.4
XS Rating Curve= 0 ,0
Exp/Cntr=0.3,0.1

Type RM Length L Ch R = 1 ,5100    ,588,588,588
BEGIN DESCRIPTION:
WALTER CREEK 11.0
END DESCRIPTION:
XS GIS Cut Line= 3
      2120274.99     13866375.02        2120625.       13865875.
      2121074.97     13865525.02
#Sta/Elev= 30
  4394.8 1121.43  4423.2 1119.48  4444.1 1116.85  4467.6 1107.32  4480.3 1100.21
  4486.4 1098.55  4503.4 1089.66  4545.2 1074.67    4560 1071.16  4641.2 1067.84
  4724.4 1066.45  4869.6 1066.25  4935.8  1062.4  4969.4 1061.53  4969.9 1061.03
  4984.3 1061.53  5033.2  1064.3  5068.5 1067.71  5202.9 1073.56  5257.7 1075.84
  5331.2 1082.46  5375.3 1087.63  5383.4 1089.81  5397.9 1091.75    5425 1098.24
    5454 1102.63  5468.5 1108.21  5497.4 1112.94  5547.2 1117.96  5575.2 1119.22
#Mann= 8 ,-1 , 0
  4394.8     .12       0  4641.2     .07       0  4935.8    .035       0
  4969.4    .035       0  4984.3    .035       0  5202.9     .07       0
  5257.7    .035       0  5331.2     .12       0
Bank Sta=4969.4,4984.3
XS Rating Curve= 0 ,0
Exp/Cntr=0.3,0.1

Type RM Length L Ch R = 1 ,4512    ,772,772,772
BEGIN DESCRIPTION:
WALTER CREEK 10.0
END DESCRIPTION:
XS GIS Cut Line= 2
      2120616.95     13866660.15      2121112.85     13865651.68
#Sta/Elev= 30
  4736.8 1109.85  4768.4 1105.51  4807.8 1105.38  4813.3 1103.31  4830.2 1106.16
  4835.8 1104.39  4852.7 1107.45  4858.3 1105.57  4875.2 1107.86  4920.1 1096.18
  4954.3 1078.15  4963.4 1075.34  4976.6 1069.29    5010 1060.44  5013.7 1056.14
  5014.2 1055.64  5028.7 1056.14  5038.1 1059.18  5071.4 1061.33  5287.4 1066.91
  5448.2 1068.43  5455.7  1073.7  5470.7 1068.44  5560.6  1069.8  5611.5 1075.48
    5712 1087.59  5756.6 1096.87  5790.9 1107.12  5830.3 1114.95  5860.6 1117.64
#Mann= 7 ,-1 , 0
  4736.8     .12       0  4963.4     .07       0  5013.7     .05       0
  5028.7     .07       0  5071.4    .035       0  5287.4     .07       0
  5611.5     .12       0
Bank Sta=5013.7,5028.7
XS Rating Curve= 0 ,0
Exp/Cntr=0.3,0.1