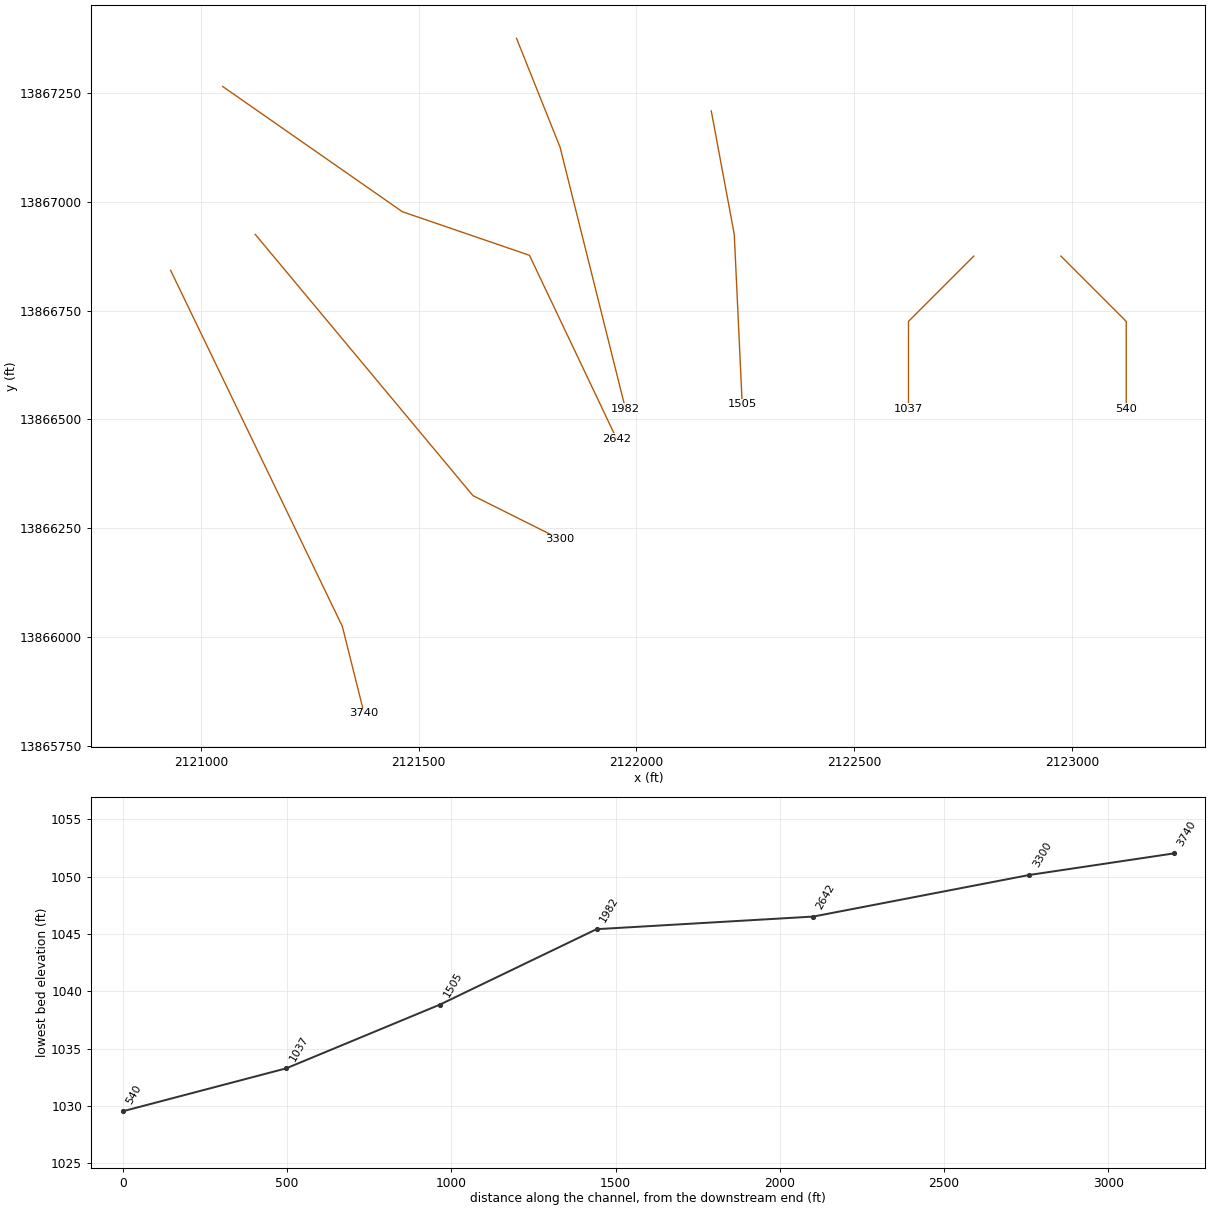
HEC-RAS study WALTER CREEK.prj: WALTER CREEK Base Level Engineering

--- WALTER CREEK.g01 (geometry) --- (continued)

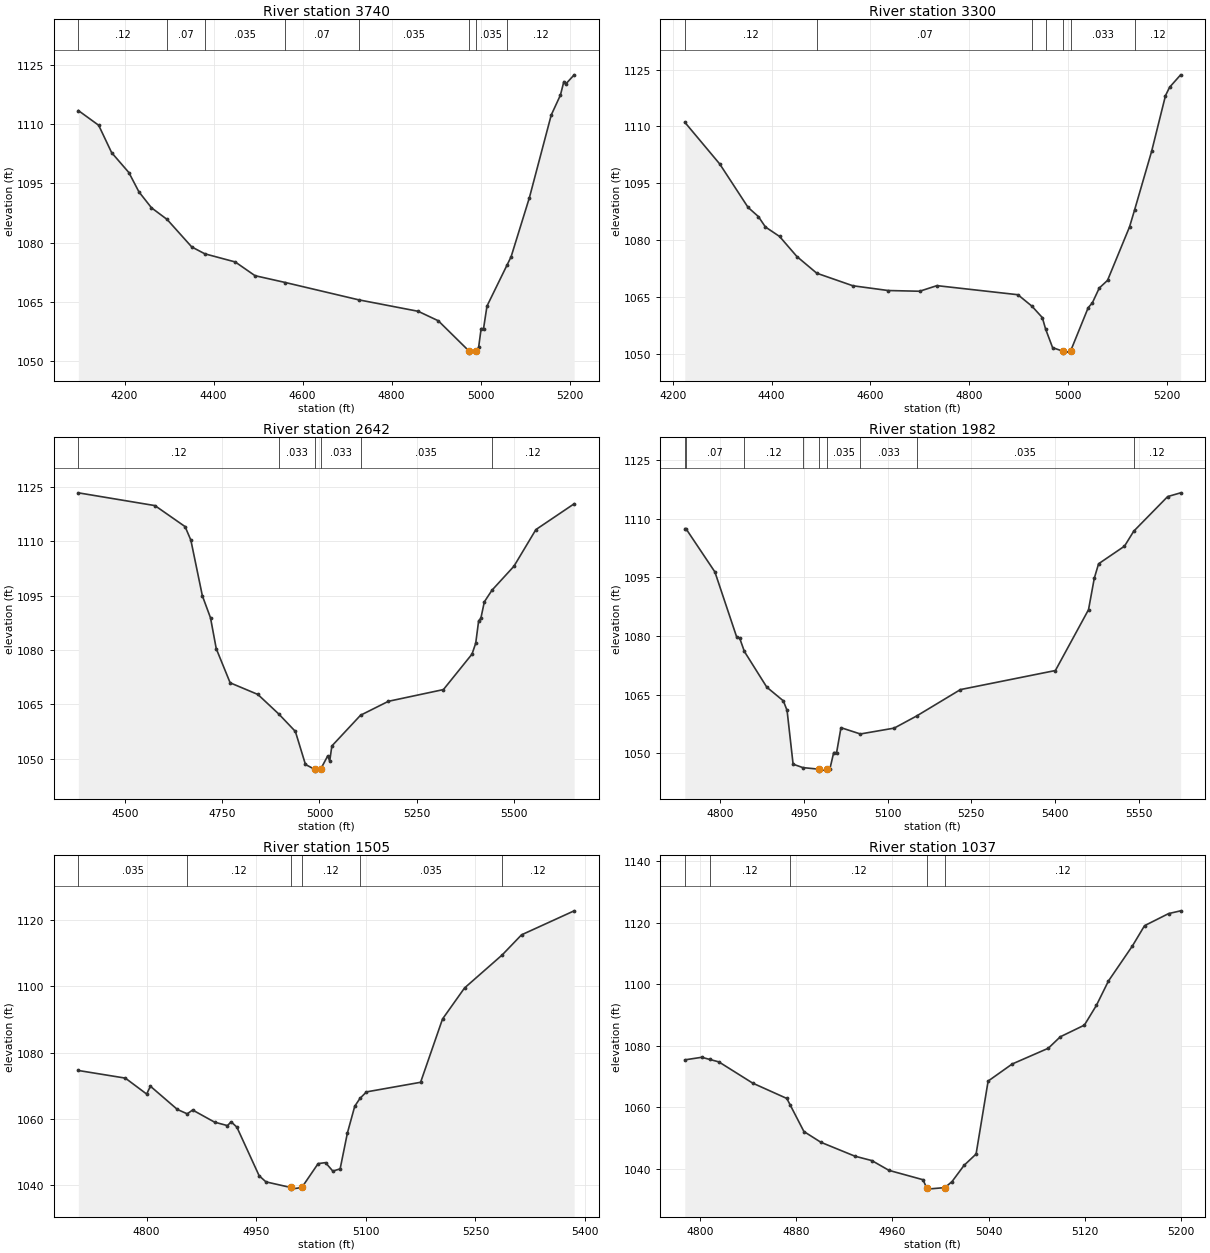
Type RM Length L Ch R = 1 ,3740    ,440,440,440
BEGIN DESCRIPTION:
WALTER CREEK 8.0
END DESCRIPTION:
XS GIS Cut Line= 3
      2120930.74     13866842.37        2121325.       13866025.
      2121374.99     13865825.05
#Sta/Elev= 30
  4096.3  1113.4    4142 1109.67  4171.1 1102.75  4209.8 1097.71  4232.4 1092.83
  4260.6  1088.8  4295.7 1085.85    4351  1078.9  4380.4 1077.16  4448.7  1075.1
  4493.1 1071.63  4561.3  1069.9    4726 1065.52  4859.6 1062.62  4904.8 1060.22
    4974 1052.54  4974.5 1052.04  4989.1 1052.54  4995.3 1053.47    5001 1058.25
  5006.4 1058.25  5014.1 1063.94    5059 1074.28  5068.2 1076.39  5109.4 1091.37
  5158.4 1112.26    5179 1117.29  5186.8 1120.73  5191.9 1120.21  5209.9 1122.43
#Mann= 8 ,-1 , 0
  4096.3     .12       0  4295.7     .07       0  4380.4    .035       0
  4561.3     .07       0    4726    .035       0    4974    .035       0
  4989.1    .035       0    5059     .12       0
Bank Sta=4974,4989.1
XS Rating Curve= 0 ,0
Exp/Cntr=0.3,0.1

Type RM Length L Ch R = 1 ,3300    ,658,658,658
BEGIN DESCRIPTION:
WALTER CREEK 7.0
END DESCRIPTION:
XS GIS Cut Line= 3
        2121125.     13866924.99        2121625.       13866325.
      2121824.98     13866225.01
#Sta/Elev= 30
    4224 1111.12  4294.9 1100.08  4352.2 1088.64    4373 1086.23  4387.4 1083.46
    4416 1080.97  4451.1 1075.67  4491.4 1071.26  4564.4 1067.95    4636 1066.69
  4699.8  1066.5  4734.9 1067.98  4898.9 1065.58  4927.3 1062.56  4948.4 1059.54
    4955 1056.53  4969.2 1051.61  4990.3 1050.66  4990.8 1050.16  5005.5 1050.66
  5041.4 1062.18  5049.7 1063.42  5063.7 1067.34  5080.5 1069.37  5125.2 1083.53
  5135.5 1088.04  5169.9 1103.47  5197.9 1118.14  5206.3 1120.37  5228.6 1123.64
#Mann= 7 ,-1 , 0
    4224     .12       0  4491.4     .07       0  4927.3    .035       0
    4955    .033       0  4990.3    .033       0  5005.5    .033       0
  5135.5     .12       0
Bank Sta=4990.3,5005.5
XS Rating Curve= 0 ,0
Exp/Cntr=0.3,0.1

Type RM Length L Ch R = 1 ,2642    ,660,660,660
BEGIN DESCRIPTION:
WALTER CREEK 5.0
END DESCRIPTION:
XS GIS Cut Line= 4
      2121050.36     13867264.45      2121462.93      13866976.9
      2121754.65     13866876.88      2121954.68     13866455.98
#Sta/Elev= 30
  4378.8 1123.42  4576.2 1119.89  4653.8 1114.09  4668.7 1110.34  4698.3 1094.98
  4719.3 1088.88  4734.1 1080.36  4769.9 1070.93  4841.4 1067.71  4895.2 1062.31
  4937.9  1057.5  4963.9 1048.37  4987.6 1047.03  4988.1 1046.53  5002.8 1047.03
  5021.2 1050.73  5026.4 1049.31  5031.9 1053.48  5105.8 1061.97  5177.5 1065.82
  5319.3 1069.06    5393 1078.87  5402.5 1081.87  5410.1 1088.09  5415.7 1088.72
  5424.7  1093.3  5444.2 1096.49    5501 1103.14  5557.5 1113.26  5656.1 1120.39
#Mann= 6 ,-1 , 0
  4378.8     .12       0  4895.2    .033       0  4987.6    .033       0
  5002.8    .033       0  5105.8    .035       0  5444.2     .12       0
Bank Sta=4987.6,5002.8
XS Rating Curve= 0 ,0
Exp/Cntr=0.3,0.1

Type RM Length L Ch R = 1 ,1982    ,477,477,477
BEGIN DESCRIPTION:
WALTER CREEK 4.0
END DESCRIPTION:
XS GIS Cut Line= 3
        2121725.     13867375.01        2121825.       13867125.
      2121974.99     13866525.03
#Sta/Elev= 30
    4737 1107.48  4739.1 1107.48  4790.9 1096.41  4829.9 1079.75  4835.3 1079.44
  4843.7 1076.05  4883.8 1066.92  4913.4 1063.42  4920.1 1060.97  4930.9 1047.21
  4948.4 1046.33  4977.1 1045.93  4977.6 1045.43  4992.3 1045.93  4996.8 1046.02
  5003.6 1050.19  5008.8 1050.19  5016.6 1056.55  5051.3 1054.94  5111.9 1056.44
  5151.9 1059.53  5230.5  1066.3  5400.5 1071.18  5459.8 1086.75  5470.1 1094.78
  5477.8  1098.5  5524.2 1103.01  5540.8 1106.85  5601.5  1115.7  5624.7 1116.66
#Mann= 9 ,-1 , 0
    4737    .035       0  4739.1     .07       0  4843.7     .12       0
  4948.4    .035       0  4977.1    .035       0  4992.3    .035       0
  5051.3    .033       0  5151.9    .035       0  5540.8     .12       0
Bank Sta=4977.1,4992.3
XS Rating Curve= 0 ,0
Exp/Cntr=0.3,0.1

Type RM Length L Ch R = 1 ,1505    ,468,468,468
BEGIN DESCRIPTION:
WALTER CREEK 3.0
END DESCRIPTION:
XS GIS Cut Line= 3
      2122172.17     13867208.22        2122225.       13866925.
      2122243.23     13866535.13
#Sta/Elev= 30
  4706.7 1074.63    4771 1072.33  4800.2 1067.52  4805.3 1069.89  4842.2 1062.88
  4855.7 1061.56  4863.1 1062.71  4893.1 1059.05  4910.7 1058.01  4915.8 1059.14
  4923.6 1057.55  4954.1 1042.88  4963.4 1041.04  4997.2 1039.35  4997.7 1038.85
  5012.5 1039.35  5034.8 1046.55  5044.9 1046.84  5054.9 1044.29  5064.9 1044.96
  5074.9 1055.83  5084.9 1063.85    5092  1066.2  5100.9 1068.17    5175 1071.07
    5205 1090.16  5235.1 1099.51  5286.7 1109.49  5313.1 1115.54  5385.1 1122.78
#Mann= 6 ,-1 , 0
  4706.7    .035       0  4855.7     .12       0  4997.2     .05       0
  5012.5     .12       0    5092    .035       0  5286.7     .12       0
Bank Sta=4997.2,5012.5
XS Rating Curve= 0 ,0
Exp/Cntr=0.3,0.1

Type RM Length L Ch R = 1 ,1037    ,497,497,497
BEGIN DESCRIPTION:
WALTER CREEK 2.0
END DESCRIPTION:
XS GIS Cut Line= 3
      2122774.98     13866874.98        2122625.       13866725.
        2122625.     13866525.01
#Sta/Elev= 30
  4787.5 1075.39  4801.6 1076.23  4808.4 1075.51  4815.8 1074.73    4844  1067.8
  4872.3 1062.82  4875.2 1060.62  4886.5 1052.05  4900.6 1048.55  4928.9 1044.02
    4943 1042.58  4957.2  1039.4  4985.5 1036.35  4988.4 1033.79  4988.9 1033.29
  5003.7 1033.79  5009.6 1035.75  5019.6 1041.03  5029.6 1044.72  5039.6 1068.48
  5059.6 1074.04  5089.6 1079.17  5099.6 1082.91  5119.6  1086.7  5129.6 1093.14
  5139.6 1101.07  5159.6 1112.54  5169.6 1119.09  5189.6 1123.03  5199.6 1123.93
#Mann= 5 ,-1 , 0
  4787.5     .12       0  4808.4     .12       0  4875.2     .12       0
  4988.4     .05       0  5003.7     .12       0
Bank Sta=4988.4,5003.7
XS Rating Curve= 0 ,0
Exp/Cntr=0.3,0.1

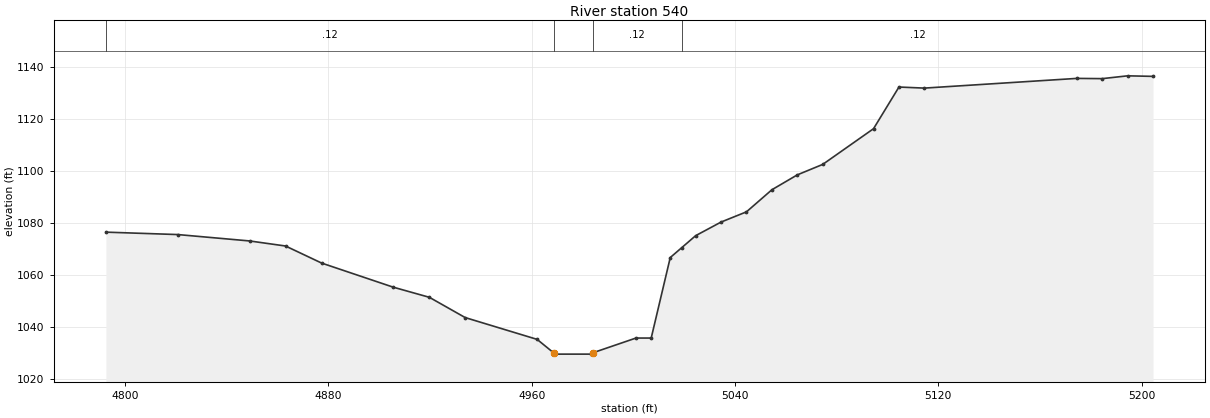
Type RM Length L Ch R = 1 ,540     ,0,0,0
BEGIN DESCRIPTION:
WALTER CREEK 1.0
END DESCRIPTION:
XS GIS Cut Line= 3
        2122975.       13866875.        2123125.       13866725.
        2123125.     13866525.04
#Sta/Elev= 30
  4792.4 1076.44  4820.7 1075.51    4849 1073.05  4863.1 1071.11  4877.3 1064.55
  4905.5 1055.28  4919.7 1051.39  4933.8  1043.6  4962.1 1035.22  4968.6 1030.05
  4969.1 1029.55  4983.5 1029.55    4984 1030.05    5001 1035.73    5007 1035.73
  5014.5 1066.68    5019 1070.46  5024.5 1075.09  5034.5 1080.32  5044.5 1084.25
  5054.5 1092.74  5064.5 1098.46  5074.5 1102.48  5094.5 1116.21  5104.5 1132.22
  5114.5 1131.81  5174.5 1135.54  5184.5 1135.45  5194.5 1136.53  5204.5 1136.32
#Mann= 4 ,-1 , 0
  4792.4     .12       0  4968.6     .05       0    4984     .12       0
    5019     .12       0
Bank Sta=4968.6,4984
XS Rating Curve= 0 ,0
Exp/Cntr=0.3,0.1

Chan Stop Cuts=-1
Use User Specified Reach Order=0
Composite Channel Slope=5